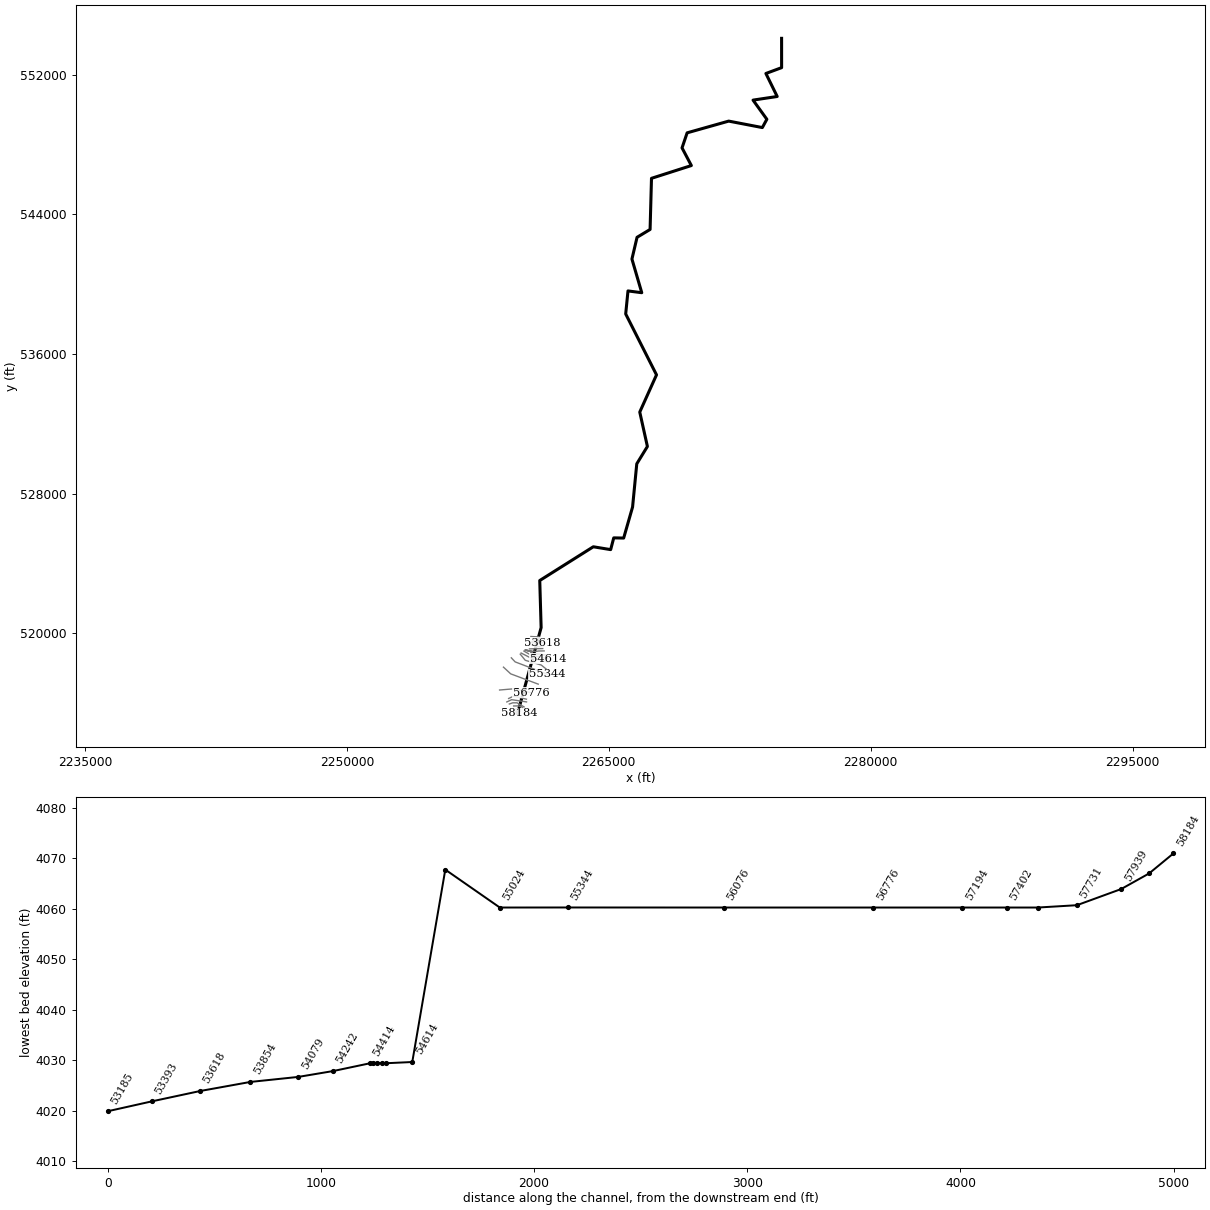
--- SHVRSFK.prj (project) ---

Proj Title=SHVRSFK
Current Plan=p01
Default Exp/Contr=0,0
English Units
Geom File=g01
Flow File=f01
Plan File=p01
BEGIN DESCRIPTION:
Stream Name: Shavers Fork
Flood Zone: Approximate
Pocahontas County, WV
HEC-RAS Version: RAS 6.1.0
Vertical Datum: NAVD88
Projection: NAD 1983 StatePlane West Virginia S FIPS 4702 (US Feet)
Terrain: 1-meter LIDAR (FEMA Region III 3DEP collected 2016-2018)
Land Use: 2019 NLCD
Hydrologic Method:
WV SIR2010-5033 regression equations weighted with gage 03067500 (Shavers Fork at Cheat Bridge)
Model Notes:
1% plus and 0.2% profiles cross around Station 10000 due to regression vs. gage flow weighting.
KWEL elevation used from Randolph County model.
END DESCRIPTION:
DSS Export Rating Curves= 0
DSS Export Rating Curve Sorted= 0
DSS Export Volume Flow Curves= 0
DXF OffsetX= 0
DXF OffsetY= 0
DXF ScaleX= 0
DXF ScaleY= 0

--- SHVRSFK.p01 (plan) ---

Plan Title=Floodplain
Program Version=6.10
Short Identifier=Floodplain
Geom File=g01
Flow File=f01
Subcritical Flow
K Sum by GR= 0
Std Step Tol= 0.01
Critical Tol= 0.01
Num of Std Step Trials= 20
Max Error Tol= 0.3
Flow Tol Ratio= 0.001
Split Flow NTrial= 30
Split Flow Tol= 0.02
Split Flow Ratio= 0.02
Log Output Level= 0
Friction Slope Method= 1
Unsteady Friction Slope Method= 2
Unsteady Bridges Friction Slope Method= 1
Parabolic Critical Depth
Global Vel Dist= 0 , 0 , 0
Global Log Level= 0
CheckData=True
Encroach Param=-1 ,0,0, 0
Mapping Interval=1HOUR
Computation Time Step Use Courant=        0
Computation Time Step Use Time Series=    0
Computation Time Step Count To Double=0
Computation Time Step Max Doubling=0
Computation Time Step Max Halving=0
Computation Time Step Residence Courant=0
Run HTab= 0
Run UNet= 0
Run Sediment= 0
Run PostProcess= 0
Run WQNet= 0
Run RASMapper=-1
UNET Theta= 0
UNET Theta Warmup= 0
UNET ZTol= 0
UNET ZSATol= 0
UNET MxIter= 0
UNET Max Iter WO Improvement= 0
UNET MaxInSteps= 0
UNET DtIC= 0
UNET DtMin= 0
UNET MaxCRTS= 0
UNET WFStab= 0
UNET SFStab= 0
UNET WFX= 1
UNET SFX= 1
UNET Gravity=32.174
UNET 1D Methodology=Finite Difference
UNET DSS MLevel= 1
UNET Pardiso=0
UNET DZMax Abort= 0
UNET Use Existing IB Tables= 0
UNET Froude Reduction=False
UNET Froude Limit= 0
UNET Froude Power= 0
UNET D1 Cores= 0
UNET WindReference=Eulerian
UNET WindDragFormulation=Hsu (1988)
UNET D2 Coriolis=0
UNET D2 Cores= 0
UNET D2 Theta= 1
UNET D2 Theta Warmup= 1
UNET D2 Z Tol= 0.01
UNET D2 Volume Tol= 0.01
UNET D2 Max Iterations= 20
UNET D2 Equation= 0
UNET D2 RampUpFraction=0.1
UNET D2 TimeSlices= 1
UNET D2 Turbulence Formulation=Non-Conservative (original)
UNET D2 Eddy Viscosity=0.3
UNET D2 Transverse Eddy Viscosity=0.1
UNET D2 Smagorinsky Mixing=0
UNET D2 BCVolumeCheck=0
UNET D2 Cores=0
UNET D2 SolverType=PARDISO (Direct)
UNET D2 Minimum Iterations= 2147483647
UNET D2 Maximum Iterations= 2147483647
UNET D2 Restart Number= 10
UNET D2 Relaxation Coeff=1.3
UNET D2 SOR Precondition Iterations= 10
UNET D2 ILUT Maximum Fill= 8
UNET D2 ILUT Tolerance=1E-08
UNET D1D2 MaxIter= 0
UNET D1D2 ZTol=0.01
UNET D1D2 QTol=0.1
UNET D1D2 MinQTol=1
Write IC File= 0
Write IC File at Fixed DateTime=0
Write IC File at Sim End=0
Echo Input=False
Echo Parameters=False
Echo Output=False
Write Detailed= 0
HDF Write Warmup=0
HDF Write Time Slices=0
HDF Flush=0
HDF Compression= 1
HDF Chunk Size= 1
HDF Spatial Parts= 1
HDF Use Max Rows=0
HDF Fixed Rows= 1
Calibration Method= 0
Calibration Iterations= 20
Calibration Max Change=0.05
Calibration Tolerance=0.2
Calibration Maximum=1.5
Calibration Minimum=0.5
Calibration Optimization Method= 1
WQ AD Non Conservative
WQ ULTIMATE=-1
WQ Max Comp Step=1HOUR
WQ Output Interval=15MIN
WQ Output Selected Increments= 0
WQ Output face flow=0
WQ Output face velocity=0
WQ Output face area=0
WQ Output face dispersion=0
WQ Output cell volume=0
WQ Output cell surface area=0
WQ Output cell continuity=0
WQ Output cumulative cell continuity=0
WQ Output face conc=0
WQ Output face dconc_dx=0
WQ Output face courant=0
WQ Output face peclet=0
WQ Output face adv mass=0
WQ Output face disp mass=0
WQ Output cell mass=0
WQ Output cell source sink temp=0
WQ Output nsm pathways=0
WQ Output nsm derived pathways=0
WQ Create Restart=0
WQ Fixed Restart=0
WQ System Summary=0
WQ Write To DSS=0
Sorting and Armoring Iterations= 10
XS Update Threshold= 0.02
Bed Roughness Predictor= 0
Hydraulics Update Threshold= 0.02
Energy Slope Method= 1
Volume Change Method= 1
Sediment Retention Method= 0
Sediment TS Multiplier= 1
Warm Up Method= 0
XS Weighting Method= 0
Number of US Weighted Cross Sections= 1
Number of DS Weighted Cross Sections= 1
Upstream XS Weight=0
Main XS Weight=1
Downstream XS Weight=0
Number of DS XS's Weighted with US Boundary= 1
Upstream Boundary Weight= 1
Weight of XSs Associated with US Boundary= 0
Number of US XS's Weighted with DS Boundary= 1
Downstream Boundary Weight= 0.5
Weight of XSs Associated with DS Boundary= 0.5
Percentile Method= 0
Sediment Output Level= 3
Mass or Volume Output= 0
Output Increment Type= 1
Profile and TS Output Increment= 1
Transport Output Increment 1
XS Output Flag= 0
XS Output Increment= 10
Read HDF5 Sediment Hotstart= 0
Sediment Hotstart Type= 0
Write Gradation File= 0
Read Gradation Hotstart= 0
Write HDF5 File= 1
Write Binary Output= 1
Write DSS Sediment File= 0
DSS Sediment Output Type= 1
SV Curve= 0
Specific Gage Flag= 0
Subcell Erosion Methods= 0
Subcell Deposition Methods= 0
Advection Scheme= 1
Matrix Solver= 0
Implicit Weighting Factor= 1
Maximum Outer Loop Convergence Iterations= 5
Convergence Maximum Absolute= 0.001
Convergence RMSE= 0.0001
Grain Fractions Max Abs Error= 0.001
Max Subgrid Regions= 1
Max Subgrid Length Scale= 3.402823E+38
Initial Layer Thickness= 3.402823E+38
Min Layer Thickness= 3.402823E+38
Max Layer Thickness= 3.402823E+38
Number of Layers= 5

--- SHVRSFK.f01 (steady flow) ---

Flow Title=USGS Regression Equation
Program Version=6.10
Number of Profiles= 6
Profile Names=01pct,10pct,04pct,02pct,0_2pct,01plus
River Rch & RM=SHVRSFK,Main            ,58184
     684     364     482     580     952    1010
River Rch & RM=SHVRSFK,Main            ,54242
     771     412     545     654    1070    1140
River Rch & RM=SHVRSFK,Main            ,51181
     861     462     610     731    1190    1270
River Rch & RM=SHVRSFK,Main            ,48749
     985     532     700     838    1360    1460
River Rch & RM=SHVRSFK,Main            ,48482
    1110     604     793     948    1540    1650
River Rch & RM=SHVRSFK,Main            ,41037
    1510     827    1080    1290    2070    2230
River Rch & RM=SHVRSFK,Main            ,39183
    1690     929    1210    1440    2310    2490
River Rch & RM=SHVRSFK,Main            ,36490
    2010    1110    1450    1720    2740    2970
River Rch & RM=SHVRSFK,Main            ,29082
    2240    1250    1620    1920    3060    3320
River Rch & RM=SHVRSFK,Main            ,22026
    2890    1620    2100    2480    3910    4270
River Rch & RM=SHVRSFK,Main            ,8275
    4610    2830    3480    4040    6230    5520
Boundary for River Rch & Prof#=SHVRSFK,Main            , 1
Up Type= 0
Dn Type= 1
Dn Known WS=3701.3
Boundary for River Rch & Prof#=SHVRSFK,Main            , 2
Up Type= 0
Dn Type= 1
Dn Known WS=3699.8
Boundary for River Rch & Prof#=SHVRSFK,Main            , 3
Up Type= 0
Dn Type= 1
Dn Known WS=3700.4
Boundary for River Rch & Prof#=SHVRSFK,Main            , 4
Up Type= 0
Dn Type= 1
Dn Known WS=3700.9
Boundary for River Rch & Prof#=SHVRSFK,Main            , 5
Up Type= 0
Dn Type= 1
Dn Known WS=3702.4
Boundary for River Rch & Prof#=SHVRSFK,Main            , 6
Up Type= 0
Dn Type= 1
Dn Known WS=3702
DSS Import GetInterval= 0
DSS Import GetPeak= 0
DSS Import FillOption= 0

--- SHVRSFK.g01 (geometry) ---

Geom Title=Geometry
Program Version=6.10

River Reach=SHVRSFK         ,Main
Reach XY= 30
     2259778.926      515403.492     2261127.108      520316.597
     2261048.166      523014.814     2264115.475      524948.751
     2265109.915       524785.52     2265286.044      525459.215
      2265855.01      525447.983     2266364.781      527228.511
     2266605.269      529703.918     2267214.417      530697.525
     2266776.339      532670.268     2267735.844      534802.463
     2265970.801      538293.154     2266102.217      539613.176
     2266891.186      539511.276     2266328.362      541440.197
     2266621.123      542685.851     2267368.182      543137.034
      2267448.53       546067.49     2269732.009      546799.535
      2269197.92      547812.048     2269490.294      548674.892
     2271870.252      549346.686     2273797.555      548976.466
     2274056.024      549451.849     2273264.889      550550.181
     2274648.335      550757.592     2274001.373      552076.425
     2274901.716      552410.741     2274900.555         554091.

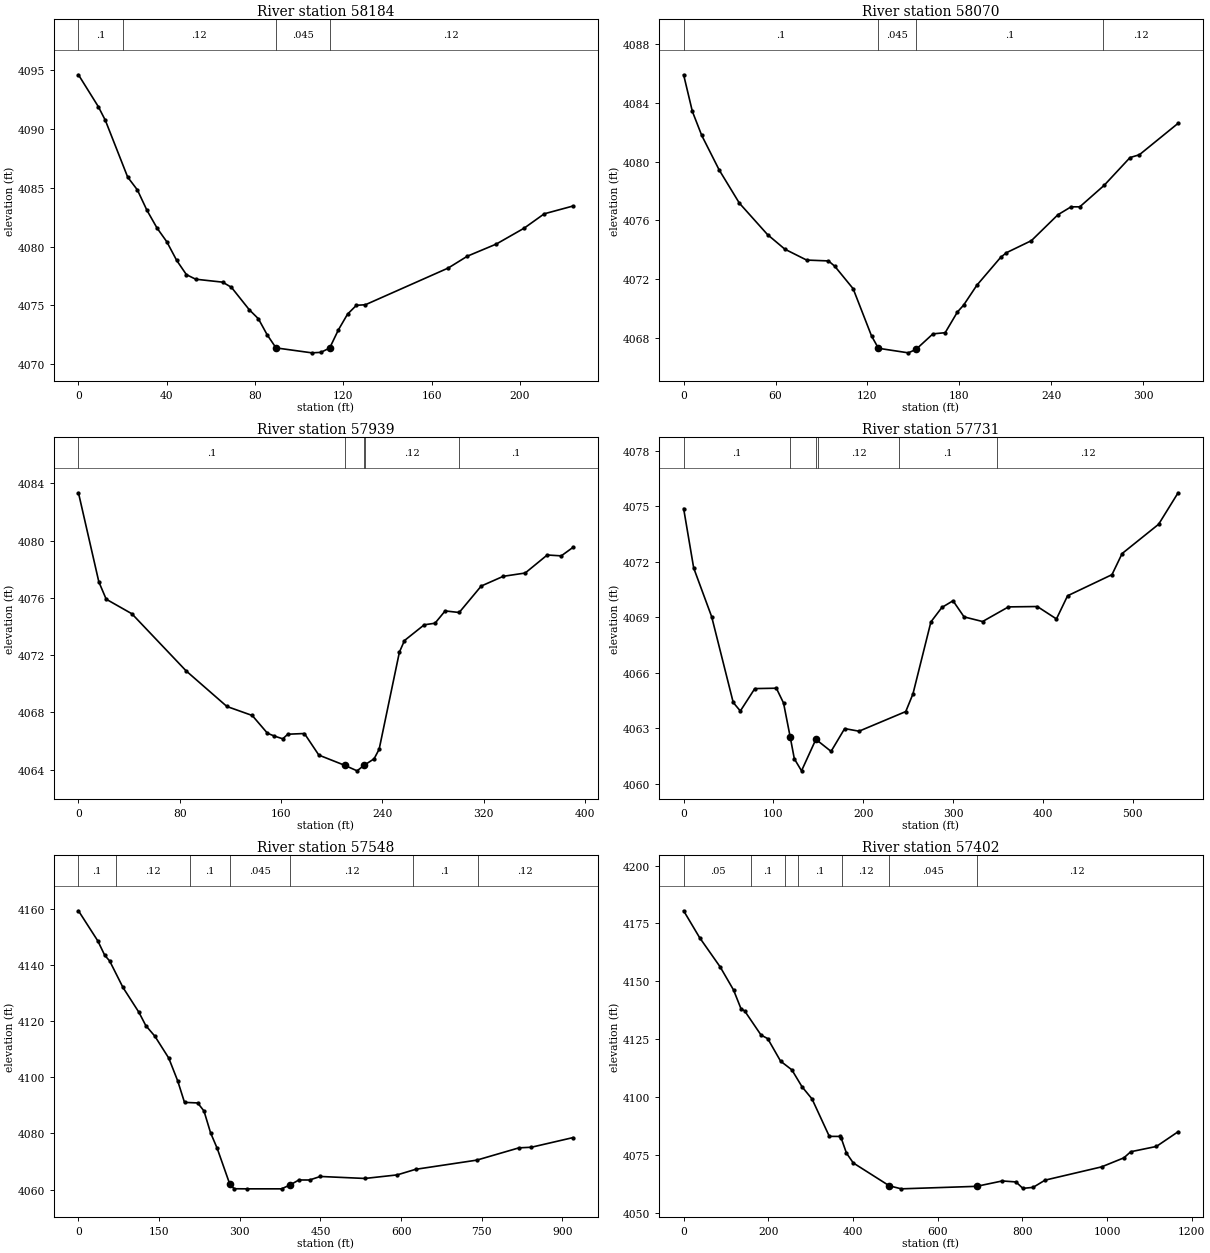
Type RM Length L Ch R = 1 ,58184   ,114.4,114.4,114.4
XS GIS Cut Line= 4
2259684.05336243515399.9111249892259730.19257414515421.977704501
2259829.82652406 515436.688757512259896.02626259 515407.93533572
#Sta/Elev= 30
       0  4094.6       9 4091.89    12.2 4090.72    22.3  4085.9    26.7 4084.81
      31 4083.09    35.6 4081.57      40 4080.41    44.5 4078.82    48.9 4077.61
    53.1 4077.22    65.3 4076.97    69.3 4076.53    77.4 4074.62    81.5 4073.86
    85.5 4072.49    89.5 4071.38   105.7 4070.96   109.8    4071   113.8 4071.37
   117.8 4072.93   121.9 4074.25   125.9    4075     130 4075.05   167.5 4078.17
   176.2 4079.18   189.3 4080.21   201.9 4081.56     211 4082.78     224 4083.44
#Mann= 4 ,-1,0
       0      .1       0      20     .12       0    89.5    .045       0
   113.8     .12       0
Bank Sta=89.5,113.8
XS Rating Curve= 0 ,0
Exp/Cntr(USF)=0,0
Exp/Cntr=0.3,0.1

Type RM Length L Ch R = 1 ,58070   ,131.5,130.7,127.3
XS GIS Cut Line= 4
2259642.59494031515481.4906007622259708.79467885515538.328760113
2259845.20626129515546.3529708442259936.81600048515508.906654096
#Sta/Elev= 30
       0  4085.9     5.7 4083.41    11.8 4081.78    23.2 4079.43    36.4 4077.17
    54.8 4075.03    66.1 4074.04    80.3  4073.3    94.6 4073.24    98.7 4072.88
   110.7 4071.35   122.7 4068.14   127.2  4067.3   146.7 4066.99   151.7 4067.22
   162.8 4068.28   170.8 4068.36   178.8 4069.77   182.8 4070.23   191.5 4071.59
     207 4073.48   210.8  4073.8   227.1 4074.62   244.4 4076.38     253 4076.92
   258.7 4076.92   274.6 4078.38   291.5 4080.27   297.6 4080.46   322.9  4082.6
#Mann= 4 ,-1,0
       0      .1       0   127.2    .045       0   151.7      .1       0
   273.9     .12       0
Bank Sta=127.2,151.7
XS Rating Curve= 0 ,0
Exp/Cntr(USF)=0,0
Exp/Cntr=0.3,0.1

Type RM Length L Ch R = 1 ,57939   ,212.5,207.8,201.2
XS GIS Cut Line= 4
2259597.79309706515617.2334989752259653.29388796515653.342447269
2259877.30310422515666.7161318222259946.17757967515594.498235235
#Sta/Elev= 30
       0 4083.35    16.1 4077.12    21.9 4075.91    42.2 4074.89    85.1 4070.89
   117.2 4068.41   137.2 4067.78   149.2 4066.54   154.7 4066.34   161.3 4066.15
   165.3 4066.47   178.4 4066.52   189.8 4065.01   210.1  4064.3     220 4063.91
   225.4 4064.29   233.4 4064.75   237.4 4065.42   253.4 4072.21   257.4 4073.02
     273 4074.12   281.5 4074.23   289.5 4075.09   300.6 4074.98     318 4076.83
   335.4 4077.51   352.7 4077.74   370.1    4079   381.2 4078.94   390.4 4079.53
#Mann= 5 ,-1,0
       0      .1       0   210.1    .045       0   225.4      .1       0
  226.21     .12       0  300.62      .1       0
Bank Sta=210.1,225.4
XS Rating Curve= 0 ,0
Exp/Cntr(USF)=0,0
Exp/Cntr=0.3,0.1

Type RM Length L Ch R = 1 ,57731   ,207.9,182.9,181.5
XS GIS Cut Line= 4
2259552.99125381515824.5256095472259832.01844143515827.162971837
2259994.45301643515788.1828964512260068.34611586515714.647315289
#Sta/Elev= 30
       0 4074.87    11.2 4071.66    31.2 4069.03    55.2  4064.4    63.1 4063.94
    79.2 4065.15   103.2 4065.17   111.2 4064.37118.59874062.539   123.2 4061.36
   131.2 4060.71147.1984 4062.41   164.1 4061.76   179.2 4062.99   195.2 4062.85
   247.2 4063.91   255.2 4064.86   275.2 4068.75   287.4 4069.53   299.8 4069.89
   312.1 4069.02   332.7 4068.77   361.5 4069.56   393.6 4069.58   414.9 4068.91
   427.3 4070.16   476.7  4071.3     488 4072.44   528.6 4074.02   550.3 4075.72
#Mann= 6 ,-1,0
       0      .1       0118.5987    .045       0147.1984      .1       0
     150     .12       0     240      .1       0  349.04     .12       0
Bank Sta=118.5987,147.1984
XS Rating Curve= 0 ,0
Exp/Cntr(USF)=0,0
Exp/Cntr=0.3,0.1

Type RM Length L Ch R = 1 ,57548   ,160.9,147,181.6
BEGIN DESCRIPTION:
Expansion into pond
END DESCRIPTION:
XS GIS Cut Line= 4
2259305.95879037 515937.570630062259500.97244218 516005.58526822
2259746.48040106 516004.83920091 2260151.0191379515770.606512421
#Sta/Elev= 30
       0 4159.37      36 4148.63    48.9 4143.49      58 4141.49    82.8 4132.03
   112.5 4123.16   125.2 4118.45   142.1 4114.66   167.9 4106.86   184.5 4098.76
   197.2 4091.07   221.7 4090.87   233.4 4088.01   245.7 4080.21     258 4074.68
   281.6 4061.81   289.7 4060.28   313.7 4060.25   377.7 4060.25   393.94061.687
   409.9 4063.41   429.7  4063.4   449.7 4064.66   532.6 4063.95   592.7 4065.22
     627 4067.21   740.6 4070.48   819.1 4074.86   842.3 4075.08   919.5 4078.51
#Mann= 7 ,-1,0
       0      .1       0      70     .12       0  206.53      .1       0
   281.6    .045       0   393.9     .12       0  622.04      .1       0
  742.04     .12       0
Bank Sta=281.6,393.9
XS Rating Curve= 0 ,0
Exp/Cntr(USF)=0,0
Exp/Cntr=0.5,0.3

Type RM Length L Ch R = 1 ,57402   ,211.6,207.2,218.2
XS GIS Cut Line= 3
2259162.19979783516054.3122312282259435.77134048516185.183715775
2260290.84667054516057.199442238
#Sta/Elev= 30
       0 4180.48    37.7 4168.88    86.4 4156.18   117.9 4146.23   135.6 4138.08
   144.1 4137.19   182.8 4126.76   198.6  4125.2   229.1 4115.44   255.6 4111.71
   279.6  4104.4   303.3 4099.11   344.1 4082.94   368.4 4082.91   372.4 4082.08
   384.5 4075.73   400.7 4071.44   485.7 4061.57     514 4060.25   691.9 4061.33
   752.6 4063.66     785 4063.23   801.2 4060.45   825.4 4060.89   853.7 4064.01
   987.2 4069.75  1039.8 4073.65    1056 4076.29  1116.6 4078.58  1167.9 4084.94
#Mann= 7 ,-1,0
       0     .05       0     160      .1       0     240     .05       0
     270      .1       0  373.26     .12       0   485.7    .045       0
   691.9     .12       0
Bank Sta=485.7,691.9
XS Rating Curve= 0 ,0
Exp/Cntr(USF)=0,0
Exp/Cntr=0.3,0.1

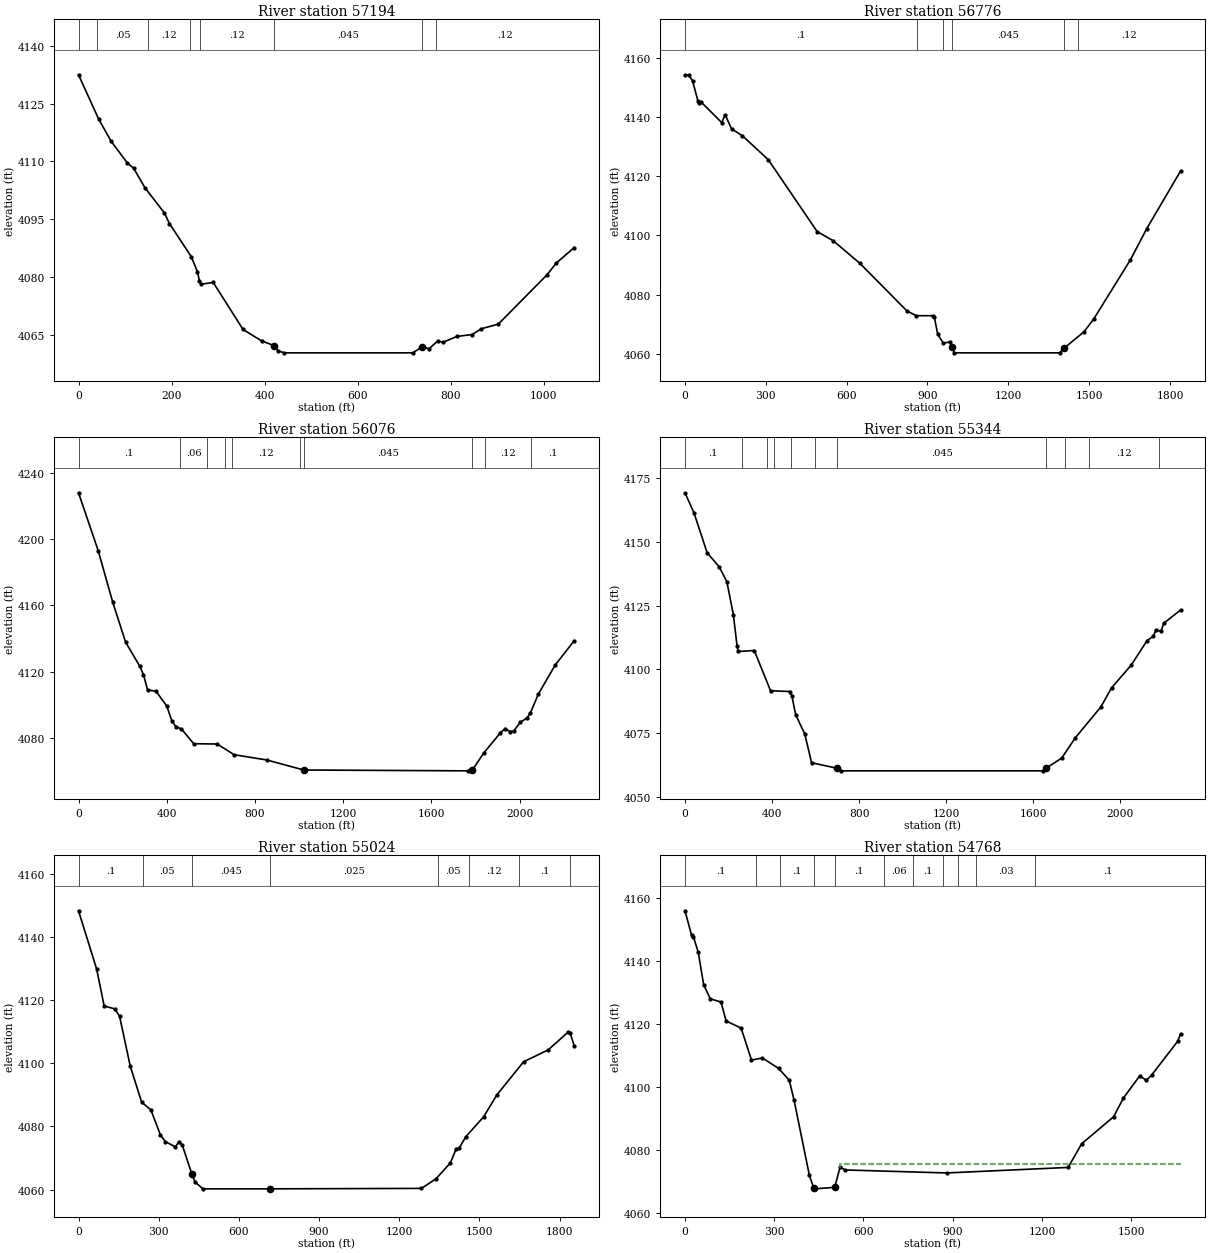
Type RM Length L Ch R = 1 ,57194   ,420.6,418.6,426.7
XS GIS Cut Line= 4
2259264.98544382516252.5134324842259517.12582496516370.694518013
2259656.45657687516366.7333285492260285.10210883516213.000043498
#Sta/Elev= 30
       0 4132.47    43.3 4120.97    69.8 4115.25   105.2 4109.52   118.4 4108.21
   142.9  4103.1   184.6 4096.57   195.4 4093.83   242.1 4085.27   255.6  4081.3
   259.7    4079   264.2 4078.09   289.5 4078.53   353.5 4066.32   393.6 4063.34
419.92474062.144   428.8  4060.8   442.1 4060.25   718.2 4060.25738.5236 4061.82
   753.1 4061.31   771.7 4063.32   782.9 4062.99   812.9  4064.5     846 4065.01
   865.6 4066.51     902 4067.71  1006.4 4080.48    1027 4083.61    1065 4087.58
#Mann= 8 ,-1,0
       0      .1       0      40     .05       0     150     .12       0
     240      .1       0     260     .12       0419.9247    .045       0
738.5236    .025       0  767.85     .12       0
Bank Sta=419.9247,738.5236
XS Rating Curve= 0 ,0
Exp/Cntr(USF)=0,0
Exp/Cntr=0.3,0.1

Type RM Length L Ch R = 1 ,56776   ,733.7,699.6,679.3
XS GIS Cut Line= 3
2258747.87777803516739.2783217042259594.17433175516811.370540662
2260557.32932524516582.210566759
#Sta/Elev= 30
       0 4154.15    13.1 4154.39    28.4 4152.28    48.5 4145.38    52.5 4144.85
    61.2 4145.05   136.8 4138.16   148.8  4140.9   172.9 4136.09   213.1 4133.74
   309.1 4125.65   490.3 4101.33   550.3 4098.19   649.4 4090.52   823.5 4074.45
   858.8 4072.82   921.3 4072.83   925.4 4072.36   937.8 4066.59   958.3 4063.53
     983 4063.94   991.2 4062.32   999.4 4060.25    1390 4060.25  1406.5  4061.8
    1481  4067.4  1517.5 4071.79  1653.2 4091.77  1713.1 4102.22  1839.4 4121.84
#Mann= 6 ,-1,0
       0      .1       0  859.36     .07       0  959.36     .08       0
   991.2    .045       0  1406.5    .025       0 1459.36     .12       0
Bank Sta=991.2,1406.5
XS Rating Curve= 0 ,0
Exp/Cntr(USF)=0,0
Exp/Cntr=0.3,0.1

Type RM Length L Ch R = 1 ,56076   ,737,731.8,732.4
XS GIS Cut Line= 3
 2258970.4427085518049.7916873782259383.65225671517665.529567043
2260960.52455777517075.622424699
#Sta/Elev= 30
       0 4227.97    89.8 4192.82   155.3 4161.92   213.9 4137.75     277 4123.57
   294.6 4118.27     313 4109.17     352 4108.17   400.3 4099.32     423 4090.54
   441.4 4086.84   466.7 4085.54   522.4  4076.6   628.9 4076.44   705.8 4069.98
   855.2 4066.76  1021.8 4060.75  1764.9 4060.25  1786.8 4060.85  1837.5 4070.97
  1913.8 4083.25  1935.7 4085.77  1957.1 4083.86  1974.2 4084.37    2004 4089.63
    2034 4092.05  2049.4 4095.12  2085.2 4106.48  2162.1 4124.13  2247.9 4138.69
#Mann= 10 ,-1,0
       0      .1       0     460     .06       0  584.27     .07       0
  664.27     .08       0  694.27     .12       0 1004.27     .05       0
  1021.8    .045       0  1786.8    .025       0 1844.27     .12       0
 2054.27      .1       0
Bank Sta=1021.8,1786.8
XS Rating Curve= 0 ,0
Exp/Cntr(USF)=0,0
Exp/Cntr=0.3,0.1

Type RM Length L Ch R = 1 ,55344   ,330,320.1,422.2
XS GIS Cut Line= 3
2259420.71187872518583.6102592732259638.26031472518351.167014593
2261468.61143461517652.115652412
#Sta/Elev= 30
       0 4169.23    41.7 4161.29   101.9 4145.71   157.3 4140.21   192.4  4134.4
   222.5 4121.39   239.2  4109.3   244.4 4107.03   318.4 4107.42   393.2 4091.65
   483.1 4091.34   491.7 4089.47   508.8 4082.21   550.7 4074.66   581.7 4063.44
   697.2 4061.31     718 4060.26  1643.5 4060.26  1660.6 4061.35  1731.2 4065.25
  1793.1 4073.15  1910.9 4085.28  1960.3 4092.79  2050.3 4101.65  2123.1 4111.27
  2151.4 4112.95    2165 4115.57  2187.3  4114.9  2200.1 4118.09  2277.7 4123.31
#Mann= 11 ,-1,0
       0      .1       0     260     .08       0  378.37      .1       0
  408.37     .08       0  488.37      .1       0  598.37     .05       0
   697.2    .045       0  1660.6    .025       0 1748.37      .1       0
 1858.37     .12       0 2178.37      .1       0
Bank Sta=697.2,1660.6
XS Rating Curve= 0 ,0
Exp/Cntr(USF)=0,0
Exp/Cntr=0.3,0.1

Type RM Length L Ch R = 1 ,55024   ,257,255.7,436.7
XS GIS Cut Line= 4
2259931.06885298518795.1524272272260218.75820427518441.792332568
2261133.34977182518170.7140232152261479.65723442 517891.29000666
#Sta/Elev= 30
       0 4148.22    67.6 4129.86      96 4118.08   135.8 4117.19   153.8  4114.8
   193.4 4099.13   236.2 4087.66   270.8 4085.24   306.4 4077.31   324.9 4075.21
   362.9  4073.5   375.5 4075.22   388.2 4074.09424.18734064.923   435.8 4062.43
   465.5 4060.25715.6689 4060.25  1283.2 4060.39  1337.4 4063.42  1391.7 4068.48
  1413.2 4072.92  1423.5 4073.02  1449.2 4076.74    1516 4083.05  1564.9 4089.91
  1665.1 4100.42  1757.6 4104.22  1832.4 4109.87  1839.8 4109.48  1854.6 4105.55
#Mann= 8 ,-1,0
       0      .1       0     240     .05       0424.1873    .045       0
715.6689    .025       0 1345.66     .05       0 1459.58     .12       0
 1649.58      .1       0 1839.58     .12       0
Bank Sta=424.1873,715.6689
XS Rating Curve= 0 ,0
Exp/Cntr(USF)=0,0
Exp/Cntr=0.3,0.1

Type RM Length L Ch R = 1 ,54768   ,156.5,154.9,212.6
BEGIN DESCRIPTION:
Contraction from pond
END DESCRIPTION:
XS GIS Cut Line= 3
2259980.33221069518859.546774155 2260458.5903124518613.314880202
2261550.06053463518326.833542046
#Sta/Elev= 30
       0 4155.93    22.3 4148.14    28.4 4147.71    44.8 4142.71    62.8 4132.45
    85.3 4128.02   121.3 4126.98   138.3 4120.98   188.7 4118.73   223.6 4108.58
     260 4109.25   314.8 4105.95   350.7 4102.17   366.9 4095.83   418.2 4072.03
   432.3 4068.14   436.2 4067.75   503.3 4068.22   521.7 4074.72   537.9 4073.74
     880 4072.79  1288.1 4074.54  1333.6 4082.03  1441.1 4090.62  1474.2 4096.55
  1528.6 4103.55  1551.5 4102.18  1569.3 4103.88  1656.1 4114.49  1666.4 4116.93
#Mann= 11 ,-1,0
       0      .1       0     240     .03       0     320      .1       0
   432.3    .045       0   503.3      .1       0  667.92     .06       0
  767.92      .1       0  867.92     .03       0  917.92      .1       0
  977.92     .03       0 1177.92      .1       0
#XS Ineff= 2 , 0
                          521.09         4075.56
Permanent Ineff=
       F       F
Bank Sta=432.3,503.3
XS Rating Curve= 0 ,0
Exp/Cntr(USF)=0,0
Exp/Cntr=0.5,0.3

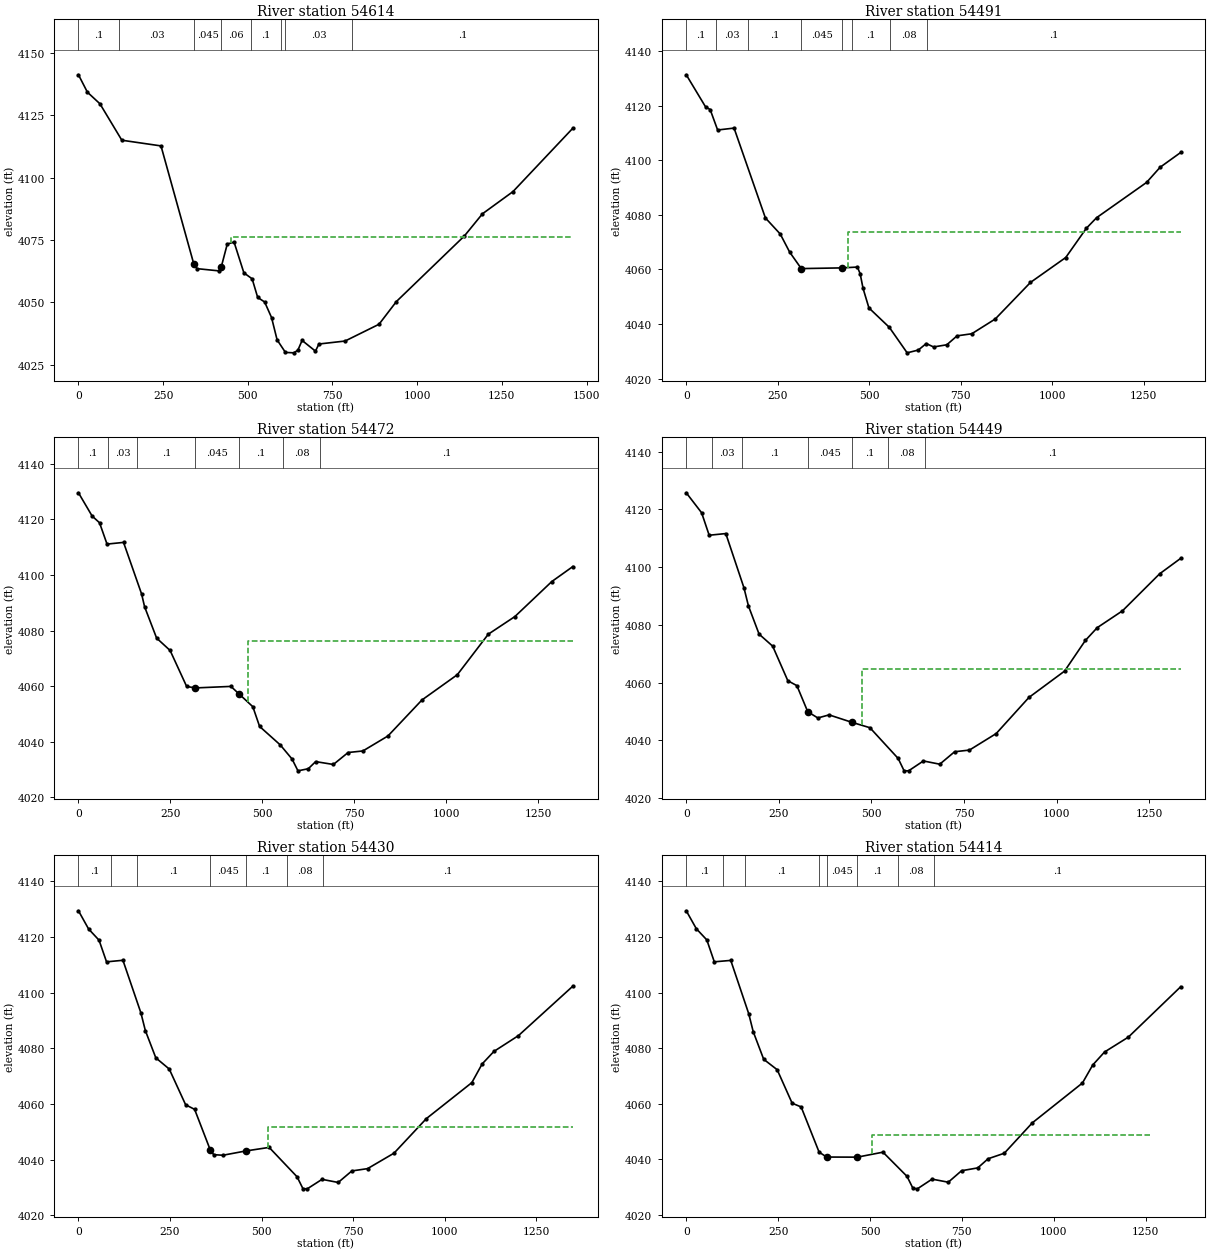
Type RM Length L Ch R = 1 ,54614   ,165.7,122.7,98.9
BEGIN DESCRIPTION:
Contraction from pond
END DESCRIPTION:
XS GIS Cut Line= 3
 2260141.3299875518970.8246493062260529.61874335518745.901284638
2261516.91393353518528.080763065
#Sta/Elev= 30
       0 4141.21    26.4 4134.23    63.4 4129.58   128.1 4114.96   243.7 4112.68
   340.7 4065.24     350 4063.45     416 4062.54   421.9 4064.26   439.4 4073.33
   459.5 4074.09   488.4 4061.77   512.8 4059.37   529.2  4051.9   549.7 4050.08
   570.1 4043.84   586.5 4034.89   611.1 4029.85   636.1 4029.68     648  4030.8
   660.3 4034.66   699.8 4030.35   709.9 4033.22   787.1 4034.41   887.4 4041.14
   938.8 4050.27  1139.5 4076.57  1192.8 4085.45  1282.9 4094.35  1459.8  4119.8
#Mann= 8 ,-1,0
       0      .1       0     120     .03       0   340.7    .045       0
   421.9     .06       0  508.73      .1       0  598.73     .06       0
  608.73     .03       0  808.73      .1       0
#XS Ineff= 2 , 0
                          449.15         4076.25
Permanent Ineff=
       F       F
Bank Sta=340.7,421.9
XS Rating Curve= 0 ,0
Exp/Cntr(USF)=0,0
Exp/Cntr=0.5,0.3

Type RM Length L Ch R = 1 ,54491   ,22.8,19,17.9
BEGIN DESCRIPTION:
Expansion from spillway
END DESCRIPTION:
XS GIS Cut Line= 4
 2260220.0963982519023.1480682942260497.18916655518968.148526873
2260588.69763757518807.3890163372261469.22150561518739.816943647
#Sta/Elev= 30
       0 4131.36    53.1 4119.52    65.3 4118.63    85.7 4111.12   130.6 4111.82
   216.2 4078.88   256.7    4073   282.5 4066.36   314.24060.319   425.6 4060.58
   467.5 4060.88     475 4058.45     483 4053.04     499  4045.9   554.7 4038.79
   603.4 4029.44     634 4030.47   655.5 4032.84   675.6  4031.6   711.7 4032.39
   739.8 4035.67   779.9 4036.43   844.1 4041.85   940.3 4055.25  1036.6 4064.38
  1092.8 4075.08  1120.9 4078.98  1257.3 4091.89  1294.4 4097.46  1350.6 4102.88
#Mann= 8 ,-1,0
       0      .1       0      80     .03       0     170      .1       0
   314.2    .045       0   425.6     .06       0   452.5      .1       0
  557.48     .08       0  657.48      .1       0
#XS Ineff= 2 , 0
                          441.34         4073.84
Permanent Ineff=
       F       F
Bank Sta=314.2,425.6
XS Rating Curve= 0 ,0
Exp/Cntr(USF)=0,0
Exp/Cntr=0.5,0.3

Type RM Length L Ch R = 1 ,54472   ,11.8,22.7,22.5
XS GIS Cut Line= 4
2260228.04312958519024.674659195  2260526.384127518963.297343968
2260604.11083852518810.1156528412261469.42023777518742.918601401
#Sta/Elev= 30
       0 4129.57    37.2  4121.2    57.3 4118.78    77.7  4111.1   122.6 4111.71
   171.7 4093.14   179.8 4088.56   212.5 4077.27   249.2 4072.81   294.2 4059.86
   317.94059.332   414.6 4059.88   435.74057.276   474.1 4052.57   492.5 4045.47
   548.6 4038.83   580.7 4033.75   596.8 4029.49   624.9 4030.25   644.9 4032.81
   693.1 4031.78   733.2 4036.09   773.3 4036.64   841.5 4042.04   933.8 4054.98
  1030.1 4064.09  1114.3 4078.67  1186.6 4085.02  1286.9 4097.61  1344.3 4103.03
#Mann= 7 ,-1,0
       0      .1       0      80     .03       0     160      .1       0
   317.9    .045       0   435.7      .1       0  556.36     .08       0
  656.36      .1       0
#XS Ineff= 2 , 0
                          460.82         4076.37
Permanent Ineff=
       F       F
Bank Sta=317.9,435.7
XS Rating Curve= 0 ,0
Exp/Cntr(USF)=0,0
Exp/Cntr=0.5,0.3

Type RM Length L Ch R = 1 ,54449   ,5.1,19.4,15.2
XS GIS Cut Line= 4
2260243.50762125519022.8704090262260561.57219111518957.625726654
2260620.73554034518809.0848761012261468.90863577518744.246918619
#Sta/Elev= 30
       0 4125.76    41.5 4118.84    61.9 4111.06   106.8 4111.64   155.8 4092.87
     168 4086.56   196.7 4076.82   233.4 4072.65   274.3 4060.69   298.8 4058.98
   328.14049.949   355.3  4047.8   385.8 4048.86   446.54046.321     496 4044.42
   572.3 4033.77   588.3  4029.5   600.4 4029.49   640.4 4032.91   684.6 4031.79
   724.7  4036.1   764.8 4036.68     837  4042.4   925.3 4054.89  1021.6 4064.02
  1077.7 4074.62  1109.8 4079.06    1178 4084.89  1278.3  4097.7  1335.2 4103.06
#Mann= 7 ,-1,0
       0      .1       0      70     .03       0     150      .1       0
   328.1    .045       0   446.5      .1       0  544.58     .08       0
  644.58      .1       0
#XS Ineff= 2 , 0
                          474.46         4064.59
Permanent Ineff=
       F       F
Bank Sta=328.1,446.5
XS Rating Curve= 0 ,0
Exp/Cntr(USF)=0,0
Exp/Cntr=0.5,0.3

Type RM Length L Ch R = 1 ,54430   ,15.7,15.7,15.7
XS GIS Cut Line= 4
2260228.95889298519025.3099156232260591.30430967518953.375204426
2260630.04746993518809.1001567522261459.46610824518746.985104543
#Sta/Elev= 30
       0 4129.42    27.7 4122.88    56.3 4118.84    76.7 4111.07   121.5 4111.63
   170.5 4092.76   182.7 4086.38   211.3 4076.58     248 4072.55   292.8  4059.7
   317.3 4058.06  359.624043.612   369.4 4041.78   394.5 4041.57   456.6  4043.1
   520.9 4044.39   597.1 4033.83   613.2 4029.55   624.9  4029.5   665.3 4032.91
   709.5 4031.79   746.7 4035.93   789.7 4036.76   861.9 4042.32   950.1 4054.72
  1074.5 4067.67  1102.6 4074.37  1134.7 4078.87  1201.9 4084.57  1350.5 4102.35
#Mann= 7 ,-1,0
       0      .1       0      90     .03       0     160      .1       0
  359.62    .045       0   456.6      .1       0   568.8     .08       0
   668.8      .1       0
#XS Ineff= 2 , 0
                           518.3         4051.72
Permanent Ineff=
       F       F
Bank Sta=359.62,456.6
XS Rating Curve= 0 ,0
Exp/Cntr(USF)=0,0
Exp/Cntr=0.5,0.3

Type RM Length L Ch R = 1 ,54414   ,133.3,172,133.3
BEGIN DESCRIPTION:
Expansion from spillway
END DESCRIPTION:
XS GIS Cut Line= 4
2260229.22520532519026.191004001 2260609.5921686518953.160547051
 2260642.9680003518809.0551757832261450.78131523 518750.25759416
#Sta/Elev= 30
       0 4129.38    27.4 4122.93      56  4118.9    76.3 4111.03   121.1 4111.54
     170 4092.37   182.2 4085.92   210.7 4075.99   247.4 4072.24   288.1  4060.2
   312.6 4058.86   361.4 4042.63   381.8 4040.85   465.3 4040.81   535.2  4042.6
   600.6 4033.91   616.7 4029.62   628.7 4029.42   668.8 4032.91   712.9  4031.8
     749 4035.93   793.1 4036.95   821.2 4040.23   865.3 4042.22   941.5 4053.14
  1077.9 4067.47  1105.9 4073.94    1138 4078.61  1202.8 4083.96  1345.2 4102.07
#Mann= 8 ,-1,0
       0      .1       0     100     .03       0     160      .1       0
     360     .08       0   381.8    .045       0   465.3      .1       0
  575.23     .08       0  675.23      .1       0
#XS Ineff= 1 ,-1
  506.61  1262.5 4048.64
Permanent Ineff=
       F
Bank Sta=381.8,465.3
XS Rating Curve= 0 ,0
Exp/Cntr(USF)=0,0
Exp/Cntr=0.5,0.3

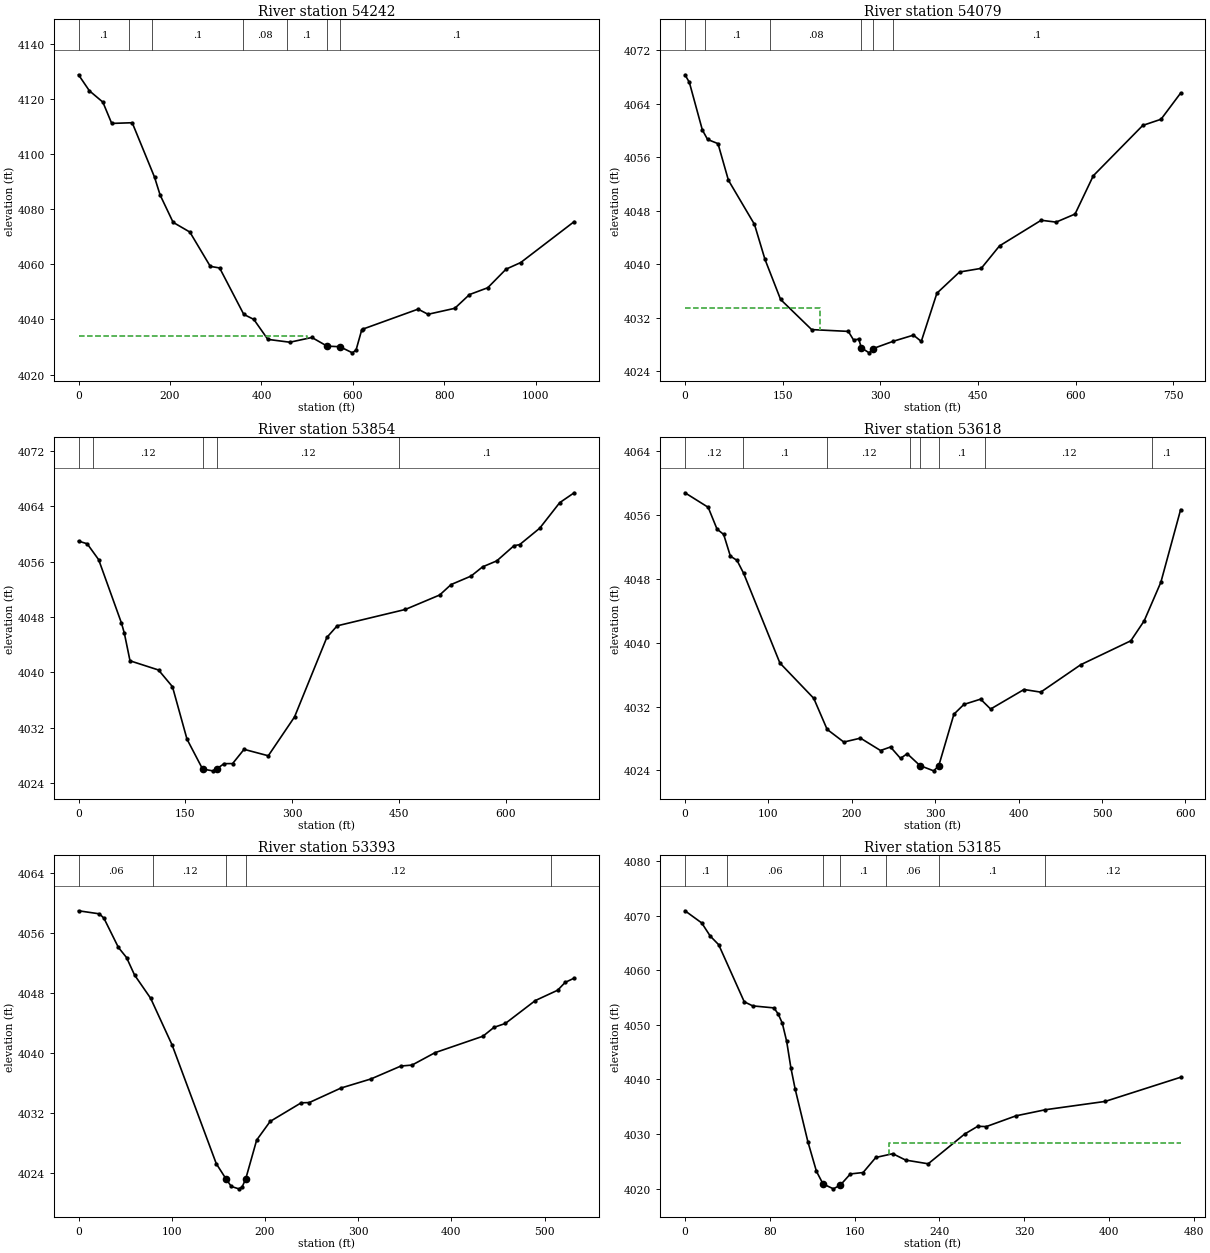
Type RM Length L Ch R = 1 ,54242   ,56.8,163.6,56.8
BEGIN DESCRIPTION:
Expansion from spillway
END DESCRIPTION:
XS GIS Cut Line= 6
2260232.71624374519027.6260981242260621.72844601518956.651585469
2260745.57097345518966.0733845372260804.70278643518942.333980139
2260966.43461337 518974.360546452261301.05824998518980.349468783
#Sta/Elev= 30
       0 4128.73    23.8 4122.92    53.2 4118.82    72.6 4111.09   117.4 4111.34
   166.2  4091.6   178.4 4085.13   206.8 4075.22   243.4 4071.69   288.1 4059.25
   308.5 4058.67   361.3 4041.84   383.3 4040.01   413.9 4032.77   462.1 4031.74
   510.2 4033.46   543.5 4030.32   571.5 4030.11   598.8 4027.89   606.8 4028.92
   618.9 4036.07   622.9 4036.57   742.4 4043.74   764.1 4041.87   822.6 4044.04
   854.7 4049.02   894.7  4051.5   934.7 4058.24   966.7 4060.63  1083.6 4075.47
#Mann= 7 ,-1,0
       0      .1       0     110     .03       0     160      .1       0
     360     .08       0  455.43      .1       0   543.5    .045       0
   571.5      .1       0
#XS Ineff= 2 , 0
          499.61 4033.84  631.01         4034.67
Permanent Ineff=
       F       F
Bank Sta=543.5,571.5
XS Rating Curve= 0 ,0
Exp/Cntr(USF)=0,0
Exp/Cntr=0.5,0.3

Type RM Length L Ch R = 1 ,54079   ,224.8,224.1,222.5
XS GIS Cut Line= 2
2260457.45892875519096.0668548062261218.20779957 519114.97648257
#Sta/Elev= 30
       0 4068.36     6.7 4067.23    26.7 4060.09    34.7 4058.68    50.7 4058.05
    66.7 4052.57   106.7 4045.96   122.8 4040.73   146.8 4034.72   194.5 4030.21
   250.8 4029.94   258.8 4028.66   266.8 4028.78   270.8 4027.48   282.8 4026.73
   288.9 4027.37     320 4028.47   350.8 4029.38   362.8 4028.44   386.8 4035.66
   421.5 4038.83   454.9 4039.38   482.9 4042.74   546.9 4046.58   569.8  4046.3
   598.9 4047.51   626.9 4053.24   702.9 4060.78   730.9  4061.7     761 4065.62
#Mann= 6 ,-1,0
       0     .06       0      30      .1       0     130     .08       0
   270.8    .045       0   288.9     .08       0     320      .1       0
#XS Ineff= 2 , 0
          206.83 4033.48
Permanent Ineff=
       F       F
Bank Sta=270.8,288.9
XS Rating Curve= 0 ,0
Exp/Cntr(USF)=0,0
Exp/Cntr=0.3,0.1

Type RM Length L Ch R = 1 ,53854   ,230.7,236.1,232.2
BEGIN DESCRIPTION:
Inline
END DESCRIPTION:
XS GIS Cut Line= 4
2260559.93238778519324.8134742842260797.93290619519317.460588514
2260909.14583053519230.0458044962261224.36907808519205.137155507
#Sta/Elev= 30
       0 4058.98    12.2 4058.59    28.3 4056.29    60.3 4047.12    64.3 4045.67
    72.3 4041.66   112.3 4040.33   131.9 4037.91   152.3 4030.32   174.2    4026
   188.3 4025.74   194.84026.076   204.3 4026.78   216.3 4026.79   232.4 4028.85
   266.4 4027.92   303.3 4033.55   348.6 4045.04   363.1 4046.72   458.8 4049.09
     507 4051.18     523 4052.69   551.1 4053.92   567.2 4055.25   587.2 4056.12
   611.3 4058.31   619.3 4058.47   647.4 4060.84   675.5 4064.54   695.8 4065.97
#Mann= 5 ,-1,0
       0      .1       0      20     .12       0   174.2    .045       0
   194.8     .12       0  449.57      .1       0
Bank Sta=174.2,194.8
XS Rating Curve= 0 ,0
Exp/Cntr(USF)=0,0
Exp/Cntr=0.3,0.1

Type RM Length L Ch R = 1 ,53618   ,212.3,225.7,238.6
XS GIS Cut Line= 2
2260613.83447475519460.3767539882261207.85059408519446.664725312
#Sta/Elev= 30
       0 4058.81    27.8 4056.99    38.4 4054.26    46.4 4053.58    54.4 4050.87
    62.4 4050.33    70.4 4048.69   113.8 4037.46   154.4 4033.03   170.4 4029.14
   190.4 4027.55   210.4 4028.04   234.4 4026.49   246.4 4026.93   258.4  4025.5
   266.4 4026.09   281.7  4024.6   298.1 4023.94   304.24024.566   322.4 4031.04
   334.4 4032.27   354.4 4032.93   366.4 4031.69   406.4 4034.14   426.5 4033.81
   474.5 4037.25   534.5 4040.25   550.5 4042.75   570.5 4047.59   594.2  4056.7
#Mann= 8 ,-1,0
       0     .12       0      70      .1       0     170     .12       0
     270      .1       0   281.7    .045       0   304.2      .1       0
     360     .12       0     560      .1       0
Bank Sta=281.7,304.2
XS Rating Curve= 0 ,0
Exp/Cntr(USF)=0,0
Exp/Cntr=0.3,0.1

Type RM Length L Ch R = 1 ,53393   ,219.5,207.5,195.3
XS GIS Cut Line= 3
2260617.46347137519516.4424258712260847.28817805519670.628621487
2261101.84085949519656.082753976
#Sta/Elev= 30
       0 4058.97    22.5 4058.56    27.3 4057.97    42.8 4054.08    51.5 4052.74
    60.1 4050.41    77.4  4047.3   100.5 4041.05   147.8 4025.25   158.2 4023.23
   163.9 4022.22   171.9  4021.9   175.5 4022.14   179.4 4023.24   191.1  4028.4
   205.6 4030.89   238.9 4033.37   247.5  4033.4   281.6 4035.34   313.7 4036.55
   345.8 4038.27   357.8  4038.4   382.4 4040.05   433.9 4042.25   445.7 4043.43
   457.9 4043.95     490    4047     514 4048.38     522 4049.42   531.7 4049.99
#Mann= 5 ,-1,0
       0     .06       0      80     .12       0   158.2    .045       0
   179.4     .12       0  506.75      .1       0
Bank Sta=158.2,179.4
XS Rating Curve= 0 ,0
Exp/Cntr(USF)=0,0
Exp/Cntr=0.3,0.1

Type RM Length L Ch R = 1 ,53185   ,111.3,109,106.7
XS GIS Cut Line= 2
2260540.37037356519805.9051893392261007.29272067519782.631801321
#Sta/Elev= 30
       0  4070.9    15.8 4068.67    23.8 4066.27    31.8 4064.68    55.9 4054.22
    63.9 4053.47    83.9  4053.1    87.9 4051.99    91.8  4050.3    95.9 4046.98
    99.9 4042.11   103.9 4038.25   115.9 4028.59     124 4023.15   130.2 4020.84
     140 4019.94   146.6 4020.64     156 4022.67     168 4022.93     180 4025.69
     196 4026.38   208.1 4025.21   229.4 4024.53   263.7 4029.97   276.1  4031.4
   284.2 4031.35   312.2 4033.32     340 4034.44   396.3 4035.96   467.5 4040.39
#Mann= 7 ,-1,0
       0      .1       0      40     .06       0   130.2    .045       0
   146.6      .1       0     190     .06       0     240      .1       0
     340     .12       0
#XS Ineff= 2 , 0
                          192.07         4028.29
Permanent Ineff=
       F       F
Bank Sta=130.2,146.6
XS Rating Curve= 0 ,0
Exp/Cntr(USF)=0,0
Exp/Cntr=0.3,0.1