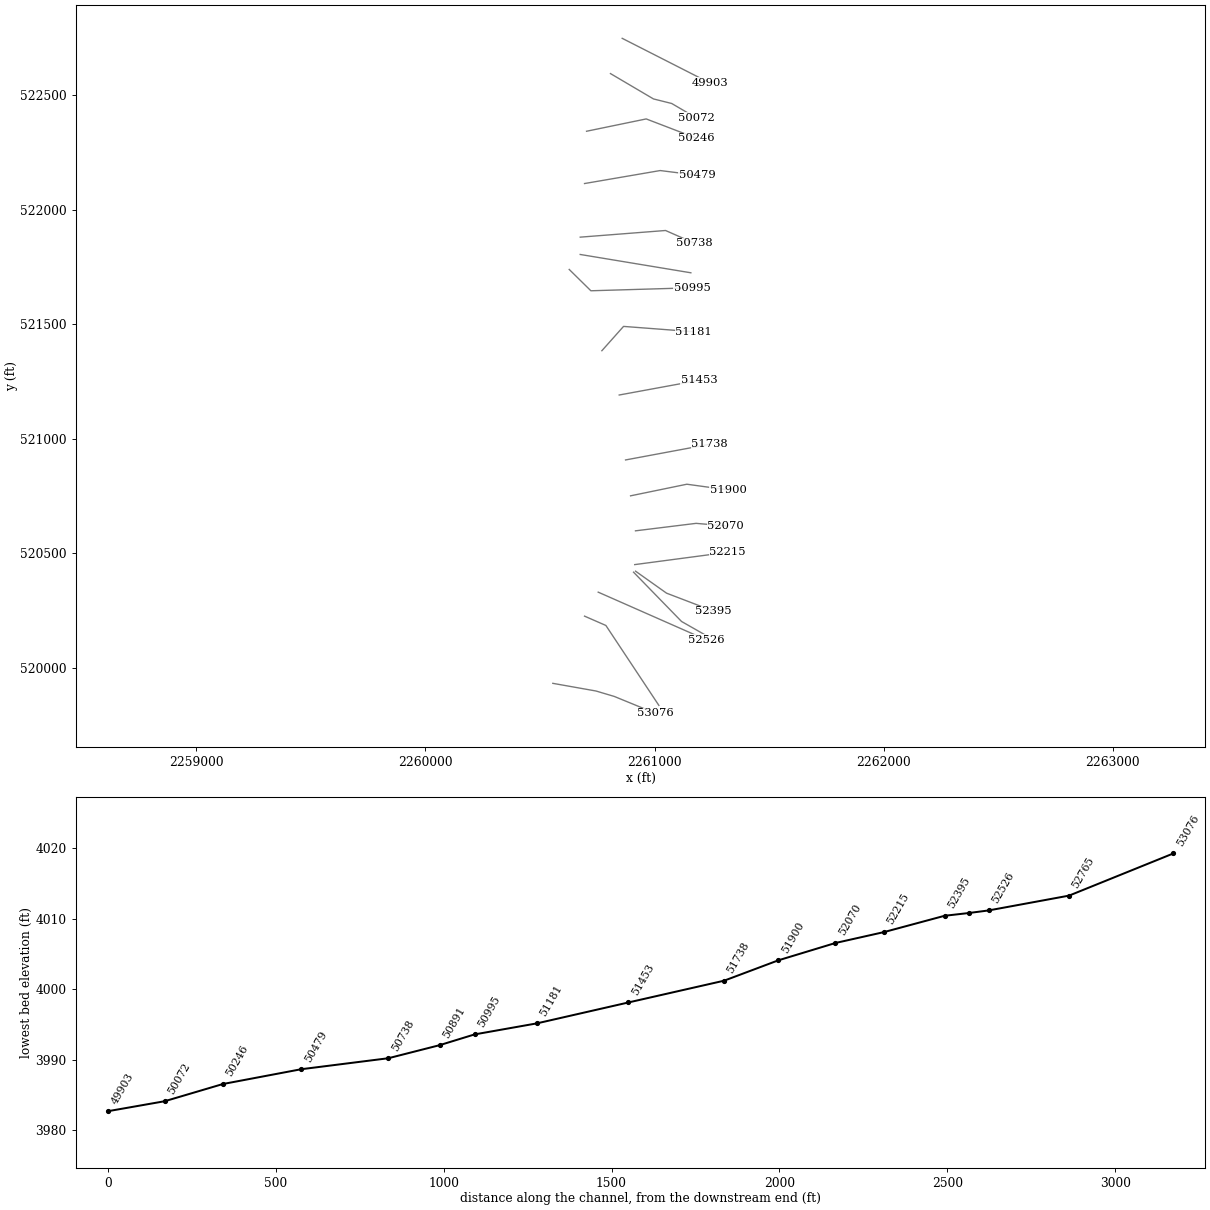
HEC-RAS study SHVRSFK.prj: SHVRSFK

--- SHVRSFK.g01 (geometry) --- (continued)

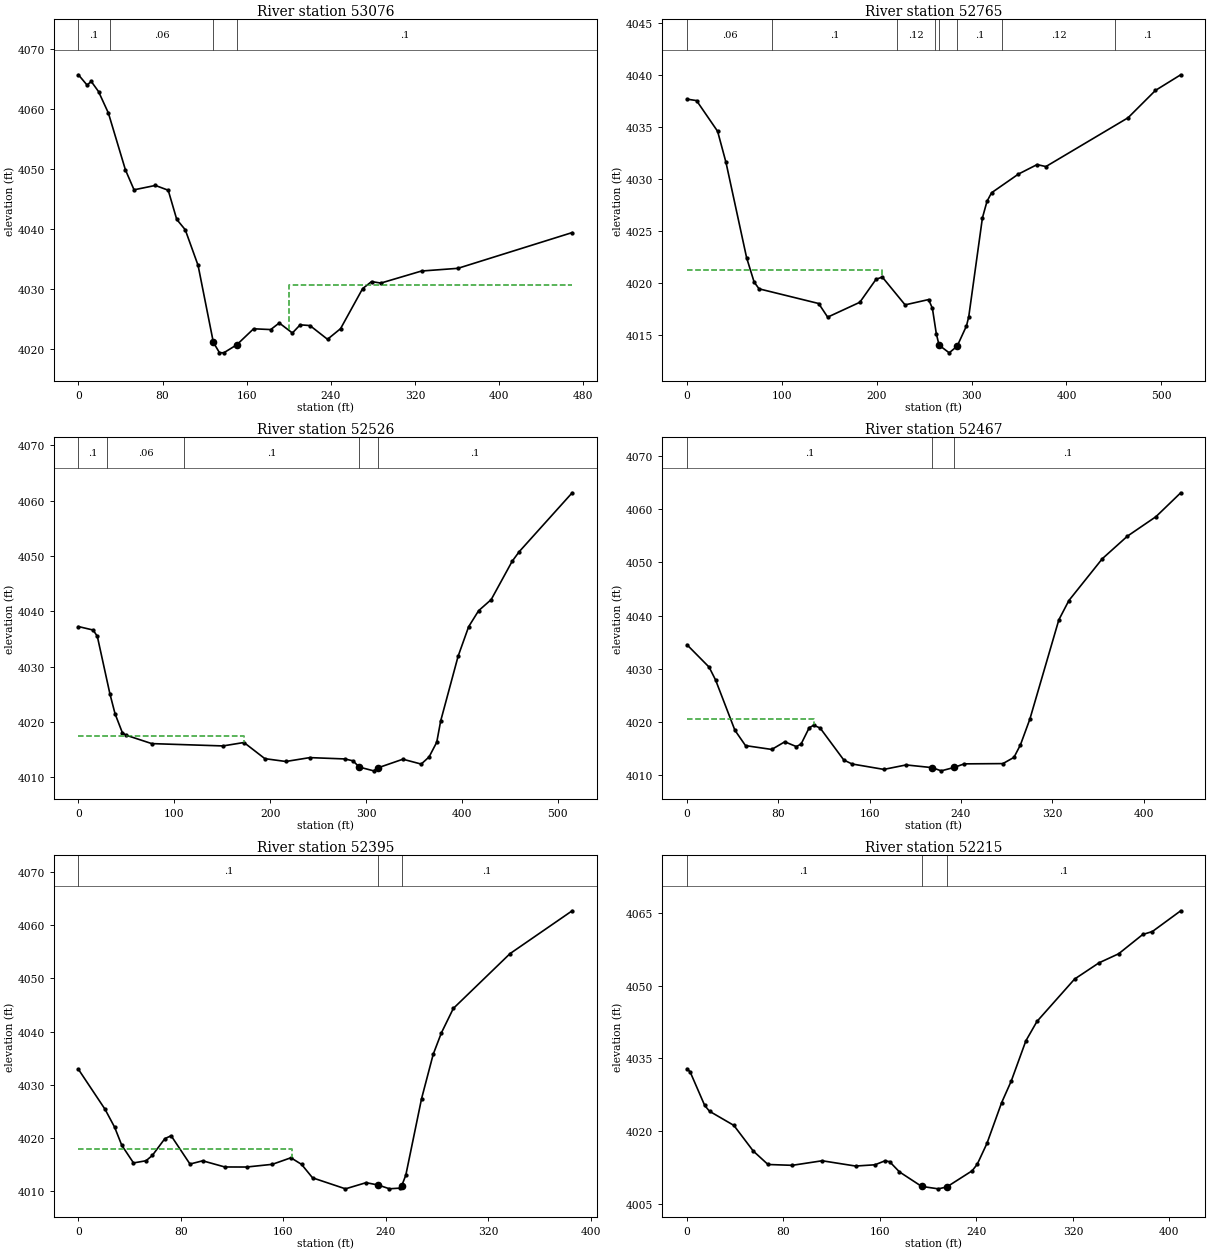
Type RM Length L Ch R = 1 ,53076   ,314.6,310.9,287.2
XS GIS Cut Line= 4
 2260556.1225441519931.3194020752260744.51279759519897.828791163
2260824.35518865519874.0818229162261004.73841495519800.123195108
#Sta/Elev= 30
       0 4065.64     8.2 4063.93    12.2 4064.53    19.1 4062.85    28.5 4059.26
    44.7 4049.79    52.9 4046.46    73.2 4047.19    85.4 4046.39    93.5 4041.53
   101.6  4039.8   113.8 4033.86  128.34 4021.02   134.1 4019.32   138.2 4019.28
   150.6 4020.62   166.6 4023.29   182.9 4023.16     191 4024.26   203.5 4022.59
   210.9 4023.95   220.2 4023.83   236.9 4021.54   249.3 4023.31   270.3 4029.99
   278.8 4031.16   287.6 4030.91   326.3 4032.92   360.9 4033.37   469.6 4039.33
#Mann= 4 ,-1,0
       0      .1       0      30     .06       0  128.34    .045       0
   150.6      .1       0
#XS Ineff= 2 , 0
                             200         4030.63
Permanent Ineff=
       F       F
Bank Sta=128.34,150.6
XS Rating Curve= 0 ,0
Exp/Cntr(USF)=0,0
Exp/Cntr=0.3,0.1

Type RM Length L Ch R = 1 ,52765   ,226,239.4,248.7
XS GIS Cut Line= 3
2260694.55656918520224.8261736532260787.65012125520184.097744623
2261018.92941467519834.996924361
#Sta/Elev= 30
       0 4037.67    10.1 4037.53    32.3 4034.58    41.1  4031.6    62.9 4022.42
    70.8 4020.09      76 4019.44   138.8 4018.03   148.3 4016.72   182.2 4018.15
   199.3 4020.36   205.9 4020.57   229.9  4017.9   254.7 4018.41   258.7 4017.56
   262.8 4015.13   265.7 4014.03   276.4 4013.29   284.84013.936   294.6 4015.88
     297 4016.77   311.4 4026.26   316.2 4027.84     321 4028.67   349.4 4030.47
     369 4031.38   378.3 4031.19   464.9 4035.88   493.8 4038.51   520.4 4040.01
#Mann= 8 ,-1,0
       0     .06       0      90      .1       0  221.61     .12       0
  261.61      .1       0   265.7    .045       0   284.8      .1       0
  331.61     .12       0  451.61      .1       0
#XS Ineff= 2 , 0
          205.85 4021.21
Permanent Ineff=
       F       F
Bank Sta=265.7,284.8
XS Rating Curve= 0 ,0
Exp/Cntr(USF)=0,0
Exp/Cntr=0.3,0.1

Type RM Length L Ch R = 1 ,52526   ,67.3,59.4,52.3
XS GIS Cut Line= 2
2260754.19462598520329.5564197322261225.48073333520121.550514326
#Sta/Elev= 30
       0 4037.26    15.3 4036.63    19.7 4035.51    32.8 4025.14    38.2 4021.51
    45.9 4018.05    50.1 4017.61    76.5 4016.11   150.8 4015.69   172.7 4016.31
   194.5 4013.39   216.4 4012.88   241.4 4013.58   277.8 4013.34   286.4    4013
     293 4011.87     308 4011.19   312.6 4011.74   338.5 4013.29   357.6 4012.41
   365.8  4013.7   373.8 4016.36   377.9  4020.2   396.1  4031.9   407.1 4037.24
   417.5 4040.13   430.6 4042.13   452.5 4049.06   459.8 4050.78   515.1 4061.43
#Mann= 5 ,-1,0
       0      .1       0      30     .06       0     110      .1       0
     293    .045       0   312.6      .1       0
#XS Ineff= 2 , 0
          172.86 4017.43
Permanent Ineff=
       F       F
Bank Sta=293,312.6
XS Rating Curve= 0 ,0
Exp/Cntr(USF)=0,0
Exp/Cntr=0.3,0.1

Type RM Length L Ch R = 1 ,52467   ,65.6,71.8,81.7
XS GIS Cut Line= 3
2260908.38082159520416.8316247982261117.84131375520201.552785636
2261232.75366709520136.096381837
#Sta/Elev= 30
       0 4034.52    19.4 4030.31    25.1 4027.88      42 4018.45    51.3 4015.56
    74.3 4014.84    85.7 4016.28    95.8 4015.38     100 4015.86   107.1 4018.92
   111.1 4019.39   116.7 4018.86   137.4 4012.86   144.6 4012.11   172.5 4011.09
     192 4011.93   214.6 4011.43   222.8 4010.82   233.9 4011.45   242.9 4012.13
   276.8 4012.18   286.5 4013.35   292.2 4015.72   300.4 4020.52   325.8 4039.19
   334.6 4042.82   363.9 4050.68   385.9 4054.92   410.9 4058.58   432.6 4063.07
#Mann= 3 ,-1,0
       0      .1       0   214.6    .045       0   233.9      .1       0
#XS Ineff= 2 , 0
             111  4020.6
Permanent Ineff=
       F       F
Bank Sta=214.6,233.9
XS Rating Curve= 0 ,0
Exp/Cntr(USF)=0,0
Exp/Cntr=0.3,0.1

Type RM Length L Ch R = 1 ,52395   ,172,180.1,190.8
XS GIS Cut Line= 3
 2260917.1083421520421.1953850512261052.38490995520325.192659479
2261257.48164185 520246.64497492
#Sta/Elev= 30
       0  4032.9    20.8 4025.38    28.3    4022    33.8 4018.64      43  4015.3
    52.8 4015.71    57.7 4016.71    67.5 4019.87    72.4 4020.41    87.1 4015.09
      97  4015.7   114.3 4014.54   131.3 4014.53   151.4 4015.04   165.9 4016.27
   174.2 4015.03   182.8  4012.5   208.5 4010.43   224.6 4011.59   234.2 4011.14
   242.8 4010.44   251.3 4010.57   252.4    4011   255.6    4013   267.9 4027.38
     277 4035.73   283.4 4039.76   292.7 4044.34     337 4054.65   385.5  4062.7
#Mann= 3 ,-1,0
       0      .1       0   234.2    .045       0   252.4      .1       0
#XS Ineff= 2 , 0
          166.74 4017.98
Permanent Ineff=
       F       F
Bank Sta=234.2,252.4
XS Rating Curve= 0 ,0
Exp/Cntr(USF)=0,0
Exp/Cntr=0.3,0.1

Type RM Length L Ch R = 1 ,52215   ,144.9,144.9,144.5
XS GIS Cut Line= 2
 2260913.5888084520449.9221645792261319.41851195520503.741874369
#Sta/Elev= 30
       0 4032.87     2.6 4032.26    14.7 4025.32    18.7 4024.12    38.9  4021.2
      55 4015.91    67.2 4013.14    87.3 4012.97   112.1 4013.91   139.8 4012.82
   155.9 4013.08     164 4013.88     168 4013.73   176.2 4011.61   194.6 4008.62
   208.4 4008.12   215.4  4008.5   236.5 4011.85   240.7  4013.2   248.7 4017.47
   260.9 4025.89   268.9 4030.36     281 4038.64   290.2 4042.64   321.4 4051.38
   341.6 4054.72   357.9 4056.59   377.9 4060.57   385.9 4061.18   409.4 4065.46
#Mann= 3 ,0,0
       0      .1       0   194.6    .045       0   215.4      .1       0
Bank Sta=194.6,215.4
XS Rating Curve= 0 ,0
Exp/Cntr(USF)=0,0
Exp/Cntr=0.3,0.1

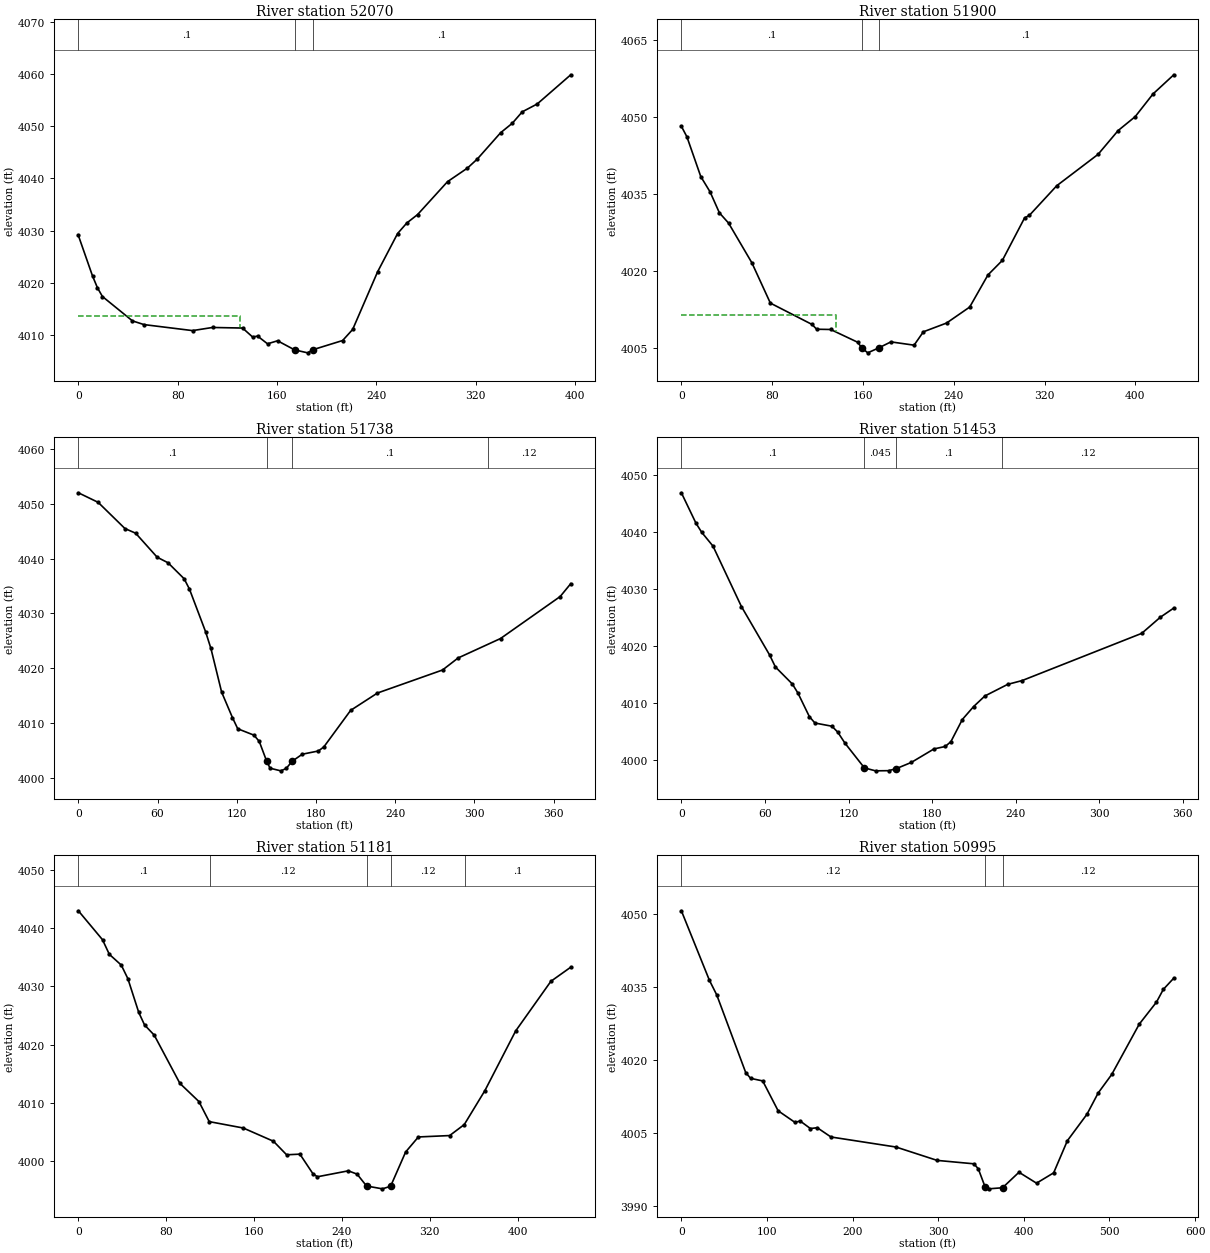
Type RM Length L Ch R = 1 ,52070   ,169.1,170.1,171.9
XS GIS Cut Line= 3
 2260916.8761009520597.4447420992261181.42313155520630.083661463
2261311.11989008520618.917715365
#Sta/Elev= 30
       0 4029.06    11.4 4021.31    15.4 4019.02    19.4 4017.36    43.6 4012.69
    52.9 4011.98      92 4010.83   108.1 4011.43   132.3 4011.32   140.4  4009.6
   144.4 4009.78   152.4  4008.3   160.5 4008.88   174.2 4007.14   184.7 4006.57
   188.7 4007.15   212.9 4008.93     221 4011.05   241.1  4022.1   257.2 4029.43
   264.6 4031.44   273.3 4033.06   297.4 4039.36   313.5 4041.97   321.5 4043.72
   340.2 4048.74   349.6 4050.55   357.6 4052.74   369.7 4054.25   396.7 4059.84
#Mann= 3 ,-1,0
       0      .1       0   174.2    .045       0   188.7      .1       0
#XS Ineff= 2 , 0
          129.99 4013.69
Permanent Ineff=
       F       F
Bank Sta=174.2,188.7
XS Rating Curve= 0 ,0
Exp/Cntr(USF)=0,0
Exp/Cntr=0.3,0.1

Type RM Length L Ch R = 1 ,51900   ,161.5,161.5,161
XS GIS Cut Line= 3
2260895.40312764520750.3323117552261141.05394181520801.008528664
2261322.28583617520776.099879675
#Sta/Elev= 30
       0 4048.16     4.9  4046.1    17.1 4038.38    25.3  4035.4    33.5 4031.33
    41.6 4029.33    62.1 4021.62    78.4 4013.78   115.1 4009.63   119.2  4008.7
   131.5 4008.65   155.4 4006.16   158.8  4005.1   164.2 4004.11   173.74005.054
   184.6 4006.24     205  4005.6   213.2  4008.2   233.6  4009.9     254 4013.01
   270.1 4019.26   282.8 4022.09   302.4 4030.36   306.5 4030.82   330.7  4036.6
   367.1  4042.7   384.8 4047.33   399.8 4050.03   415.5 4054.44   433.8 4058.17
#Mann= 3 ,-1,0
       0      .1       0   158.8    .045       0   173.7      .1       0
#XS Ineff= 2 , 0
          136.05 4011.51
Permanent Ineff=
       F       F
Bank Sta=158.8,173.7
XS Rating Curve= 0 ,0
Exp/Cntr(USF)=0,0
Exp/Cntr=0.3,0.1

Type RM Length L Ch R = 1 ,51738   ,285.1,285.1,285.1
XS GIS Cut Line= 2
2260873.47073957520907.0273599162261240.02660084520975.392937217
#Sta/Elev= 30
       0 4052.04      15 4050.29    35.3  4045.5    43.4 4044.65    59.7 4040.26
    67.9 4039.25    80.1 4036.33    84.1 4034.46    96.3 4026.68   100.4 4023.58
   108.5 4015.61   116.7 4010.95   120.7 4008.91     133 4007.74     137  4006.6
   142.6 4002.99   145.2  4001.7   153.3 4001.22   157.4 4001.65   161.9 4002.97
   169.6 4004.26   181.8 4004.85   185.9 4005.59   206.2 4012.27   226.5 4015.44
   275.8 4019.65   287.6 4021.85   319.7  4025.4   364.9 4033.08   372.9 4035.43
#Mann= 4 ,-1,0
       0      .1       0   142.6    .045       0   161.9      .1       0
     310     .12       0
Bank Sta=142.6,161.9
XS Rating Curve= 0 ,0
Exp/Cntr(USF)=0,0
Exp/Cntr=0.3,0.1

Type RM Length L Ch R = 1 ,51453   ,275.4,271.9,263.8
XS GIS Cut Line= 2
2260845.83359129521190.6717763792261193.47982481521254.673593427
#Sta/Elev= 30
       0 4046.93    10.5 4041.58    14.6 4039.99    22.7 4037.57    43.1 4026.97
    63.4 4018.44    67.5 4016.36    79.7 4013.36    83.7 4011.77    91.9 4007.64
    95.9 4006.52   108.1 4005.96   112.2 4004.94   117.5 4002.97   131.43998.646
   139.4 3998.13   148.8 3998.16   154.3 3998.52   165.1 3999.61   181.3 4001.97
   189.5 4002.41   193.5 4003.26   201.7 4007.14   209.8 4009.41   217.9 4011.27
   234.3 4013.31   244.6 4013.97   330.5 4022.26   343.8 4025.08   353.5  4026.7
#Mann= 4 ,-1,0
       0      .1       0   131.4    .045       0   154.3      .1       0
     230     .12       0
Bank Sta=131.4,154.3
XS Rating Curve= 0 ,0
Exp/Cntr(USF)=0,0
Exp/Cntr=0.3,0.1

Type RM Length L Ch R = 1 ,51181   ,185.1,185.8,189.3
XS GIS Cut Line= 3
2260770.19508024521384.1318142742260864.74321906521490.316647104
2261170.20643679521467.043259086
#Sta/Elev= 30
       0 4043.03      22 4038.05    28.2 4035.54    39.1 4033.68    45.1 4031.35
      55 4025.54    60.3 4023.38    69.1 4021.63    92.5 4013.32   109.8  4010.2
   119.2 4006.74   150.2 4005.64   177.7 4003.36   189.7 4001.03   201.8 4001.14
   213.8 3997.73   217.8 3997.25   245.9 3998.27   253.9  3997.7   262.5 3995.66
   276.9 3995.17   284.4 3995.61   298.1 4001.51   309.7  4004.1   338.2 4004.34
   351.5 4006.23   370.3 4012.08   398.3 4022.34   430.4 4030.89   448.5 4033.32
#Mann= 5 ,-1,0
       0      .1       0     120     .12       0   262.5    .045       0
   284.4     .12       0  352.18      .1       0
Bank Sta=262.5,284.4
XS Rating Curve= 0 ,0
Exp/Cntr(USF)=0,0
Exp/Cntr=0.3,0.1

Type RM Length L Ch R = 1 ,50995   ,108.2,104.5,100.3
XS GIS Cut Line= 3
2260627.64557863521739.0509815412260722.19371745521645.957429471
2261164.38808978521659.048710231
#Sta/Elev= 30
       0  4050.6    32.8 4036.33    41.3 4033.36    75.2 4017.41    80.9 4016.25
      95 4015.72     113  4009.6   132.7 4007.22   138.7 4007.51   150.7 4005.96
   158.7 4006.13   174.7 4004.23   250.7 4002.17   298.7 3999.43   341.7 3998.73
   346.8  3997.7   354.8 3993.96   358.8  3993.6   375.13993.822   394.3    3997
   414.8 3994.76   434.8 3996.88   450.8 4003.46   473.7 4008.89   486.8 4013.25
   502.6 4017.04   534.8 4027.37   554.9 4031.88   562.9 4034.49   575.1 4036.79
#Mann= 3 ,-1,0
       0     .12       0   354.8    .045       0   375.1     .12       0
Bank Sta=354.8,375.1
XS Rating Curve= 0 ,0
Exp/Cntr(USF)=0,0
Exp/Cntr=0.3,0.1

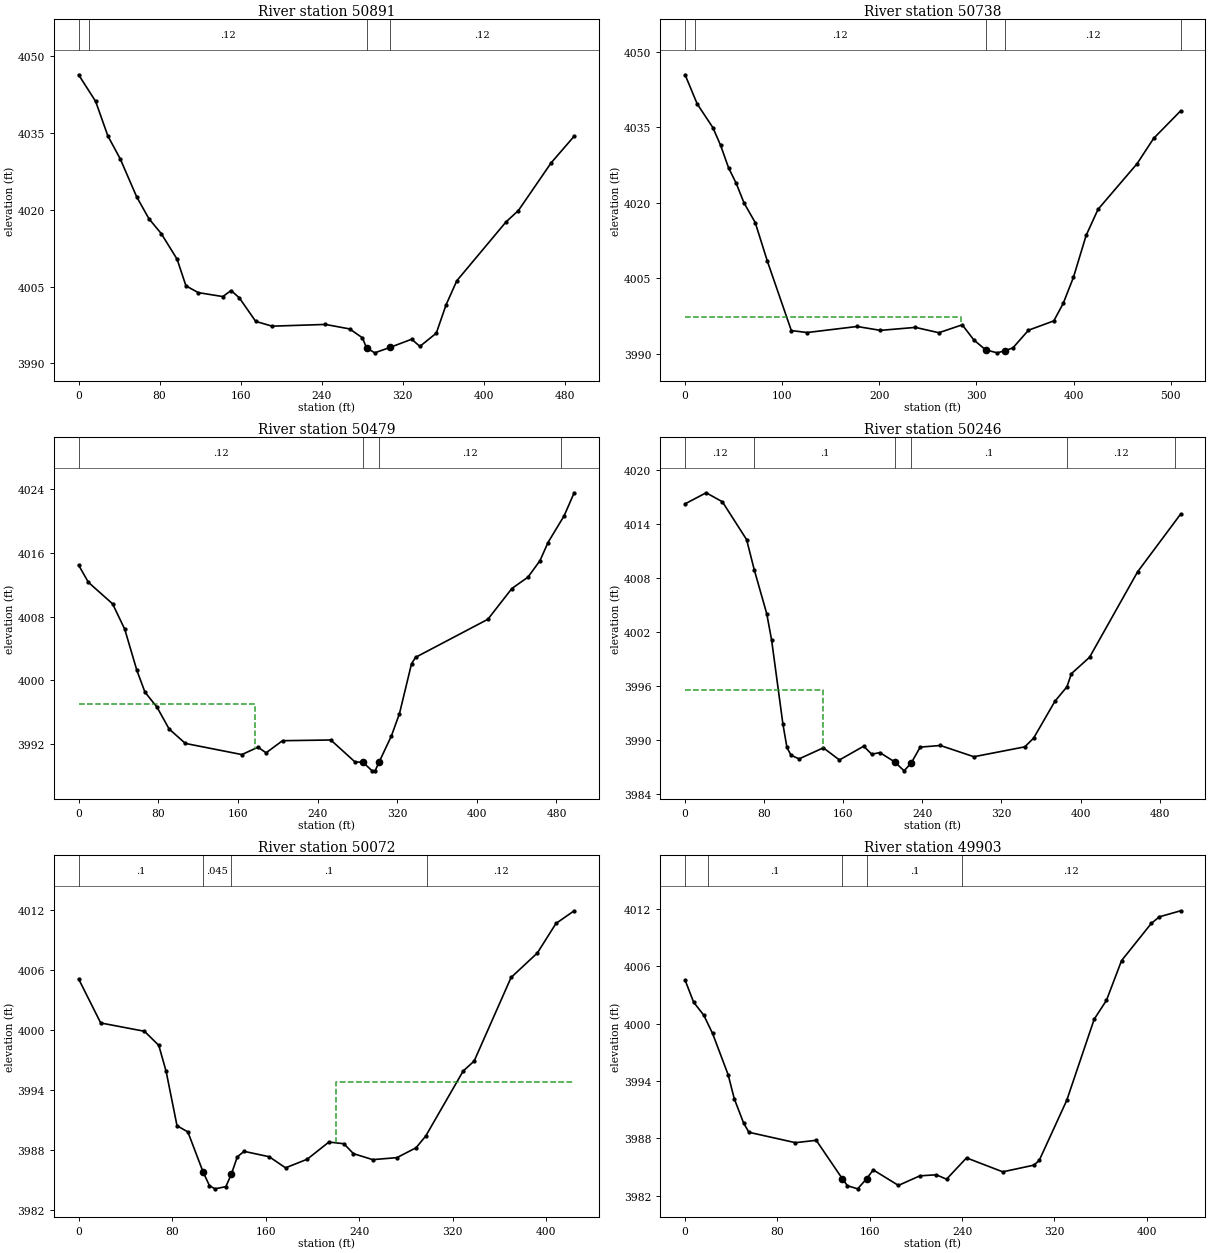
Type RM Length L Ch R = 1 ,50891   ,147.8,152.4,157.5
XS GIS Cut Line= 2
2260675.64694142 521804.507385342261158.56974278 521724.50511403
#Sta/Elev= 30
       0 4046.39    16.8 4041.19    28.9 4034.43    41.1 4029.96    57.3 4022.56
    69.5 4018.25    81.6 4015.37    97.3 4010.35     106 4005.16   118.1 4003.84
   142.4 4003.06   150.6 4004.24   158.7 4002.82   174.9 3998.22   191.1 3997.28
   243.8 3997.62   267.7 3996.74   280.3 3995.01   284.4 3993.03   292.5 3992.07
   307.6 3993.13     329 3994.73   337.1 3993.33   353.3 3995.91     363 4001.47
   373.6 4006.16   422.2 4017.65   434.4 4019.87   466.8  4029.2   489.5 4034.39
#Mann= 4 ,-1,0
       0      .1       0      10     .12       0   284.4    .045       0
   307.6     .12       0
Bank Sta=284.4,307.6
XS Rating Curve= 0 ,0
Exp/Cntr(USF)=0,0
Exp/Cntr=0.3,0.1

Type RM Length L Ch R = 1 ,50738   ,258.2,259.5,261.2
XS GIS Cut Line= 3
2260675.64694142521880.145896397 2261048.0211497521909.237631419
2261173.11561029521853.963334877
#Sta/Elev= 30
       0  4045.4    12.5  4039.6    28.6 4034.92    36.6 4031.38    44.7 4026.97
    52.7 4023.83    60.7 4019.96    72.2 4016.08    84.8 4008.36   109.4 3994.64
   125.7 3994.25   177.1 3995.45   201.1 3994.68   237.2 3995.27   261.3 3994.21
   285.4 3995.78   297.4 3992.77   309.5 3990.81   321.4 3990.22   329.8 3990.66
   337.6 3991.21   353.6 3994.71   379.7 3996.56   389.4 4000.04   399.9  4005.2
     413 4013.53   425.2 4018.69   465.5 4027.77   482.5 4032.78   510.3 4038.24
#Mann= 5 ,-1,0
       0      .1       0      10     .12       0   309.5    .045       0
   329.8     .12       0  510.27      .1       0
#XS Ineff= 2 , 0
          283.92 3997.34
Permanent Ineff=
       F       F
Bank Sta=309.5,329.8
XS Rating Curve= 0 ,0
Exp/Cntr(USF)=0,0
Exp/Cntr=0.3,0.1

Type RM Length L Ch R = 1 ,50479   ,232.8,233.3,233.8
XS GIS Cut Line= 3
2260694.55656918522114.3343633232261024.74776168522171.063246615
2261186.20689105  522150.6990321
#Sta/Elev= 30
       0 4014.46     9.8 4012.31    34.1 4009.61    46.3 4006.43    58.5 4001.26
    66.6 3998.54    78.8 3996.63    90.9 3993.91   107.2  3992.1     164  3990.7
   180.2 3991.63   188.3 3990.92   204.8 3992.44   253.3 3992.53   277.6 3989.78
   285.7 3989.73   294.8 3988.66   297.9 3988.68   301.7 3989.72   314.2 3993.04
   322.3 3995.84   334.4 4002.09   338.5  4002.9   411.1 4007.67   435.2 4011.53
   451.4 4012.96   463.5 4015.03   471.5  4017.3   487.7 4020.65   497.8 4023.54
#Mann= 4 ,-1,0
       0     .12       0   285.7    .045       0   301.7     .12       0
  485.03      .1       0
#XS Ineff= 2 , 0
          177.11 3997.08
Permanent Ineff=
       F       F
Bank Sta=285.7,301.7
XS Rating Curve= 0 ,0
Exp/Cntr(USF)=0,0
Exp/Cntr=0.3,0.1

Type RM Length L Ch R = 1 ,50246   ,181.7,173.2,154.6
XS GIS Cut Line= 3
2260703.28408969522342.7044832442260963.65511813522396.524193035
2261183.29771755522312.158161471
#Sta/Elev= 30
       0 4016.27    21.3  4017.5    37.7  4016.5    62.2 4012.29      70 4008.91
    82.6 4004.03    87.5 4001.11    98.9 3991.79     103 3989.16   107.1  3988.3
   115.3 3987.89   139.8 3989.12   156.1 3987.77   180.6  3989.3   188.8 3988.41
     197 3988.59     2123987.553   221.5 3986.56   228.83987.447   237.8  3989.2
   258.2 3989.38   292.1 3988.13   343.6 3989.23   352.5  3990.2   374.1 3994.31
   386.2 3995.91   390.7 3997.37   409.1  3999.2   457.7 4008.71   501.2 4015.13
#Mann= 6 ,-1,0
       0     .12       0      70      .1       0     212    .045       0
   228.8      .1       0  385.88     .12       0  495.88      .1       0
#XS Ineff= 2 , 0
          139.76 3995.55
Permanent Ineff=
       F       F
Bank Sta=212,228.8
XS Rating Curve= 0 ,0
Exp/Cntr(USF)=0,0
Exp/Cntr=0.3,0.1

Type RM Length L Ch R = 1 ,50072   ,168.7,169.5,170.6
XS GIS Cut Line= 4
2260807.67021098522594.5946253982260995.37178499522483.869525983
2261074.83907416522464.0027036892261182.12735493 522401.28785494
#Sta/Elev= 30
       0 4005.11    18.9 4000.71    56.3 3999.88    68.6 3998.47    74.9 3995.86
    84.2 3990.43    93.5 3989.81   106.6 3985.78     112 3984.43   116.7 3984.12
     126 3984.34130.73263985.593   135.8 3987.32   141.6 3987.87   163.1 3987.33
   177.1 3986.22   195.6 3987.08   214.2  3988.8     227 3988.63   235.2 3987.64
   251.7 3987.04   272.4 3987.24   288.8 3988.23   297.1 3989.41   329.1  3995.9
   338.5  3996.9   370.1 4005.26   392.6 4007.71   408.5 4010.66   424.1 4011.93
#Mann= 4 ,-1,0
       0      .1       0   106.6    .045       0130.7326      .1       0
  297.93     .12       0
#XS Ineff= 2 , 0
                          220.08         3994.77
Permanent Ineff=
       F       F
Bank Sta=106.6,130.7326
XS Rating Curve= 0 ,0
Exp/Cntr(USF)=0,0
Exp/Cntr=0.3,0.1

Type RM Length L Ch R = 1 ,49903   ,68.5,68.9,69.5
XS GIS Cut Line= 2
2260858.92487205522748.5341867992261241.48118759522553.619562153
#Sta/Elev= 30
       0 4004.54     7.4 4002.23    16.2 4000.87    23.8 3998.96    37.3 3994.64
    42.6 3992.13    50.8 3989.55    55.3 3988.62    95.6 3987.53   113.6 3987.78
   136.1 3983.78   140.6 3983.03   149.5  3982.7   157.2 3983.75     163 3984.68
   184.8 3983.06   203.4 3984.06   217.6 3984.17   226.5 3983.71   243.8 3985.94
   275.2 3984.48   302.2 3985.18   306.8 3985.68   330.6 3991.95   354.4 4000.45
     365 4002.42   378.1 4006.58   403.9 4010.48   410.9 4011.17   429.3  4011.8
#Mann= 5 ,-1,0
       0     .12       0      20      .1       0   136.1    .045       0
   157.2      .1       0     240     .12       0
Bank Sta=136.1,157.2
XS Rating Curve= 0 ,0
Exp/Cntr(USF)=0,0
Exp/Cntr=0.3,0.1