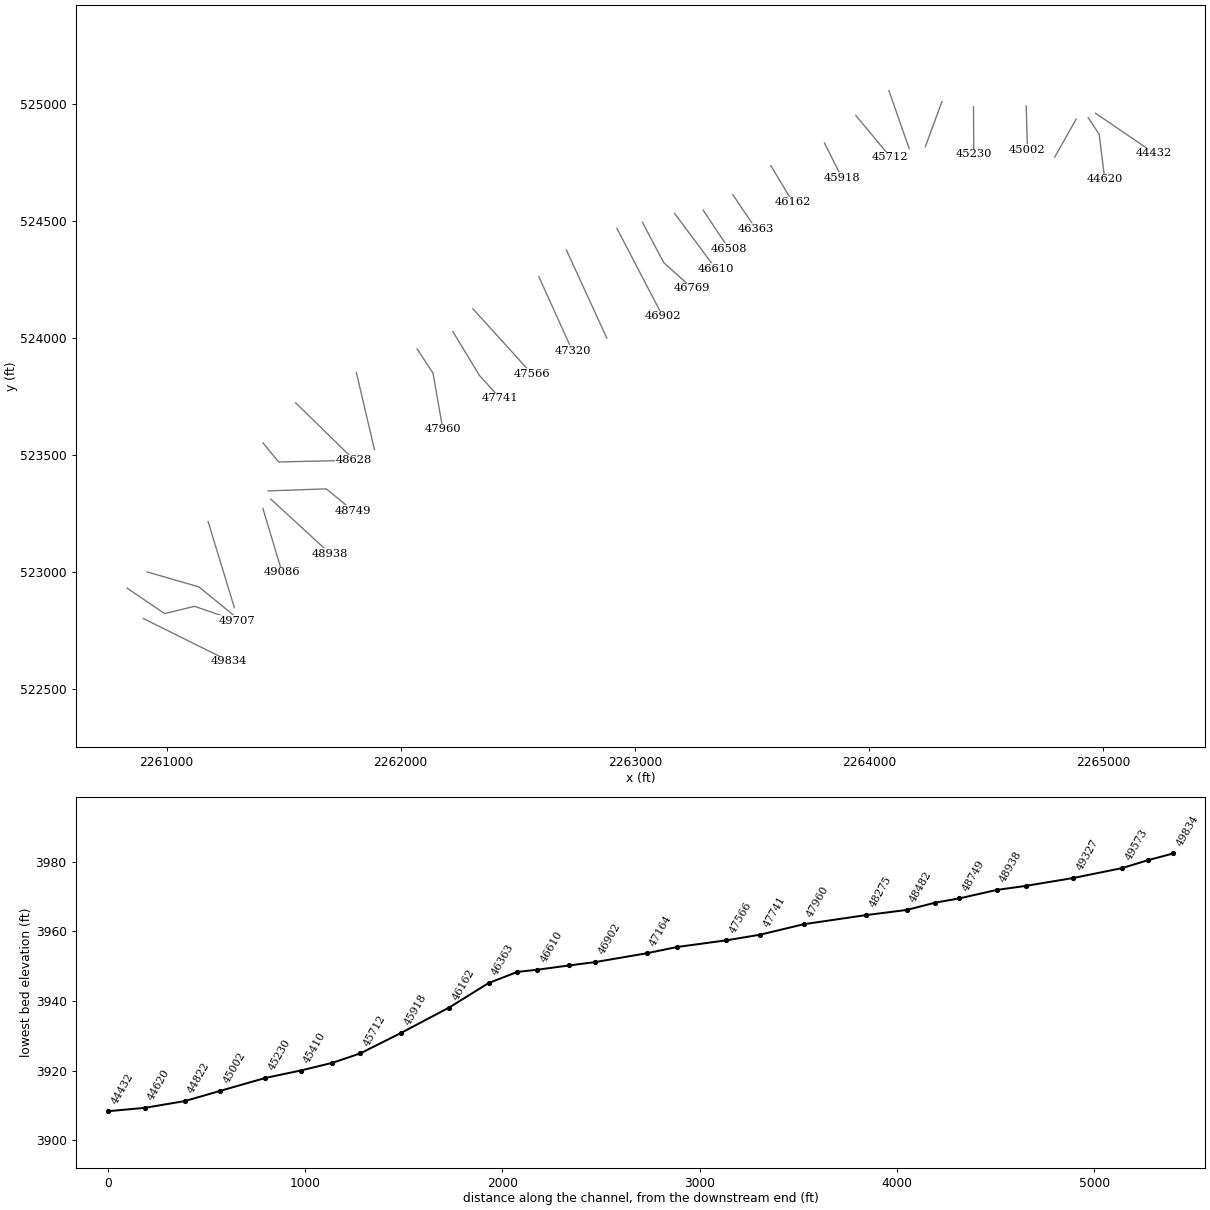
HEC-RAS study SHVRSFK.prj: SHVRSFK

--- SHVRSFK.g01 (geometry) --- (continued)

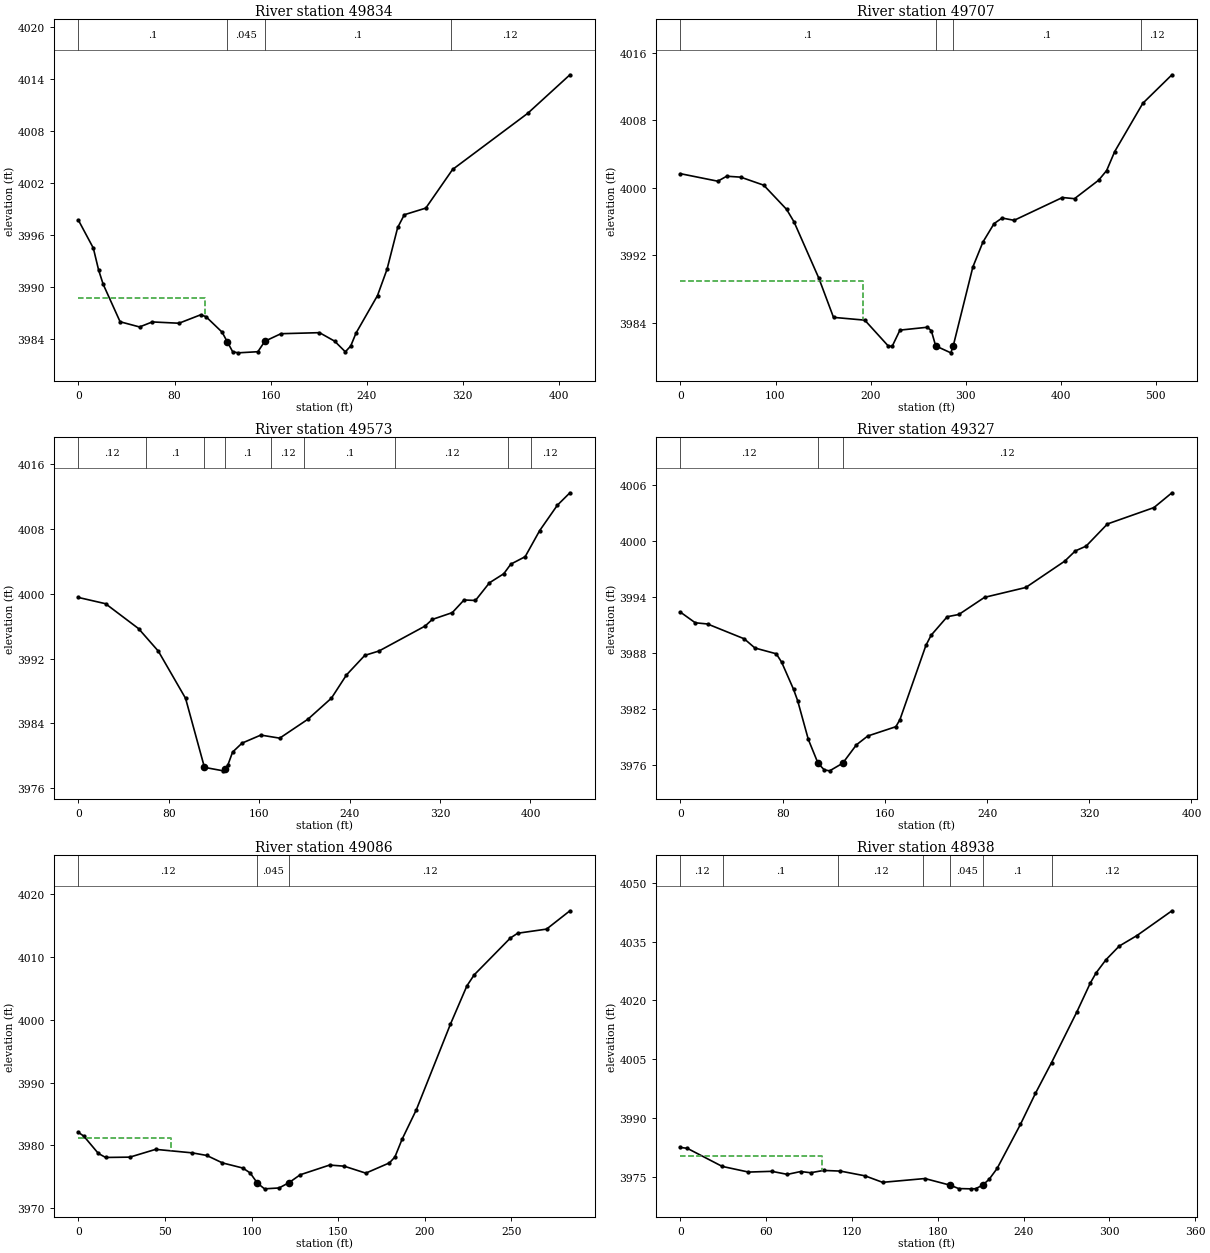
Type RM Length L Ch R = 1 ,49834   ,115.3,127.3,141
XS GIS Cut Line= 2
2260901.10788784522802.3538965892261267.66374911522620.530552703
#Sta/Elev= 30
       0 3997.71    12.4 3994.49    16.8 3991.96    20.6 3990.31    34.7 3985.98
    50.9 3985.38    61.5 3985.96    83.7 3985.81   101.7 3986.78   106.1 3986.58
   119.6 3984.78     124 3983.65   128.4 3982.52   132.9 3982.39   149.4 3982.52
   155.2 3983.73   168.6  3984.6   200.7 3984.72   213.3 3983.74   222.2 3982.51
   226.7 3983.18   231.1 3984.67     249 3989.01   256.9 3992.03   265.8 3996.87
   271.3 3998.34   289.2 3999.11   311.5 4003.57     374 4010.05   409.2 4014.51
#Mann= 4 ,-1,0
       0      .1       0     124    .045       0   155.2      .1       0
     310     .12       0
#XS Ineff= 2 , 0
          105.08 3988.67
Permanent Ineff=
       F       F
Bank Sta=124,155.2
XS Rating Curve= 0 ,0
Exp/Cntr(USF)=0,0
Exp/Cntr=0.3,0.1

Type RM Length L Ch R = 1 ,49707   ,142.7,133.7,122.8
XS GIS Cut Line= 4
2260831.68732831522932.2335050782260991.92454977522823.584554856
 2261119.2959005522854.7190196292261301.11924439522792.171789332
#Sta/Elev= 30
       0 4001.68    39.3 4000.79    48.6 4001.38    63.4 4001.27    87.6 4000.32
   111.7 3997.45   119.5 3995.97   145.6  3989.3     161 3984.67   193.9 3984.34
   218.6 3981.28   222.7 3981.24   230.9 3983.16   259.7  3983.5   263.9 3983.09
268.46813981.291   284.4 3980.47286.85263981.252   307.6 3990.64   318.2 3993.59
   329.9 3995.77   338.3 3996.43     351 3996.16   401.8 3998.86   414.5 3998.72
   439.9 4000.91   448.3 4002.05   456.8  4004.3   486.4 4010.02     517 4013.39
#Mann= 4 ,-1,0
       0      .1       0268.4681    .045       0286.8526      .1       0
  484.72     .12       0
#XS Ineff= 2 , 0
          192.17 3988.97
Permanent Ineff=
       F       F
Bank Sta=268.4681,286.8526
XS Rating Curve= 0 ,0
Exp/Cntr(USF)=0,0
Exp/Cntr=0.3,0.1

Type RM Length L Ch R = 1 ,49573   ,262.4,246.5,224.1
XS GIS Cut Line= 3
 2260917.1083421523001.6322814892261138.20552826522937.630464441
2261296.75548413522808.172243594
#Sta/Elev= 30
       0 3999.54      24 3998.77    53.2  3995.7    70.7 3992.92    94.8  3987.1
   111.5 3978.59   128.1 3978.16   129.43978.362   132.3  3978.9   136.4 3980.47
   144.8 3981.58   161.4 3982.57   178.1 3982.19   203.1 3984.53   223.9 3987.13
   237.2 3989.99   253.4  3992.4     266 3992.94   306.8 3996.02   313.1 3996.83
   330.8 3997.67   341.2 3999.23   351.3 3999.17   363.7 4001.35   376.4 4002.47
   382.6 4003.65   395.3 4004.57   408.1 4007.78   423.8 4010.92   434.9 4012.45
#Mann= 9 ,-1,0
       0     .12       0      60      .1       0   111.5    .045       0
   129.4      .1       0     170     .12       0     200      .1       0
  280.17     .12       0  380.17      .1       0  400.17     .12       0
Bank Sta=111.5,129.4
XS Rating Curve= 0 ,0
Exp/Cntr(USF)=0,0
Exp/Cntr=0.3,0.1

Type RM Length L Ch R = 1 ,49327   ,240.1,240.4,239.9
XS GIS Cut Line= 2
2261177.47937054523216.9111206512261289.48255038522848.900672624
#Sta/Elev= 30
       0 3992.37    11.6 3991.23    21.2  3991.1    49.9 3989.51    58.3 3988.52
      75  3987.9    79.2    3987    88.5 3984.09    91.7 3982.88   100.1  3978.7
   107.7 3976.14   112.6 3975.43   116.8 3975.33     127 3976.15   137.7 3978.12
   146.6 3979.07   168.6 3980.07   171.8 3980.83   192.1 3988.79   196.2 3989.89
   208.8 3991.88   217.9 3992.12     238 3993.96   270.3 3995.02   300.8 3997.85
   309.1 3998.95   317.5 3999.46   334.2 4001.84   370.6  4003.6   384.7 4005.19
#Mann= 3 ,-1,0
       0     .12       0   107.7    .045       0     127     .12       0
Bank Sta=107.7,127
XS Rating Curve= 0 ,0
Exp/Cntr(USF)=0,0
Exp/Cntr=0.3,0.1

Type RM Length L Ch R = 1 ,49086   ,138.3,148.2,161.7
XS GIS Cut Line= 2
2261411.66783747523272.1854171922261493.12469553523000.177694738
#Sta/Elev= 30
       0 3982.05     3.1 3981.46    11.5  3978.7    15.7 3978.06    29.7 3978.11
    44.6 3979.35    65.8 3978.79    74.1 3978.38    83.2 3977.19      95 3976.37
    99.2 3975.59   103.4 3973.96   107.5 3973.06   115.9  3973.2   121.7 3974.06
   128.1  3975.3   145.1 3976.85   153.5 3976.67     166 3975.56   179.6 3977.19
   182.8 3978.13   186.9 3980.93   195.2 3985.67   214.9 3999.31   224.4  4005.4
   228.6 4007.15   249.5 4013.02   253.7 4013.78   270.4 4014.44   283.9 4017.36
#Mann= 3 ,-1,0
       0     .12       0   103.4    .045       0   121.7     .12       0
#XS Ineff= 2 , 0
           53.24  3981.1
Permanent Ineff=
       F       F
Bank Sta=103.4,121.7
XS Rating Curve= 0 ,0
Exp/Cntr(USF)=0,0
Exp/Cntr=0.3,0.1

Type RM Length L Ch R = 1 ,48938   ,175.8,189.4,207.2
XS GIS Cut Line= 2
2261445.12333274523312.9138462232261698.22142743523080.179966048
#Sta/Elev= 30
       0 3982.46     4.8 3982.23    29.2 3977.62    47.6 3976.17    63.9 3976.36
    74.8 3975.58    84.1 3976.31    91.1    3976   100.1 3976.59   111.9 3976.42
   129.1 3975.21   141.4 3973.55     171 3974.52   188.9  3972.8   194.6 3971.96
     203 3971.89   206.4 3971.92   211.5 3972.84   216.1 3974.41   221.5 3977.09
   237.8 3988.33   248.3 3996.26   259.6 4004.13   277.4 4017.15   286.7 4024.43
   290.7    4027   297.6 4030.36   306.9 4033.86   319.3 4036.55   343.8 4042.88
#Mann= 7 ,-1,0
       0     .12       0      30      .1       0     110     .12       0
     170      .1       0   188.9    .045       0   211.5      .1       0
     260     .12       0
#XS Ineff= 2 , 0
           99.13 3980.15
Permanent Ineff=
       F       F
Bank Sta=188.9,211.5
XS Rating Curve= 0 ,0
Exp/Cntr(USF)=0,0
Exp/Cntr=0.3,0.1

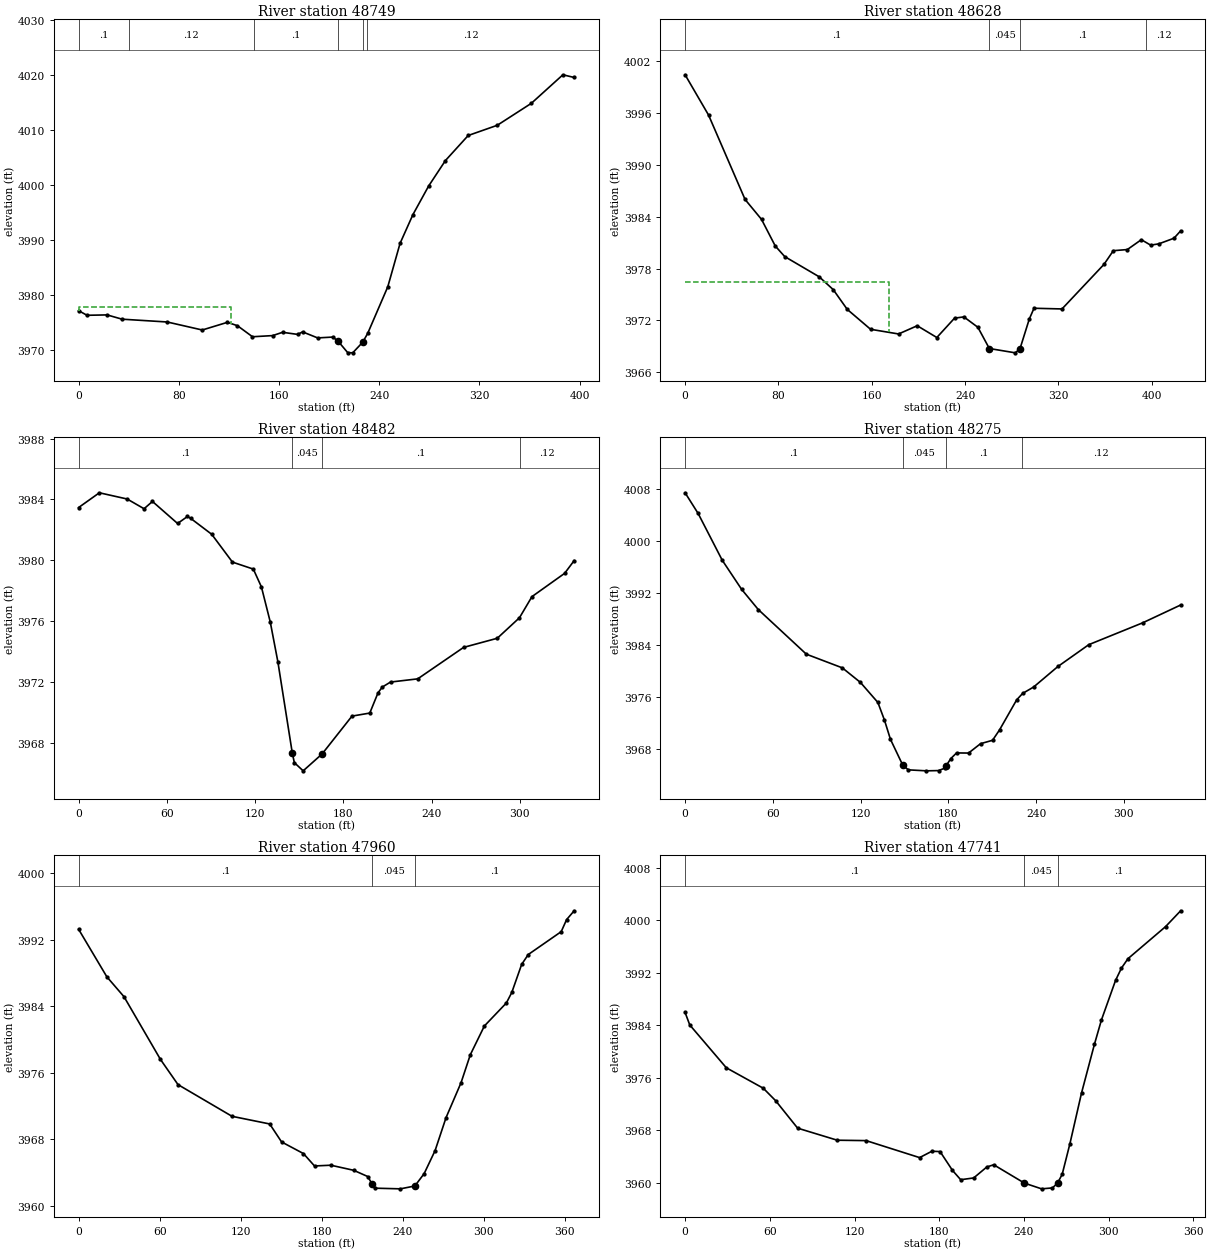
Type RM Length L Ch R = 1 ,48749   ,120.8,120.6,120.2
XS GIS Cut Line= 3
2261433.48663874523347.8239282492261682.22097317523356.551448756
2261795.67873976523263.457896686
#Sta/Elev= 30
       0 3977.14     6.7  3976.3    22.7 3976.37    34.7 3975.59    70.7 3975.08
    98.7 3973.62   118.8 3975.02   126.8  3974.4   138.8 3972.39   154.9  3972.6
   162.8  3973.2   174.8 3972.82   178.8 3973.28   190.8 3972.18   202.8 3972.33
   206.8 3971.67   214.8  3969.5   218.8 3969.46   226.8  3971.4   230.8 3973.02
   246.8 3981.49   256.6  3989.4   266.9 3994.65   279.4 3999.84   292.8 4004.48
     311 4009.05   334.2 4010.91   361.4 4014.91   386.6 4020.11   395.6 4019.62
#Mann= 6 ,-1,0
       0      .1       0      40     .12       0     140      .1       0
   206.8    .045       0   226.8      .1       0     230     .12       0
#XS Ineff= 2 , 0
          121.64 3977.87
Permanent Ineff=
       F       F
Bank Sta=206.8,226.8
XS Rating Curve= 0 ,0
Exp/Cntr(USF)=0,0
Exp/Cntr=0.3,0.1

Type RM Length L Ch R = 1 ,48628   ,161.8,146.3,129.1
XS GIS Cut Line= 3
2261411.66783747523552.9206601532261478.57882802523471.463802092
2261797.86061988523478.591277172
#Sta/Elev= 30
       0 4000.38    20.1 3995.73    51.4 3985.98    65.5 3983.68    77.3  3980.6
    85.4 3979.38     115 3977.04     127 3975.56     139 3973.28     159 3970.98
     183 3970.44     199 3971.39   215.8 3970.03     231 3972.27     239 3972.41
     251 3971.21   260.8 3968.76   283.1 3968.26   287.1 3968.74   295.1 3972.18
   299.1 3973.41   323.1 3973.33   359.1 3978.48   367.1 3980.06   379.1 3980.19
   391.1 3981.33   399.1  3980.7   406.1 3980.85   419.1  3981.5   424.8 3982.35
#Mann= 4 ,-1,0
       0      .1       0   260.8    .045       0   287.1      .1       0
  395.41     .12       0
#XS Ineff= 2 , 0
          174.67 3976.48
Permanent Ineff=
       F       F
Bank Sta=260.8,287.1
XS Rating Curve= 0 ,0
Exp/Cntr(USF)=0,0
Exp/Cntr=0.3,0.1

Type RM Length L Ch R = 1 ,48482   ,217.7,206.5,193.5
XS GIS Cut Line= 2
2261551.30816557523724.2709794322261792.18773155523488.627925755
#Sta/Elev= 30
       0 3983.46    14.1 3984.43      33 3984.02    44.5 3983.38    50.2 3983.86
    67.3 3982.41      74 3982.87    76.3 3982.74    90.5  3981.7   104.6 3979.87
   118.8 3979.41   124.3 3978.24   130.3 3975.94   135.5 3973.31   145.33967.313
   146.7 3966.68   152.7 3966.14   165.63967.253   185.9 3969.74     198 3969.94
   203.6 3971.27   206.5 3971.65   212.1 3971.98   230.6 3972.19   261.8 3974.26
   284.7 3974.86   299.8 3976.21   308.3  3977.6   330.5 3979.13     337 3979.97
#Mann= 4 ,-1,0
       0      .1       0   145.3    .045       0   165.6      .1       0
     300     .12       0
Bank Sta=145.3,165.6
XS Rating Curve= 0 ,0
Exp/Cntr(USF)=0,0
Exp/Cntr=0.3,0.1

Type RM Length L Ch R = 1 ,48275   ,316.2,315.4,313.5
XS GIS Cut Line= 2
2261810.51552462523853.874658954 2261887.7540811523523.974383807
#Sta/Elev= 30
       0 4007.35     8.9 4004.18    25.4 3996.99    38.6 3992.54      50 3989.43
    82.9 3982.57   107.5 3980.47   119.9 3978.23   131.8 3975.16   136.3 3972.45
   140.4  3969.5   148.9 3965.49   152.7 3964.81     165 3964.66   173.3  3964.7
   177.4 3965.06   178.4 3965.42   181.7 3966.55   185.6 3967.41   193.8 3967.39
     202 3968.83   210.2 3969.35     215 3970.95   226.7 3975.56   230.8 3976.55
   238.3 3977.53   254.9 3980.68     276 3984.03   312.9 3987.39   338.8 3990.12
#Mann= 4 ,-1,0
       0      .1       0   148.9    .045       0   178.4      .1       0
     230     .12       0
Bank Sta=148.9,178.4
XS Rating Curve= 0 ,0
Exp/Cntr(USF)=0,0
Exp/Cntr=0.3,0.1

Type RM Length L Ch R = 1 ,47960   ,204.5,219.1,230.4
XS GIS Cut Line= 3
2262069.72288366523954.6775208052262137.79754361523851.256402802
2262179.68964205523611.685964897
#Sta/Elev= 30
       0 3993.24    20.9 3987.53    33.6 3985.14    60.6  3977.6    73.6 3974.57
   113.6 3970.76   141.5 3969.84   150.3 3967.68   166.5 3966.28   174.7 3964.79
   186.8 3964.88   203.7 3964.27   214.1 3963.52   217.5 3962.58   219.3 3962.12
   238.3 3962.04     2493962.383   255.9 3963.87     264 3966.64   272.1  3970.6
   283.2 3974.79   290.1 3978.17   300.5 3981.62   316.8 3984.39   320.8 3985.65
   328.1 3989.02     333 3990.21   357.4 3992.96   361.4 3994.41     367 3995.47
#Mann= 3 ,-1,0
       0      .1       0   217.5    .045       0     249      .1       0
Bank Sta=217.5,249
XS Rating Curve= 0 ,0
Exp/Cntr(USF)=0,0
Exp/Cntr=0.3,0.1

Type RM Length L Ch R = 1 ,47741   ,173.9,174.5,174.9
XS GIS Cut Line= 3
2262222.89086855 524027.988693062262336.04876294523841.199801436
2262425.25754913523743.060554333
#Sta/Elev= 30
       0 3985.93     3.3 3984.03    29.2  3977.5    55.4 3974.38    64.1 3972.49
    79.7  3968.3   107.8 3966.46   128.2  3966.4   166.1 3963.81   174.8 3964.78
   180.6 3964.73   189.4 3961.86   195.2 3960.44   204.4 3960.71   213.7 3962.38
   218.6 3962.72   240.43959.917   252.5 3959.05   260.2 3959.19   263.8 3959.93
   267.1 3961.26   272.5 3965.86   280.8 3973.66   289.9 3981.05   294.9 3984.79
   304.9 3990.82   309.1  3992.7   313.7 3994.13   340.3 3999.01     351 4001.43
#Mann= 3 ,-1,0
       0      .1       0   240.4    .045       0   263.8      .1       0
Bank Sta=240.4,263.8
XS Rating Curve= 0 ,0
Exp/Cntr(USF)=0,0
Exp/Cntr=0.3,0.1

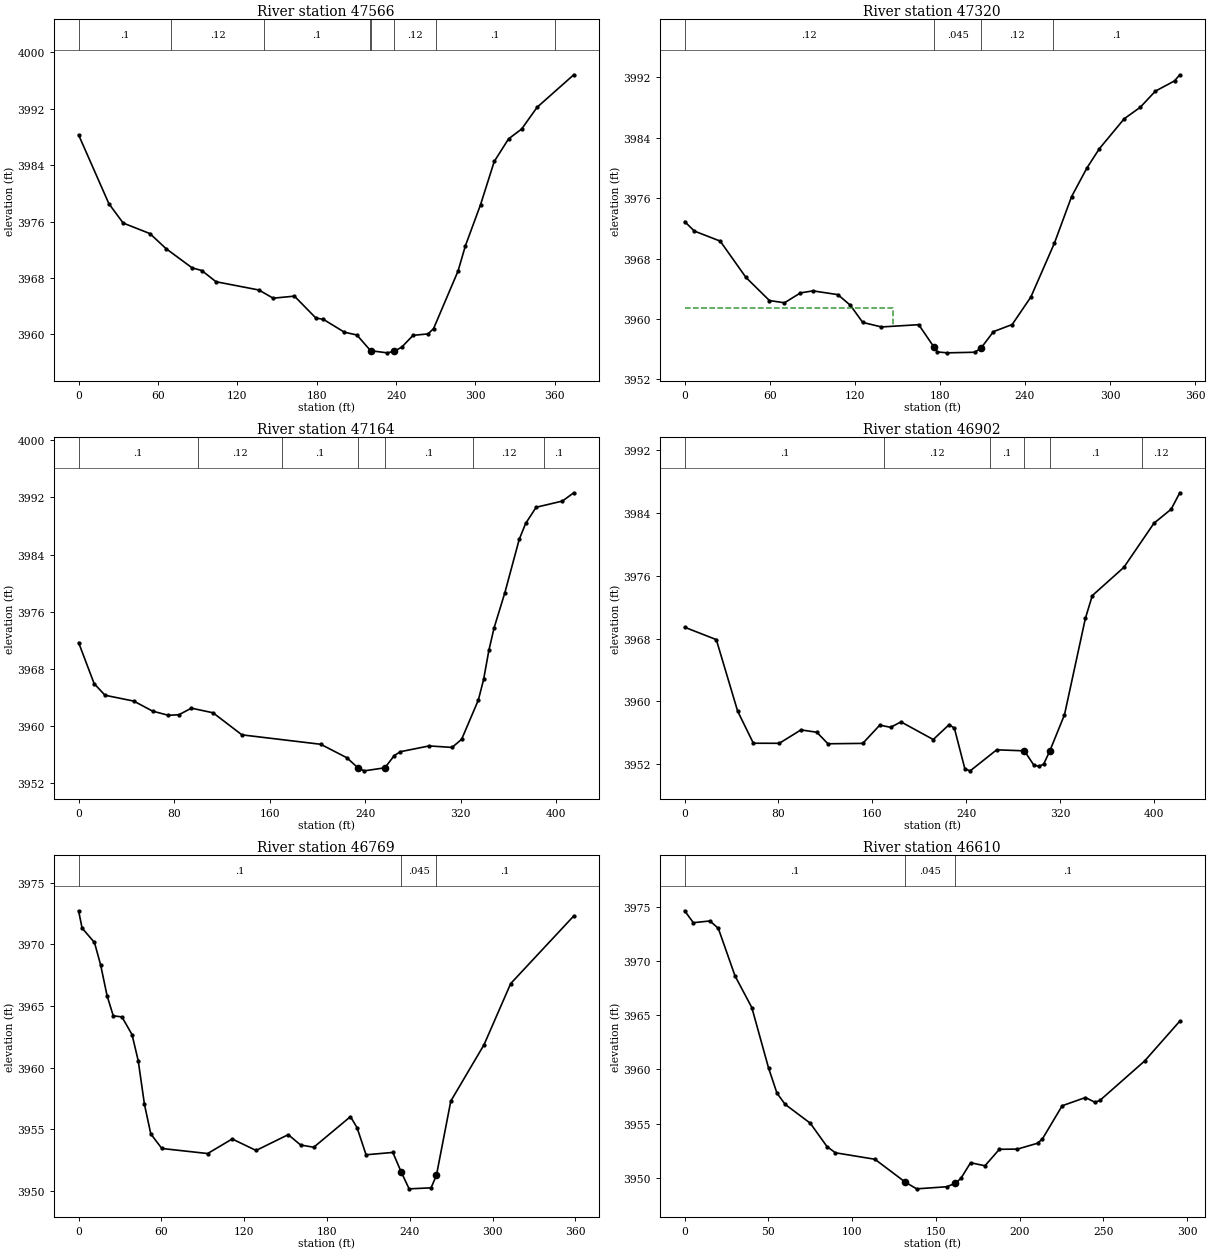
Type RM Length L Ch R = 1 ,47566   ,253.4,246.4,239.7
XS GIS Cut Line= 2
2262307.98419349524126.1732987592262559.33678408 523848.63814665
#Sta/Elev= 30
       0 3988.26    22.9 3978.52    33.7 3975.78    53.9 3974.29    66.1 3972.16
    85.8 3969.44    93.1 3969.06   103.9 3967.47   136.3  3966.3   147.1 3965.14
   163.2 3965.43   179.4 3962.33     185 3962.15     201 3960.32   210.4 3959.93
   220.8  3957.7   233.4  3957.4   238.8 3957.63   244.4 3958.22   252.9 3959.88
   264.2 3960.08   268.4 3960.83   286.9 3968.98   292.5 3972.58   303.9 3978.37
   314.3 3984.51   325.1  3987.7     335  3989.1   346.7 3992.18   374.4 3996.78
#Mann= 8 ,-1,0
       0      .1       0      70     .12       0     140      .1       0
     220     .12       0   220.8    .045       0   238.8     .12       0
     270      .1       0     360     .12       0
Bank Sta=220.8,238.8
XS Rating Curve= 0 ,0
Exp/Cntr(USF)=0,0
Exp/Cntr=0.3,0.1

Type RM Length L Ch R = 1 ,47320   ,155.6,155.7,156
XS GIS Cut Line= 2
2262589.44672983524263.6317467372262733.45081819523945.513624273
#Sta/Elev= 30
       0  3972.9     6.9 3971.64    25.1 3970.31    43.2 3965.51    59.8 3962.44
    70.4 3962.14    81.7 3963.45    90.5 3963.72   108.1 3963.22   116.9 3961.81
   125.6 3959.54   138.8 3958.94   165.1 3959.24   175.9 3956.26   178.3 3955.63
   185.3 3955.51   204.7 3955.59   209.1 3956.16   217.8 3958.32     231 3959.26
   244.2 3962.91   260.8 3970.05   272.9 3976.21   283.7    3980   292.5 3982.56
     310 3986.52   321.3 3988.04     332 3990.18   345.5 3991.54   349.2 3992.35
#Mann= 4 ,-1,0
       0     .12       0   175.9    .045       0   209.1     .12       0
     260      .1       0
#XS Ineff= 2 , 0
          147.11  3961.4
Permanent Ineff=
       F       F
Bank Sta=175.9,209.1
XS Rating Curve= 0 ,0
Exp/Cntr(USF)=0,0
Exp/Cntr=0.3,0.1

Type RM Length L Ch R = 1 ,47164   ,260,262.1,262
XS GIS Cut Line= 2
2262707.26825667524377.525889348 2262880.0731627524000.497003464
#Sta/Elev= 30
       0 3971.66      13 3965.92    22.1 3964.29    46.2 3963.47      62 3962.06
    75.2 3961.48      84 3961.56    94.5 3962.48   112.6 3961.83   136.8 3958.74
   202.8 3957.42   224.8 3955.52   234.4 3954.05   239.3  3953.7   256.53954.125
   264.4 3955.84   269.5 3956.38   293.6 3957.19   312.8 3956.98   320.8 3958.12
   334.8 3963.62   339.2  3966.5   343.6 3970.56   347.9 3973.68     357 3978.65
     369 3986.11   374.4 3988.35   383.2 3990.62   405.2 3991.49   414.7 3992.65
#Mann= 7 ,-1,0
       0      .1       0     100     .12       0     170      .1       0
   234.4    .045       0   256.5      .1       0     330     .12       0
     390      .1       0
Bank Sta=234.4,256.5
XS Rating Curve= 0 ,0
Exp/Cntr(USF)=0,0
Exp/Cntr=0.3,0.1

Type RM Length L Ch R = 1 ,46902   ,124.8,132.7,140.3
XS GIS Cut Line= 2
 2262923.2743892524469.1648546662263118.33447253524094.754224935
#Sta/Elev= 30
       0 3969.46      27 3967.88    45.2 3958.76    58.6 3954.67    80.7 3954.66
    99.2 3956.37   112.7 3956.07   122.2  3954.6   151.9 3954.65   166.4 3956.98
   175.6  3956.7   184.5 3957.39     212 3955.14   225.5 3957.04     230 3956.59
     239 3951.38   243.5 3951.15   266.1 3953.83   289.7  3953.7   297.7 3951.89
   302.2 3951.73   306.1    3952   311.2 3953.62   323.9  3958.3   341.7 3970.58
   347.6 3973.49   374.5 3977.09   400.2 3982.72   414.9 3984.51   422.2  3986.6
#Mann= 6 ,-1,0
       0      .1       0     170     .12       0     260      .1       0
   289.7    .045       0   311.2      .1       0     390     .12       0
Bank Sta=289.7,311.2
XS Rating Curve= 0 ,0
Exp/Cntr(USF)=0,0
Exp/Cntr=0.3,0.1

Type RM Length L Ch R = 1 ,46769   ,165.6,159.3,155.1
XS GIS Cut Line= 3
2263031.93201951524495.3474161862263123.57098483524322.542510156
 2263245.3198959 524213.88487985
#Sta/Elev= 30
       0 3972.72     2.5 3971.32    11.5 3970.15      16 3968.31    20.6 3965.85
    25.1 3964.21    31.4 3964.12    38.7 3962.69    43.2 3960.57    47.7 3957.04
    52.3 3954.64    60.3 3953.46    93.5 3953.05   111.3 3954.23   128.6  3953.3
   151.9 3954.58   160.9 3953.74   170.4 3953.56     197 3956.04   201.8 3955.14
   208.3 3952.95   227.7 3953.14   233.9 3951.52   239.5 3950.19   255.4 3950.27
   259.3 3951.29   269.7  3957.3   293.8 3961.87   313.1 3966.82   358.8  3972.3
#Mann= 3 ,-1,0
       0      .1       0   233.9    .045       0   259.3      .1       0
Bank Sta=233.9,259.3
XS Rating Curve= 0 ,0
Exp/Cntr(USF)=0,0
Exp/Cntr=0.3,0.1

Type RM Length L Ch R = 1 ,46610   ,103.2,101.7,100.5
XS GIS Cut Line= 2
2263169.39046749 524533.312130392263346.12275775524296.359948637
#Sta/Elev= 30
       0 3974.64     5.2 3973.54    15.1  3973.7    20.1 3973.02    30.1 3968.62
    40.1 3965.71    50.1 3960.13    55.1 3957.81      60 3956.77      75 3955.03
      85 3952.87      90  3952.3   113.6  3951.7   131.8 3949.58   138.5 3948.97
   156.4 3949.16   161.73949.488     165 3949.95   170.7 3951.38   179.3  3951.1
   187.9 3952.62   198.7 3952.64   210.7 3953.18   213.6 3953.58   225.4 3956.64
   239.3  3957.4     245 3956.96   247.9 3957.13   274.6 3960.77   295.6 3964.45
#Mann= 3 ,-1,0
       0      .1       0   131.8    .045       0   161.7      .1       0
Bank Sta=131.8,161.7
XS Rating Curve= 0 ,0
Exp/Cntr(USF)=0,0
Exp/Cntr=0.3,0.1

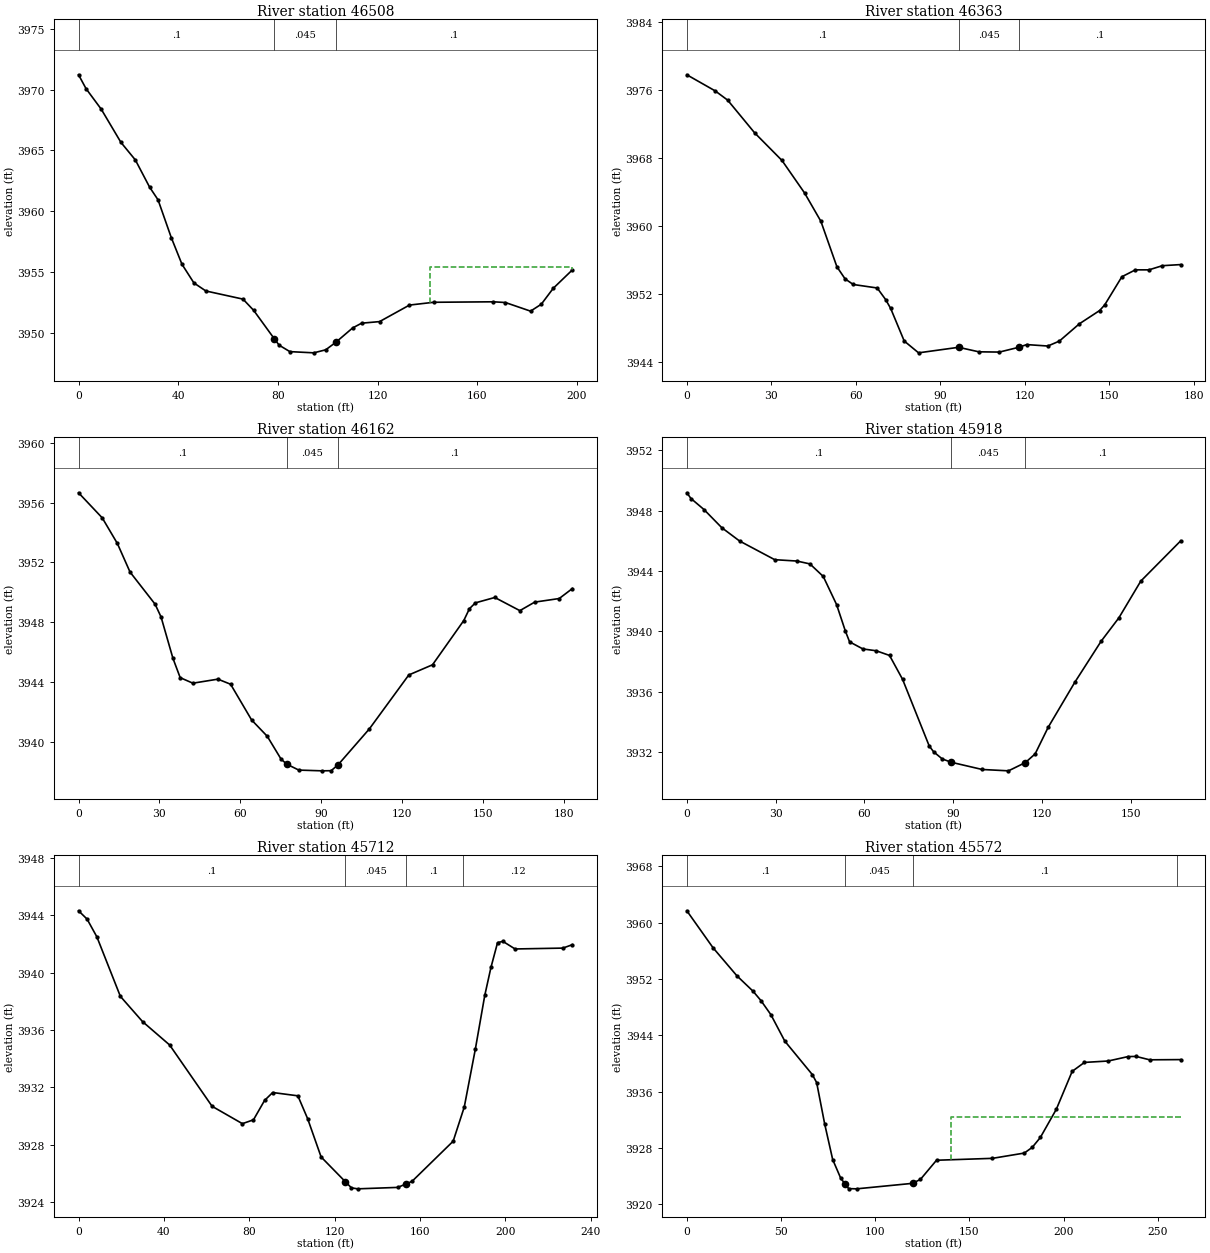
Type RM Length L Ch R = 1 ,46508   ,148.2,145.5,147.3
XS GIS Cut Line= 2
2263291.13937856524547.7125392262263401.10613694524382.762401652
#Sta/Elev= 30
       0 3971.22       3 3970.08     9.1 3968.39      17 3965.66    22.8 3964.21
    28.5 3961.98    31.9 3960.93    37.2 3957.83    41.5 3955.63    46.3 3954.09
    51.1 3953.43      66 3952.76    70.3 3951.83    78.63949.484    80.5 3948.97
    84.8 3948.44    94.4 3948.34    99.2 3948.59   103.33949.216     110 3950.39
   113.6 3950.78   120.8 3950.91   132.8 3952.27   142.5  3952.5   166.5 3952.54
   171.3 3952.48   181.4 3951.77   185.7 3952.34   190.5 3953.65   198.2 3955.17
#Mann= 3 ,-1,0
       0      .1       0    78.6    .045       0   103.3      .1       0
#XS Ineff= 2 , 0
                          141.13         3955.42
Permanent Ineff=
       F       F
Bank Sta=78.6,103.3
XS Rating Curve= 0 ,0
Exp/Cntr(USF)=0,0
Exp/Cntr=0.3,0.1

Type RM Length L Ch R = 1 ,46363   ,204.3,201.2,202.6
XS GIS Cut Line= 2
2263418.12480193524613.1689430252263516.30940762524467.855726591
#Sta/Elev= 30
       0  3977.8    10.1  3975.9    14.5 3974.82    24.1 3970.97    33.8 3967.73
    41.8 3963.92    47.6 3960.59    53.3 3955.24    56.2 3953.82    59.1 3953.16
    67.6 3952.75    70.6 3951.39    72.4 3950.34    77.2 3946.52    82.3 3945.13
    96.5 3945.78   103.7 3945.25     111 3945.22     118 3945.79   120.7  3946.1
   128.2 3945.93   132.3 3946.51   139.4 3948.54   146.6  3950.1   148.4 3950.76
   154.5 3954.07   159.3 3954.88   164.1 3954.88   168.9 3955.37   175.4  3955.5
#Mann= 3 ,-1,0
       0      .1       0    96.5    .045       0     118      .1       0
Bank Sta=96.5,118
XS Rating Curve= 0 ,0
Exp/Cntr(USF)=0,0
Exp/Cntr=0.3,0.1

Type RM Length L Ch R = 1 ,46162   ,245.7,243.6,243.5
XS GIS Cut Line= 2
2263580.45668335524737.5361102432263674.71390482524580.440741125
#Sta/Elev= 30
       0 3956.65     8.8 3954.97    14.4 3953.26    19.1 3951.35    28.4  3949.2
    30.6 3948.35      35 3945.59    37.7 3944.29    42.4 3943.92    51.7 3944.19
    56.4 3943.85    64.2 3941.46      70 3940.37    75.1 3938.85    77.2 3938.51
    81.7 3938.11    90.4 3938.06    93.7 3938.07    96.3 3938.47   107.9 3940.87
   122.5 3944.47   131.3 3945.15   142.9 3948.11     145  3948.9   147.2 3949.29
   154.4 3949.65   163.7 3948.77   169.2 3949.34   178.3 3949.58   183.2 3950.25
#Mann= 3 ,-1,0
       0      .1       0    77.2    .045       0    96.3      .1       0
Bank Sta=77.2,96.3
XS Rating Curve= 0 ,0
Exp/Cntr(USF)=0,0
Exp/Cntr=0.3,0.1

Type RM Length L Ch R = 1 ,45918   ,201.1,205.5,211.8
XS GIS Cut Line= 2
2263809.55409664524834.4115878662263884.17439698524685.170987204
#Sta/Elev= 30
       0 3949.18     1.4  3948.8     5.8 3948.07    11.8 3946.87    17.8 3945.99
    29.7 3944.75    37.2 3944.66    41.6 3944.47    46.1 3943.64    50.6 3941.78
    53.6 3940.01      55 3939.31    59.5 3938.84      64 3938.72    68.5 3938.41
    72.9 3936.83    81.9 3932.42    83.4 3932.03    86.3 3931.56    89.3 3931.34
    99.8 3930.86   108.7 3930.77   114.43931.318   117.7 3931.89   122.1 3933.65
   131.1 3936.63     140 3939.35     146  3940.9   153.4 3943.33   166.9    3946
#Mann= 3 ,-1,0
       0      .1       0    89.3    .045       0   114.4      .1       0
Bank Sta=89.3,114.4
XS Rating Curve= 0 ,0
Exp/Cntr(USF)=0,0
Exp/Cntr=0.3,0.1

Type RM Length L Ch R = 1 ,45712   ,159.1,140.8,137.6
XS GIS Cut Line= 2
2263943.08516039524952.2331147042264091.01663298524774.191696371
#Sta/Elev= 30
       0  3944.3       4 3943.72     8.6 3942.48    19.6 3938.34      30 3936.58
    42.7 3934.95    62.6 3930.68    76.8 3929.47      82 3929.74    87.2 3931.09
      91 3931.64   102.8 3931.41   107.4 3929.81   113.7 3927.15   125.1 3925.42
   127.9    3925   130.8 3924.93   149.6 3925.03   153.5 3925.27   156.3 3925.45
   175.6 3928.25   180.8 3930.63     186 3934.67   190.4  3938.4   193.3 3940.35
   196.4 3942.08   198.9 3942.17   204.6 3941.64     227  3941.7   231.5 3941.94
#Mann= 4 ,-1,0
       0      .1       0   125.1    .045       0   153.5      .1       0
     180     .12       0
Bank Sta=125.1,153.5
XS Rating Curve= 0 ,0
Exp/Cntr(USF)=0,0
Exp/Cntr=0.3,0.1

Type RM Length L Ch R = 1 ,45572   ,187.4,161.7,150.6
XS GIS Cut Line= 2
 2264084.4709926525058.2724888592264170.87344562524810.847282498
#Sta/Elev= 30
       0  3961.7    13.9 3956.45    26.6 3952.46    35.1 3950.29    39.3 3948.96
    44.6 3946.95      52 3943.19    66.6 3938.44    68.9  3937.3    73.2 3931.37
    77.4 3926.38    81.7 3923.71      84 3922.91    85.9 3922.25    90.1 3922.22
   119.8    3923     124 3923.57   132.5 3926.28   162.2 3926.55   179.1  3927.3
   183.3 3928.11   187.6 3929.51   196.1 3933.53   204.5  3938.9     211 3940.17
   223.6 3940.37   234.2    3941   238.4 3941.02   245.6 3940.54   262.1 3940.57
#Mann= 4 ,-1,0
       0      .1       0      84    .045       0   119.8      .1       0
     260     .12       0
#XS Ineff= 2 , 0
                          140.21         3932.35
Permanent Ineff=
       F       F
Bank Sta=84,119.8
XS Rating Curve= 0 ,0
Exp/Cntr(USF)=0,0
Exp/Cntr=0.3,0.1

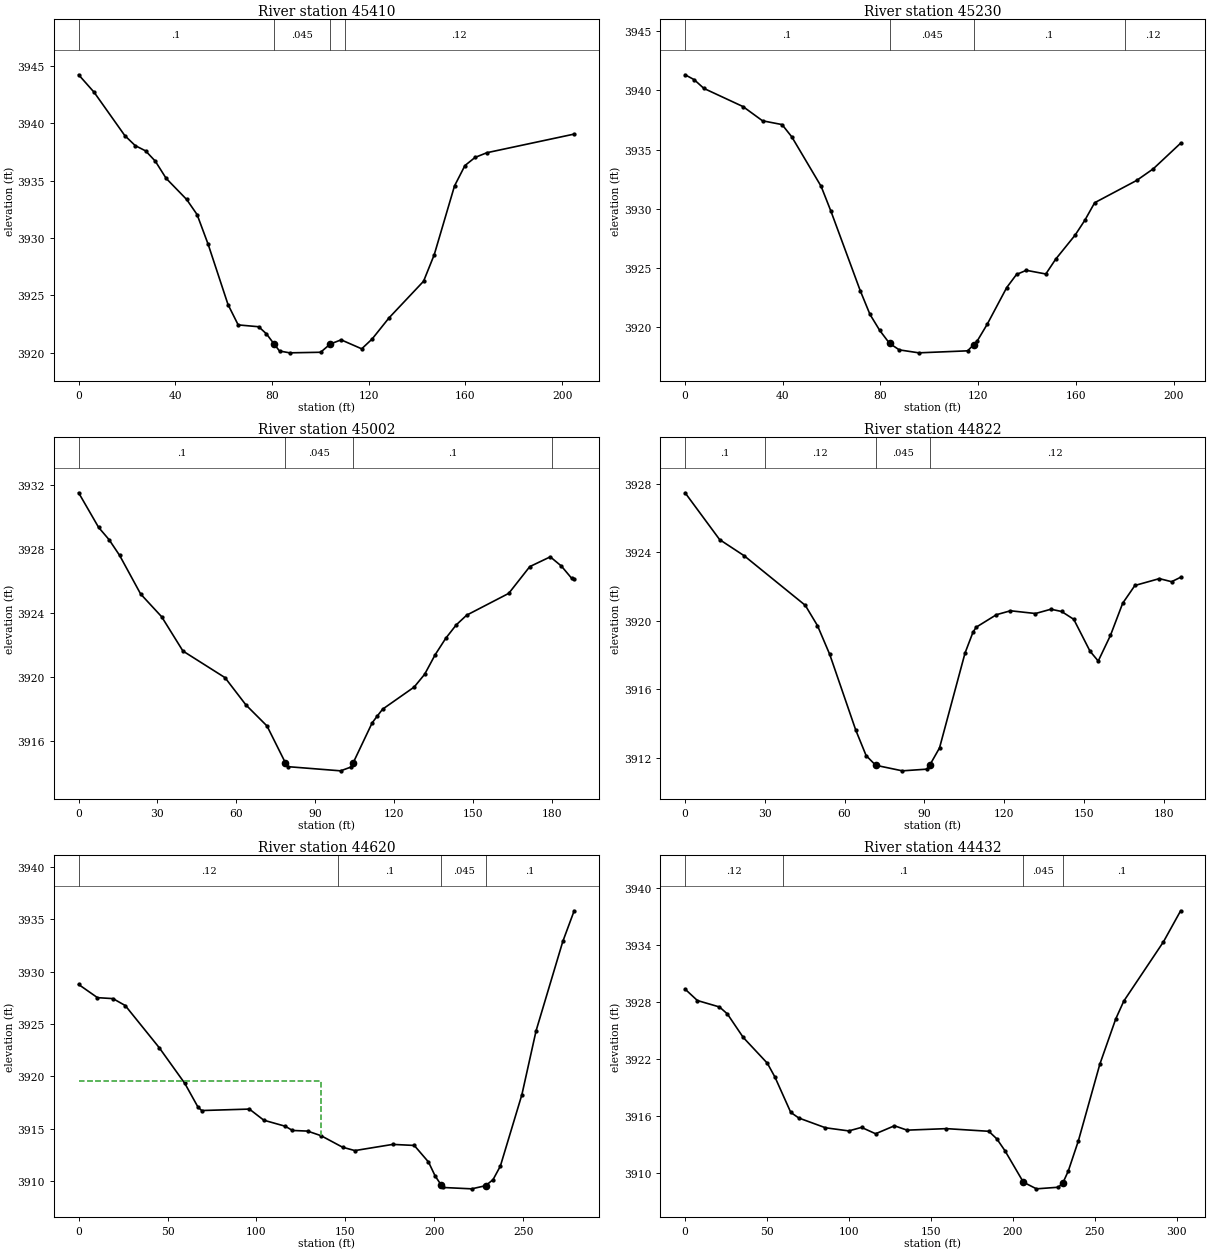
Type RM Length L Ch R = 1 ,45410   ,168.3,179.5,186.2
XS GIS Cut Line= 2
2264310.95014975525011.1438781242264240.25723364524818.702050954
#Sta/Elev= 30
       0  3944.2     6.4 3942.68    19.1 3938.91    23.4 3938.04    27.7 3937.58
    31.7 3936.69    36.2 3935.19    44.7 3933.35      49 3932.04    53.6 3929.44
    61.8 3924.21      66 3922.44    74.5 3922.28    77.7 3921.66    80.83920.795
    83.1 3920.17    87.3 3920.01   100.1 3920.06   104.13920.779   108.6 3921.14
   117.1 3920.36   121.4 3921.21   128.4 3923.05   142.7 3926.24   147.1 3928.54
   155.5 3934.53   159.8  3936.3     164 3937.01   168.9 3937.42     205 3939.04
#Mann= 4 ,-1,0
       0      .1       0    80.8    .045       0   104.1      .1       0
     110     .12       0
Bank Sta=80.8,104.1
XS Rating Curve= 0 ,0
Exp/Cntr(USF)=0,0
Exp/Cntr=0.3,0.1

Type RM Length L Ch R = 1 ,45230   ,226.9,228.6,228.4
XS GIS Cut Line= 2
2264445.79034157524988.8887008322264447.09946965524785.973849054
#Sta/Elev= 30
       0 3941.31     3.7  3940.9     7.7 3940.16    23.7 3938.63    31.7 3937.43
    39.7 3937.11    43.7 3936.07    55.7  3931.9    59.7 3929.81    71.7 3923.11
    75.7  3921.1    79.7 3919.75    83.7 3918.66    87.7 3918.11    95.7 3917.86
   115.7 3918.03   118.1 3918.54   119.7 3918.89   123.7 3920.27   131.7 3923.37
   135.7 3924.47   139.7 3924.82   147.7 3924.51   151.7 3925.75   159.7 3927.79
   163.7 3929.05   167.7 3930.52   184.9  3932.4   191.7 3933.38   202.9 3935.54
#Mann= 4 ,-1,0
       0      .1       0    83.7    .045       0   118.1      .1       0
     180     .12       0
Bank Sta=83.7,118.1
XS Rating Curve= 0 ,0
Exp/Cntr(USF)=0,0
Exp/Cntr=0.3,0.1

Type RM Length L Ch R = 1 ,45002   ,188.4,179.4,165.1
XS GIS Cut Line= 2
2264670.96037064 524992.816085062264676.19688295524804.301642118
#Sta/Elev= 30
       0 3931.51     7.6 3929.35    11.6 3928.58    15.6  3927.6    23.6 3925.19
    31.6 3923.77    39.7 3921.63    55.7 3919.97    63.7 3918.26    71.7 3916.95
    78.7 3914.65    79.7 3914.41    99.7 3914.15   103.7 3914.39   104.53914.654
   111.7 3917.14   113.6 3917.56   115.7    3918   127.7 3919.38   131.7 3920.18
   135.7  3921.4   139.7 3922.42   143.7 3923.26   147.7 3923.87   163.7 3925.23
   171.7  3926.9   179.5 3927.51   183.7 3926.94   187.7 3926.16   188.6 3926.13
#Mann= 4 ,-1,0
       0      .1       0    78.7    .045       0   104.5      .1       0
     180     .12       0
Bank Sta=78.7,104.5
XS Rating Curve= 0 ,0
Exp/Cntr(USF)=0,0
Exp/Cntr=0.3,0.1

Type RM Length L Ch R = 1 ,44822   ,188.9,202.7,217.6
XS GIS Cut Line= 2
2264884.34824703524936.5235777922264792.70928171524774.191696371
#Sta/Elev= 30
       0 3927.48      13 3924.74    22.2  3923.8    45.2  3920.9    49.8 3919.71
    54.4 3918.03    64.2  3913.6    68.1 3912.11    71.73911.546    81.7 3911.22
    91.1 3911.32    92.13911.572    95.7 3912.56   105.3 3918.11   108.3 3919.33
   109.5 3919.62   117.1 3920.35   122.4 3920.58   131.8 3920.42   137.6 3920.67
   141.6 3920.54   146.2 3920.08   152.3 3918.22   155.4 3917.64     160 3919.14
   164.6 3921.02   169.2 3922.06   178.4 3922.46     183 3922.28   186.4 3922.54
#Mann= 4 ,-1,0
       0      .1       0      30     .12       0    71.7    .045       0
    92.1     .12       0
Bank Sta=71.7,92.1
XS Rating Curve= 0 ,0
Exp/Cntr(USF)=0,0
Exp/Cntr=0.3,0.1

Type RM Length L Ch R = 1 ,44620   ,168.7,187.1,206.2
XS GIS Cut Line= 3
2264935.40424199524943.0692181722264982.53285273524871.067173993
2265006.09715809  524679.9344749
#Sta/Elev= 30
       0 3928.78    10.6 3927.52    19.3 3927.43    26.2 3926.77    45.3 3922.75
    59.7 3919.34    67.1 3917.08    69.2 3916.75      96 3916.89   104.1 3915.83
   116.2 3915.25   120.2 3914.85   128.7 3914.79   136.3 3914.35   148.4 3913.25
   155.3 3912.93   176.6 3913.52   188.7 3913.42   196.7 3911.84   200.4 3910.52
     204  3909.6   204.8 3909.41     221 3909.28   228.8 3909.58     233 3910.16
   237.1 3911.45   249.2 3918.26   257.2 3924.37   272.2 3932.88   278.6 3935.81
#Mann= 4 ,-1,0
       0     .12       0  146.05      .1       0     204    .045       0
   228.8      .1       0
#XS Ineff= 2 , 0
          136.42 3919.59
Permanent Ineff=
       F       F
Bank Sta=204,228.8
XS Rating Curve= 0 ,0
Exp/Cntr(USF)=0,0
Exp/Cntr=0.3,0.1

Type RM Length L Ch R = 1 ,44432   ,218.8,222,224.9
XS GIS Cut Line= 2
2264966.82331581524961.3970112362265216.86677833524791.210361358
#Sta/Elev= 30
       0 3929.34     7.5 3928.14      21 3927.46    25.8 3926.73    35.5 3924.25
    50.2 3921.54    54.9 3920.06    64.5 3916.36    69.4 3915.77    85.7 3914.74
    99.9 3914.41   107.7 3914.78   116.3 3914.11   127.8 3914.95   135.5 3914.49
   159.5 3914.65   185.4 3914.37   190.3 3913.57   195.2 3912.34   206.5 3909.01
   214.5 3908.31   227.9 3908.48   230.73908.972   233.9 3910.18   240.1 3913.38
   253.2 3921.45   262.9 3926.21   267.8 3928.08     292 3934.32   302.5 3937.59
#Mann= 4 ,-1,0
       0     .12       0      60      .1       0   206.5    .045       0
   230.7      .1       0
Bank Sta=206.5,230.7
XS Rating Curve= 0 ,0
Exp/Cntr(USF)=0,0
Exp/Cntr=0.3,0.1