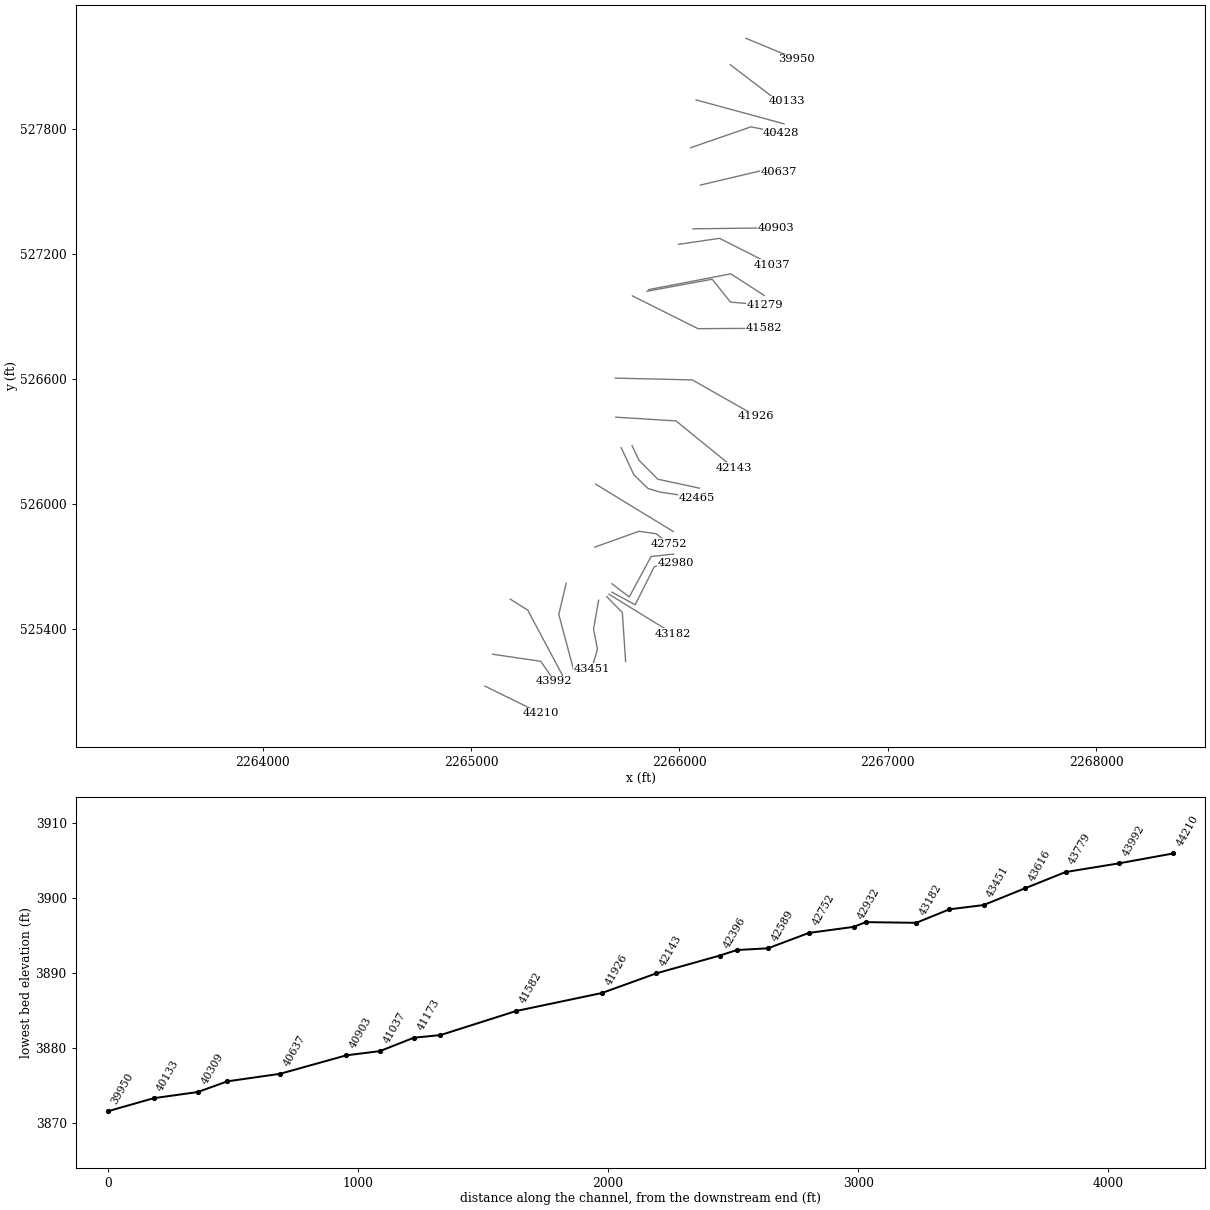
HEC-RAS study SHVRSFK.prj: SHVRSFK

--- SHVRSFK.g01 (geometry) --- (continued)

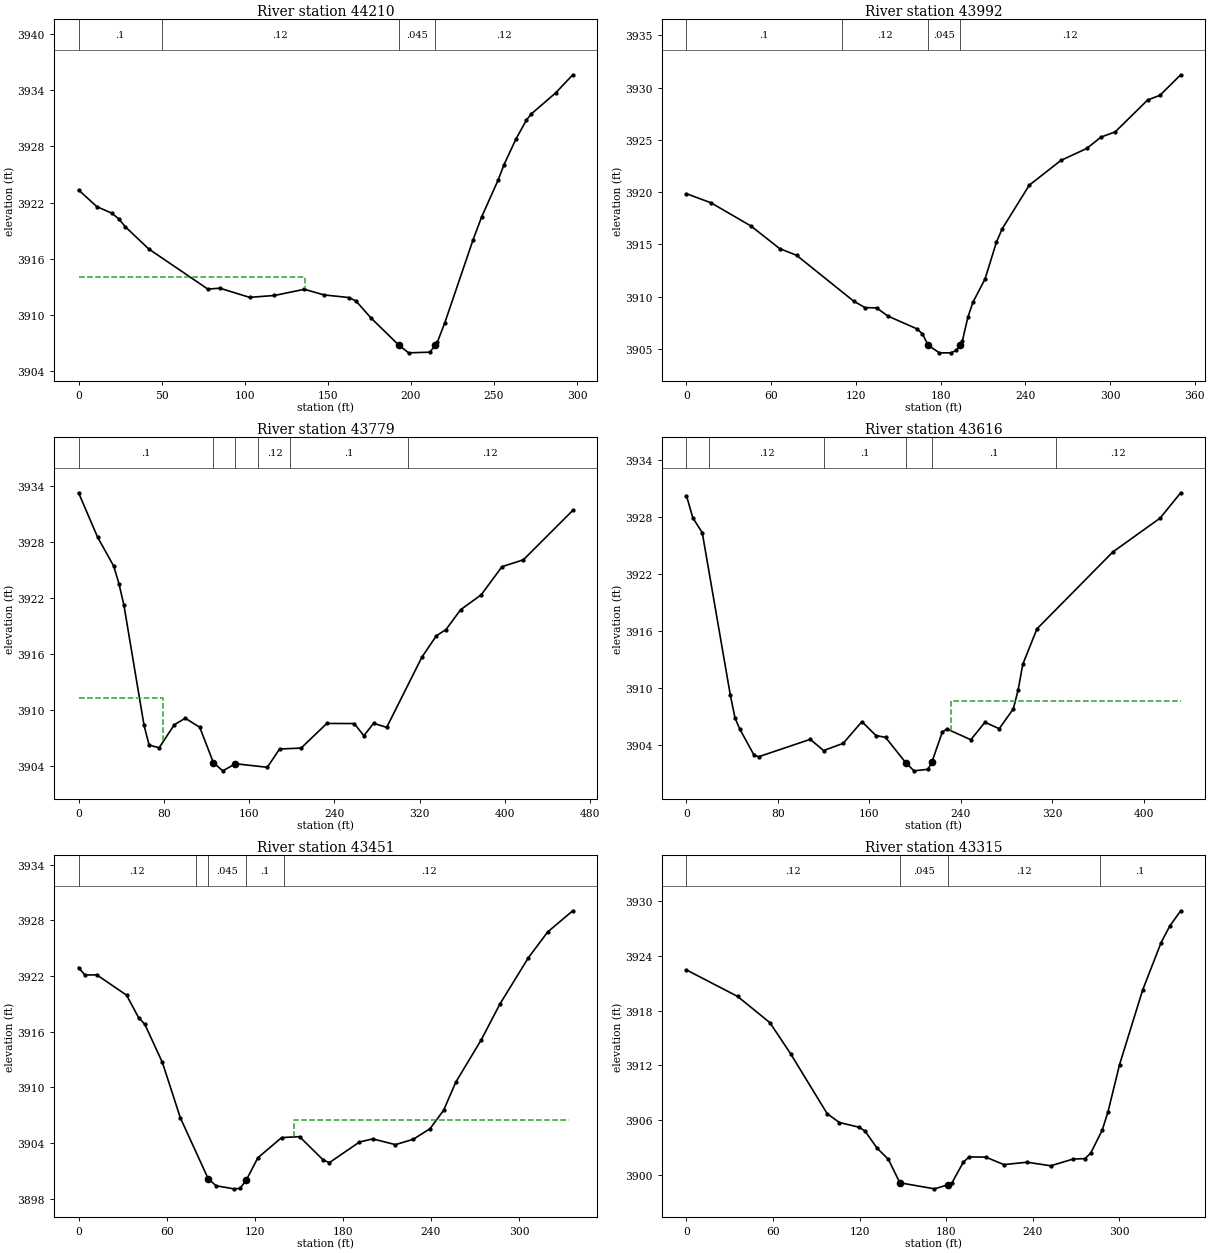
Type RM Length L Ch R = 1 ,44210   ,212.9,218.7,225.9
XS GIS Cut Line= 2
2265066.31704959525125.0380207342265333.37917709524994.125213136
#Sta/Elev= 30
       0 3923.35      11 3921.57    19.9 3920.88    24.3 3920.25    28.2 3919.41
    42.2 3917.06    77.8 3912.77      85 3912.87   102.9 3911.89   117.9 3912.09
   135.8 3912.75   147.8 3912.15   162.7 3911.87   166.9 3911.51   175.8 3909.72
   192.6 3906.81   198.6 3905.97   211.4 3906.04   214.73906.787   215.9  3907.1
   220.4 3909.18   237.4 3918.03   242.6 3920.49   252.4 3924.37     256 3926.04
   263.2 3928.78   269.4 3930.77   272.3 3931.44   287.2 3933.72   297.4 3935.64
#Mann= 4 ,-1,0
       0      .1       0      50     .12       0   192.6    .045       0
   214.7     .12       0
#XS Ineff= 2 , 0
          136.12 3914.04
Permanent Ineff=
       F       F
Bank Sta=192.6,214.7
XS Rating Curve= 0 ,0
Exp/Cntr(USF)=0,0
Exp/Cntr=0.3,0.1

Type RM Length L Ch R = 1 ,43992   ,226.4,212.9,188.3
XS GIS Cut Line= 3
2265102.97263572525278.2060056242265334.68830517525244.168675649
2265400.14470896525148.602326102
#Sta/Elev= 30
       0 3919.85    17.4 3918.98    45.7 3916.76    65.9 3914.61      78 3913.96
   118.5 3909.57   126.5 3908.96   134.6 3908.94   142.7 3908.15   162.9 3906.95
     167 3906.47   171.2 3905.36   179.1 3904.64   187.2 3904.64   191.2 3904.87
   193.53905.344   195.3 3905.73   199.3 3908.06   202.9 3909.49   211.4 3911.69
   219.5 3915.22   223.6  3916.5   242.7 3920.66   265.1 3923.03   283.5 3924.18
   293.5 3925.26   303.6 3925.76   326.6 3928.81   335.3 3929.26     350 3931.22
#Mann= 4 ,-1,0
       0      .1       0     110     .12       0   171.2    .045       0
   193.5     .12       0
Bank Sta=171.2,193.5
XS Rating Curve= 0 ,0
Exp/Cntr(USF)=0,0
Exp/Cntr=0.3,0.1

Type RM Length L Ch R = 1 ,43779   ,164,163,155.9
XS GIS Cut Line= 3
2265188.06596066525542.6498769732265271.85015752525490.284753934
2265443.34593547525168.239247242
#Sta/Elev= 30
       0 3933.29    17.9 3928.52      33 3925.43    37.9 3923.54    42.6 3921.21
    61.4 3908.38    66.2 3906.24    75.6 3905.95    89.8 3908.42   100.1 3909.12
   113.7 3908.15   126.5 3904.36   135.3 3903.48   147.2 3904.24   177.1 3903.86
   188.6 3905.82   208.8 3905.92   232.9 3908.56   258.7 3908.55   267.7 3907.24
   276.8 3908.58   289.1 3908.14   322.1 3915.66   335.7 3917.96   344.8 3918.63
   358.4 3920.75   377.8 3922.35   397.3 3925.37   417.3  3926.1   463.7  3931.4
#Mann= 6 ,-1,0
       0      .1       0   126.5    .045       0   147.2      .1       0
   168.8     .12       0   198.8      .1       0   308.8     .12       0
#XS Ineff= 2 , 0
           78.95 3911.34
Permanent Ineff=
       F       F
Bank Sta=126.5,147.2
XS Rating Curve= 0 ,0
Exp/Cntr(USF)=0,0
Exp/Cntr=0.3,0.1

Type RM Length L Ch R = 1 ,43616   ,174.4,164.4,154.9
XS GIS Cut Line= 3
2265456.43721623 525618.579305382265421.09075818525469.338704718
2265493.09280236525199.658321065
#Sta/Elev= 30
       0 3930.22     5.5  3927.9    13.8 3926.32    38.4 3909.23    42.5 3906.83
    46.7 3905.68      59 3902.97    63.1 3902.78   108.3 3904.61     120 3903.43
   137.1 3904.19   153.5 3906.47   165.8 3905.01   174.2 3904.82     192 3902.14
   199.1  3901.3   211.4 3901.46   214.8 3902.24   223.9 3905.38   227.9  3905.7
   248.8 3904.57   261.2  3906.4   273.7 3905.73     286 3907.81   290.2 3909.78
   294.3  3912.5   306.7 3916.22     373 3924.29   414.4 3927.85   432.5 3930.52
#Mann= 6 ,-1,0
       0      .1       0      20     .12       0     120      .1       0
     192    .045       0   214.8      .1       0  323.37     .12       0
#XS Ineff= 2 , 0
                          231.38         3908.62
Permanent Ineff=
       F       F
Bank Sta=192,214.8
XS Rating Curve= 0 ,0
Exp/Cntr(USF)=0,0
Exp/Cntr=0.3,0.1

Type RM Length L Ch R = 1 ,43451   ,130.2,136.8,142.7
XS GIS Cut Line= 4
2265612.22345727525537.4133646692265587.81182809525398.680631287
2265606.73261123525301.9744063612265579.07561241525208.822217597
#Sta/Elev= 30
       0 3922.91     4.3 3922.11    12.4 3922.13    32.7 3919.94    40.9 3917.52
    45.1 3916.81    57.1 3912.69    69.3 3906.7488.294733900.168    93.7 3899.41
   105.8 3899.08   109.9 3899.12114.19323900.007   122.1 3902.42   138.3  3904.6
   150.5  3904.7   166.8 3902.16   170.9 3901.91   191.3 3904.12   200.4 3904.46
   215.8 3903.84     228 3904.42   239.4 3905.56   248.6 3907.53   256.9 3910.56
   274.3 3915.14   287.1 3919.02   306.4 3923.98   319.5 3926.75   336.6 3929.03
#Mann= 5 ,-1,0
       0     .12       0      80      .1       088.29473    .045       0
114.1932      .1       0     140     .12       0
#XS Ineff= 1 ,-1
  146.62   334.3 3906.48
Permanent Ineff=
       F
Bank Sta=88.29473,114.1932
XS Rating Curve= 0 ,0
Exp/Cntr(USF)=0,0
Exp/Cntr=0.3,0.1

Type RM Length L Ch R = 1 ,43315   ,113.5,132.8,155.5
XS GIS Cut Line= 3
2265651.49729955525554.4320296572265726.11759988 525478.50260125
 2265741.8271368525242.859547573
#Sta/Elev= 30
       0 3922.44    35.4 3919.55    57.8 3916.68    72.1  3913.3    97.5 3906.73
     106 3905.76   119.8 3905.24   123.8 3904.82   132.2 3902.94   139.9 3901.75
   147.9 3899.17   171.9 3898.51     181 3898.94     184 3899.16     192 3901.45
     196    3902   207.4 3901.98     220 3901.16   236.1 3901.42   252.5 3901.03
   268.1 3901.77   276.2 3901.81   280.2 3902.41   288.2 3904.93   292.2 3906.93
   300.2 3912.09   316.2 3920.24     329 3925.43   335.1 3927.26   342.6 3928.91
#Mann= 4 ,-1,0
       0     .12       0   147.9    .045       0     181     .12       0
  286.46      .1       0
Bank Sta=147.9,181
XS Rating Curve= 0 ,0
Exp/Cntr(USF)=0,0
Exp/Cntr=0.3,0.1

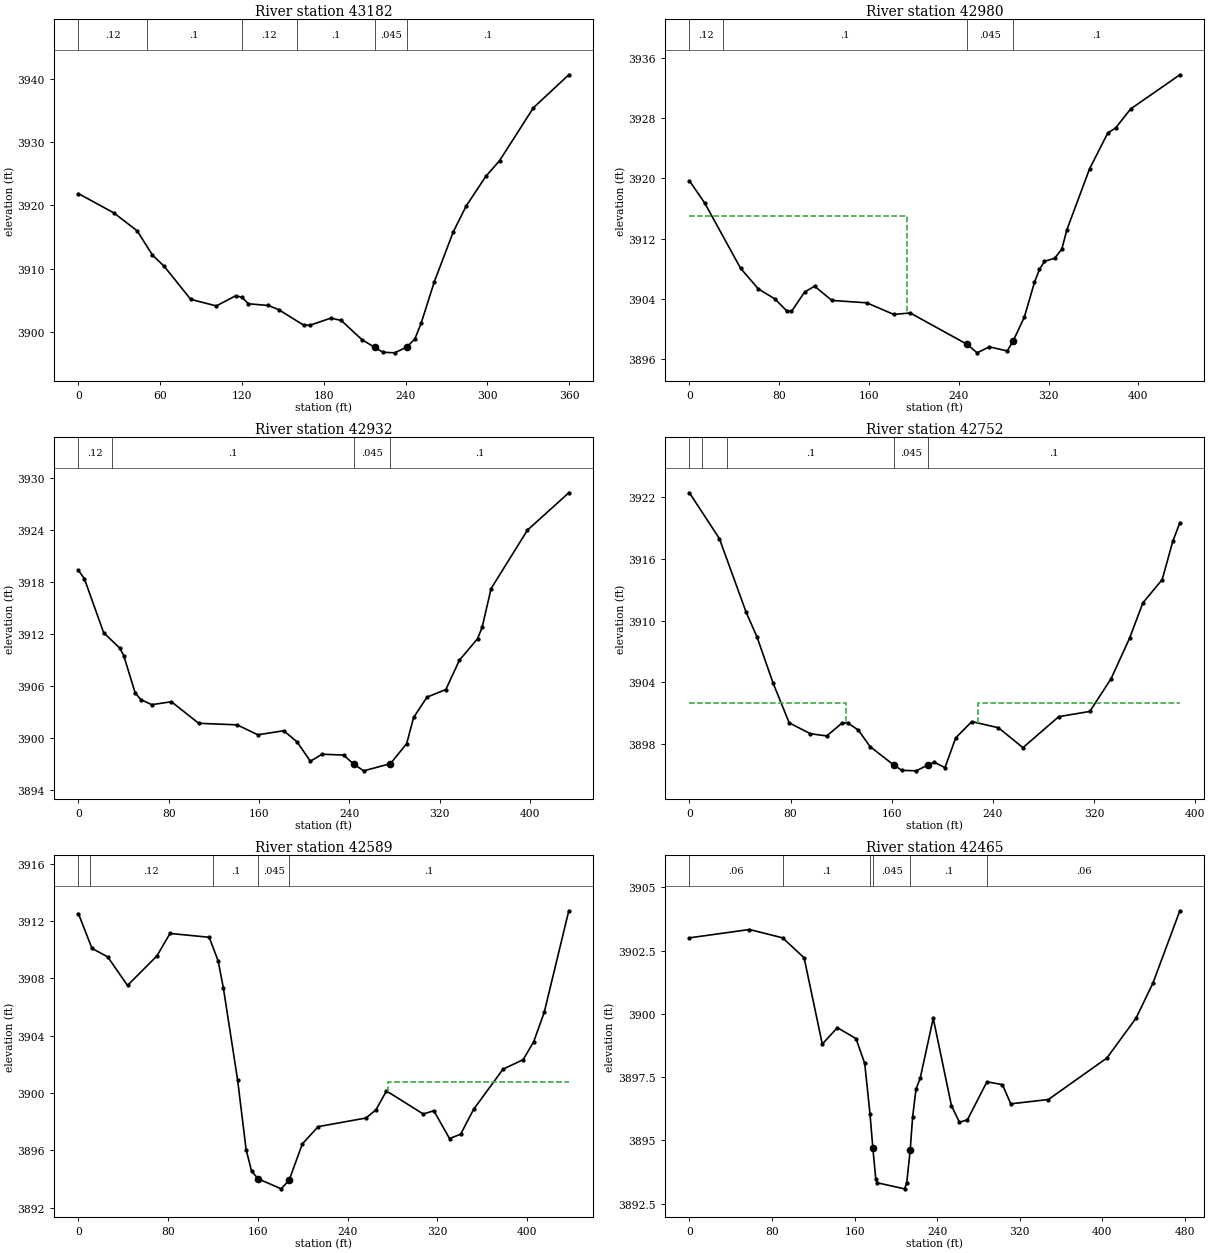
Type RM Length L Ch R = 1 ,43182   ,145.6,201.8,228.6
XS GIS Cut Line= 2
2265661.97032416525566.2141823412265968.30629394525377.699739399
#Sta/Elev= 30
       0 3921.87    26.1 3918.81    43.1 3915.99    54.3 3912.17      63 3910.37
    82.4 3905.16   101.2 3904.12   115.3 3905.72     120 3905.49   124.7 3904.46
   139.4 3904.19     147 3903.52   165.2 3901.09   169.9 3901.07   185.1 3902.19
   192.8 3901.83     208 3898.79   217.5 3897.56   223.3 3896.81     232 3896.71
   240.8 3897.62   246.8  3898.9   251.5 3901.45   261.1 3907.96     275 3915.84
   284.4 3919.89   298.9 3924.61   308.9 3927.06   333.8 3935.44   359.7 3940.64
#Mann= 6 ,-1,0
       0     .12       0      50      .1       0     120     .12       0
     160      .1       0   217.5    .045       0   240.8      .1       0
Bank Sta=217.5,240.8
XS Rating Curve= 0 ,0
Exp/Cntr(USF)=0,0
Exp/Cntr=0.3,0.1

Type RM Length L Ch R = 1 ,42980   ,55.4,47.9,50.4
XS GIS Cut Line= 4
 2265676.1613738525576.3467849512265787.69939039525515.894882826
2265879.65439644525698.9534596842265983.52949587525715.130729267
#Sta/Elev= 30
       0 3919.68    13.7  3916.7    45.5 3908.06    61.4  3905.3    76.1 3903.97
    86.5 3902.41    90.9  3902.3   102.7  3904.9   111.5 3905.66   126.9 3903.77
     158 3903.45     182 3901.91   196.7  3902.1   247.4 3897.93   256.3  3896.8
   267.1  3897.6   283.1 3897.05   288.3 3898.35   298.4 3901.57   307.4 3906.19
   311.8 3907.89   316.3 3908.96   325.3 3909.38   331.7 3910.57   336.3 3913.19
   356.5 3921.28   372.7 3926.04   379.7 3926.71     393 3929.23   436.9 3933.78
#Mann= 4 ,-1,0
       0     .12       0      30      .1       0   247.4    .045       0
   288.3      .1       0
#XS Ineff= 2 , 0
           194.2    3915
Permanent Ineff=
       F       F
Bank Sta=247.4,288.3
XS Rating Curve= 0 ,0
Exp/Cntr(USF)=0,0
Exp/Cntr=0.3,0.1

Type RM Length L Ch R = 1 ,42932   ,205.7,179.7,166.6
XS GIS Cut Line= 4
2265676.25597771525616.7216338582265759.15003095525553.200360246
2265864.26549282525747.6639647182265972.53441856525759.226665524
#Sta/Elev= 30
       0 3919.32     5.3 3918.36    22.4 3912.12    36.7 3910.34    40.2 3909.47
    50.3 3905.17    55.3  3904.4      65 3903.81    82.4 3904.15   106.6 3901.66
   140.6 3901.48     159 3900.33   181.9  3900.8   193.7 3899.52   205.5 3897.28
   215.9 3898.09     235 3897.99   243.9 3896.94   252.8 3896.17   276.4    3897
   290.8 3899.31     297 3902.35   308.8 3904.68   325.5 3905.56   337.5 3908.94
   353.6 3911.43   357.6 3912.73   365.6 3917.22   397.8 3923.97   434.4 3928.28
#Mann= 4 ,-1,0
       0     .12       0      30      .1       0   243.9    .045       0
   276.4      .1       0
Bank Sta=243.9,276.4
XS Rating Curve= 0 ,0
Exp/Cntr(USF)=0,0
Exp/Cntr=0.3,0.1

Type RM Length L Ch R = 1 ,42752   ,179.3,163.2,136.5
XS GIS Cut Line= 4
2265593.89566421525792.6933394862265805.97441252525868.622767893
2265888.44948131525856.8406152092265951.28762895525808.402876397
#Sta/Elev= 30
       0 3922.46    23.7 3917.99    44.9  3910.8    53.4 3908.42    66.2  3903.9
    78.9 3900.04    95.6 3898.98   108.6 3898.76     121 3900.05   125.6    3900
   133.6 3899.33   142.9 3897.72   161.7 3895.92     168 3895.41   179.4 3895.36
   188.3 3895.91   193.6  3896.2   202.1 3895.67   210.6 3898.57   223.3 3900.16
   244.4 3899.56   263.8 3897.62   292.1 3900.64   316.7 3901.15   333.5 3904.34
   348.1 3908.28   358.7 3911.74   373.9 3913.99   382.3 3917.72   387.9 3919.54
#Mann= 5 ,-1,0
       0      .1       0      10     .12       0      30      .1       0
   161.7    .045       0   188.3      .1       0
#XS Ineff= 2 , 0
          123.59 3901.98  228.25         3901.93
Permanent Ineff=
       F       F
Bank Sta=161.7,188.3
XS Rating Curve= 0 ,0
Exp/Cntr(USF)=0,0
Exp/Cntr=0.3,0.1

Type RM Length L Ch R = 1 ,42589   ,128.9,124.1,117.1
XS GIS Cut Line= 2
2265597.82304844526095.1019250382265970.92455009525867.313639817
#Sta/Elev= 30
       0 3912.52    12.1 3910.09    26.2 3909.49    43.8  3907.5      70 3909.56
    81.7 3911.13   116.6 3910.86   124.6 3909.21   129.3 3907.29   141.9 3900.92
   149.5 3896.05   154.4 3894.54   160.2 3894.01   180.8 3893.31   187.9 3893.92
   199.6 3896.44   213.7 3897.65   256.3 3898.25   265.2 3898.82   274.6 3900.14
   307.4 3898.53   316.8 3898.76   330.8 3896.82   340.7 3897.12   352.3 3898.86
   378.5 3901.66   396.4 3902.32   405.8 3903.57   415.2 3905.62   437.1 3912.71
#Mann= 5 ,-1,0
       0      .1       0      10     .12       0     120      .1       0
   160.2    .045       0   187.9      .1       0
#XS Ineff= 2 , 0
                          275.92         3900.76
Permanent Ineff=
       F       F
Bank Sta=160.2,187.9
XS Rating Curve= 0 ,0
Exp/Cntr(USF)=0,0
Exp/Cntr=0.3,0.1

Type RM Length L Ch R = 1 ,42465   ,68.4,68.8,67.8
XS GIS Cut Line= 5
2265720.78108093526269.7992599552265781.48108147526140.024812735
2265849.00272776526074.4364010542265905.19745368 526057.40769623
2266082.09022339526030.256608236
#Sta/Elev= 30
       0    3903    58.1 3903.33    90.3    3903   111.1 3902.21   128.7  3898.8
   143.3 3899.45   161.3 3899.02   169.8 3898.04   174.9 3896.05  177.66  3894.7
   180.5 3893.47   181.8 3893.32   208.4 3893.08   210.5 3893.32   213.9 3894.62
   216.2 3895.92   219.5 3897.02   223.6 3897.46   236.2 3899.82   253.8 3896.37
   261.6 3895.71   269.3 3895.81   288.2 3897.31   303.2  3897.2   311.3 3896.44
   347.7 3896.61   404.4 3898.25   432.7 3899.83   448.9  3901.2   475.1 3904.07
#Mann= 6 ,-1,0
       0     .06       0    90.3      .1       0   174.9     .06       0
  177.66    .045       0   213.9      .1       0   288.2     .06       0
#XS Ineff= 3 ,-1
     100     170  3894.3     226     244  3894.8     244     400    3898
Permanent Ineff=
       F       F       F
Bank Sta=177.66,213.9
XS Rating Curve= 0 ,0
Exp/Cntr(USF)=0,0
Exp/Cntr=0.3,0.1

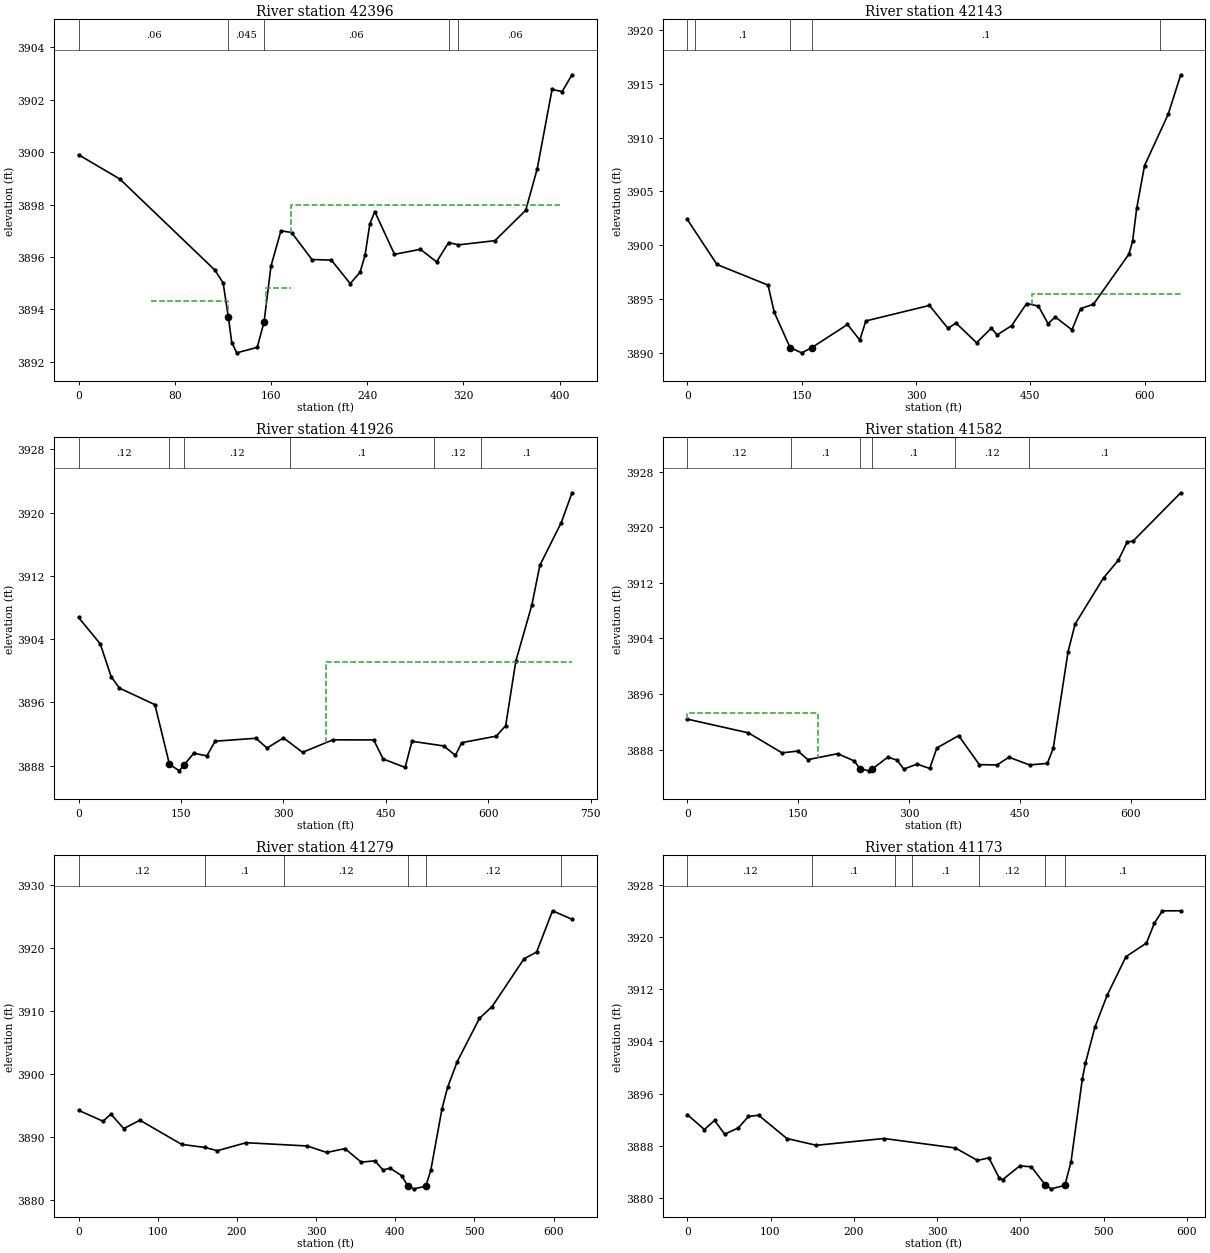
Type RM Length L Ch R = 1 ,42396   ,245.1,253.4,277.2
XS GIS Cut Line= 4
2265772.88459754526279.7268683152265806.19075465526209.612234862
2265896.00467057526118.9470591892266096.43643616526075.657747287
#Sta/Elev= 30
       0  3899.9    34.4 3898.97   113.3  3895.5   120.2 3895.01   124.6  3893.7
   127.4 3892.73   131.6 3892.34   148.6 3892.55   154.3 3893.53     160 3895.65
   168.3    3897   177.1 3896.93   194.1  3895.9   210.2 3895.88   225.9 3894.98
   234.1 3895.42   238.2 3896.06   242.2 3897.26   246.3 3897.73   262.7  3896.1
   284.3 3896.29   297.7 3895.81   307.7 3896.55   315.9 3896.46   346.2 3896.62
   371.8 3897.78   381.4 3899.37   393.7 3902.39   402.1 3902.31   410.3 3902.95
#Mann= 5 ,-1,0
       0     .06       0   124.6    .045       0   154.3     .06       0
   307.7      .1       0   315.9     .06       0
#XS Ineff= 3 ,-1
      60     124  3894.3     156     177  3894.8     177     400    3898
Permanent Ineff=
       F       F       F
Bank Sta=124.6,154.3
XS Rating Curve= 0 ,0
Exp/Cntr(USF)=0,0
Exp/Cntr=0.3,0.1

Type RM Length L Ch R = 1 ,42143   ,213.5,217.2,216.7
XS GIS Cut Line= 3
2265694.35552098526416.7114669922265983.67661687526398.753605867
2266261.02580535526173.282682858
#Sta/Elev= 30
       0 3902.39      39 3898.19     106 3896.27     114 3893.77   134.93890.453
   150.1 3889.97   163.5 3890.46   210.2 3892.61   226.3 3891.16   234.3 3892.94
   317.7 3894.38   342.1 3892.24   352.4 3892.75   379.5 3890.91   398.8 3892.26
   406.5 3891.64   425.5  3892.5   445.2 3894.56   460.6 3894.32   473.3 3892.68
   482.6 3893.31   504.6 3892.11     516 3894.09   532.8 3894.49   579.2 3899.14
   584.1 3900.33   589.5  3903.4   599.8 3907.39   630.8 3912.16   647.3 3915.84
#Mann= 5 ,-1,0
       0     .07       0      10      .1       0   134.9    .045       0
   163.5      .1       0  619.88     .06       0
#XS Ineff= 2 , 0
                          451.57         3895.42
Permanent Ineff=
       F       F
Bank Sta=134.9,163.5
XS Rating Curve= 0 ,0
Exp/Cntr(USF)=0,0
Exp/Cntr=0.3,0.1

Type RM Length L Ch R = 1 ,41926   ,352,343.8,333.5
XS GIS Cut Line= 3
2265692.36020307526604.2713498492266061.93044708526595.649082871
2266368.62846331526421.438223026
#Sta/Elev= 30
       0 3906.75    31.8 3903.41    47.8 3899.25    59.8 3897.82   111.8 3895.72
133.0941 3888.18   147.5 3887.35154.09313888.048   168.7 3889.58   187.9 3889.24
   199.9  3891.1   259.9 3891.47   275.9 3890.23     300 3891.52   327.9 3889.69
   372.3 3891.27   432.1 3891.26   445.9 3888.85   478.1 3887.78   488.1 3891.09
   534.5  3890.5   551.7 3889.31   560.9 3890.91   611.5 3891.74   625.3 3893.06
   640.1 3901.22   663.6 3908.32   675.3 3913.34   706.7 3918.76   722.4 3922.52
#Mann= 6 ,-1,0
       0     .12       0133.0941    .045       0154.0931     .12       0
     310      .1       0  519.67     .12       0  589.67      .1       0
#XS Ineff= 2 , 0
                          362.51         3901.12
Permanent Ineff=
       F       F
Bank Sta=133.0941,154.0931
XS Rating Curve= 0 ,0
Exp/Cntr(USF)=0,0
Exp/Cntr=0.3,0.1

Type RM Length L Ch R = 1 ,41582   ,304.4,302.5,291.6
XS GIS Cut Line= 3
2265774.16823709 526999.344294592266089.42846572526841.714180274
2266404.68869435526843.709498177
#Sta/Elev= 30
       0 3892.39    82.7 3890.41   128.3 3887.53   149.8 3887.79   163.2 3886.55
   203.5 3887.41   225.9 3886.37   233.73885.232   246.3 3884.94   250.1 3885.19
   271.4 3886.91     284 3886.48   292.9 3885.19   310.8 3885.91   328.1 3885.28
   337.7 3888.23   367.2 3890.01   395.2 3885.83   419.2 3885.79   435.2  3886.9
   463.2 3885.79   487.2 3886.01   495.2 3888.18   515.2 3902.08   524.8 3906.08
   563.2 3912.72   583.2 3915.25   595.2 3917.88   603.2 3918.03   667.7 3924.98
#Mann= 6 ,-1,0
       0     .12       0     140      .1       0   233.7    .045       0
   250.1      .1       0  362.47     .12       0  462.47      .1       0
#XS Ineff= 2 , 0
          176.84 3893.24
Permanent Ineff=
       F       F
Bank Sta=233.7,250.1
XS Rating Curve= 0 ,0
Exp/Cntr(USF)=0,0
Exp/Cntr=0.3,0.1

Type RM Length L Ch R = 1 ,41279   ,101.6,106.3,112.9
XS GIS Cut Line= 4
2265844.00436368 527021.292791522266157.26927441  527079.1570107
2266245.06326213526969.4145260492266408.67933016 526955.44730073
#Sta/Elev= 30
       0 3894.19    30.9 3892.46    40.9 3893.59    57.1 3891.29    77.5 3892.62
   130.3 3888.78     160 3888.29   175.2 3887.78   211.7 3889.05     289 3888.53
   313.4  3887.5   336.5 3888.11     357 3885.97   374.4 3886.17   384.6 3884.72
   393.6 3885.01   408.2 3883.81     416 3882.16   423.5 3881.73   438.5 3882.13
   444.9 3884.66   459.1 3894.45   466.2 3897.86   478.3 3901.91   506.4 3908.79
   522.4 3910.66   562.6 3918.22   578.6 3919.31   598.7 3925.85   623.3  3924.5
#Mann= 6 ,-1,0
       0     .12       0     160      .1       0     260     .12       0
     416    .045       0   438.5     .12       0   609.1      .1       0
Bank Sta=416,438.5
XS Rating Curve= 0 ,0
Exp/Cntr(USF)=0,0
Exp/Cntr=0.3,0.1

Type RM Length L Ch R = 1 ,41173   ,133.7,135.9,139.1
XS GIS Cut Line= 3
2265851.98563529527029.2740631312266247.05858003527105.096143435
2266406.68401225527001.339612493
#Sta/Elev= 30
       0 3892.78    20.6 3890.48    32.8 3891.88      45 3889.76    61.3 3890.73
    73.5 3892.48    85.7 3892.67   119.7  3889.1     155 3888.06   236.4  3889.1
     322 3887.65   348.6 3885.74   362.3 3886.13   374.9    3883     379 3882.81
   399.3 3884.89   413.2 3884.77     4303881.981     437 3881.38   453.5 3881.91
   460.9  3885.5   474.5 3898.23   478.2 3900.63   489.5 3906.13   504.2 3911.04
   526.9 3916.99   551.5 3919.08     561 3922.12   570.6 3924.02   592.7 3924.03
#Mann= 7 ,-1,0
       0     .12       0     150      .1       0     250     .12       0
     270      .1       0     350     .12       0     430    .045       0
   453.5      .1       0
Bank Sta=430,453.5
XS Rating Curve= 0 ,0
Exp/Cntr(USF)=0,0
Exp/Cntr=0.3,0.1

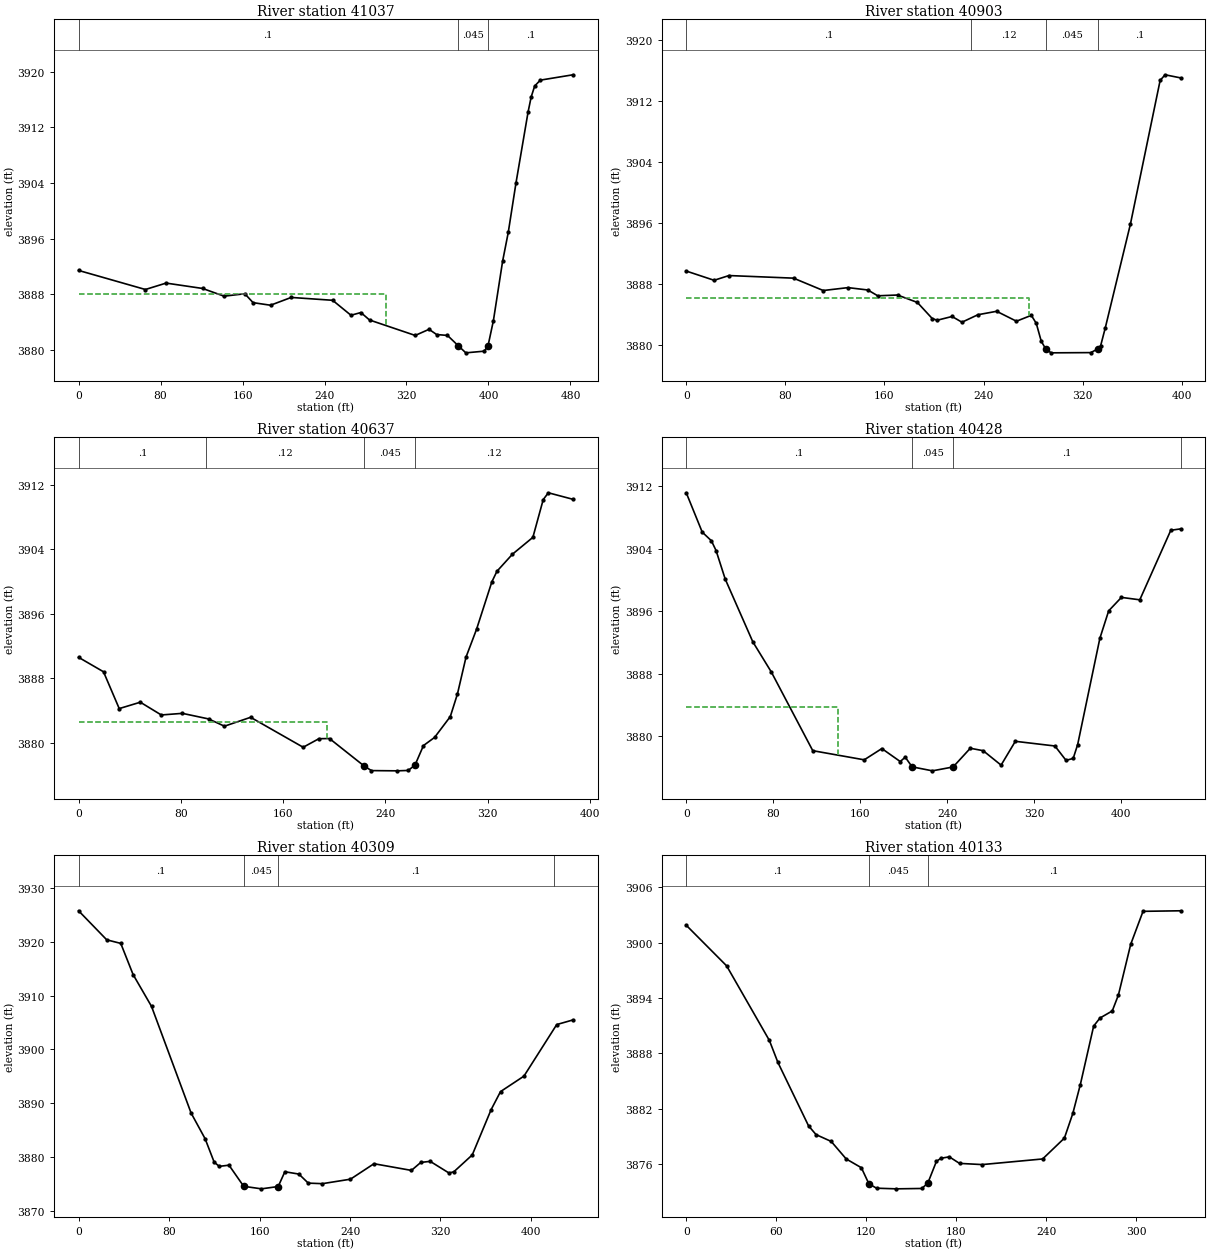
Type RM Length L Ch R = 1 ,41037   ,123.5,133.9,148.8
XS GIS Cut Line= 3
2265995.64852429527246.7637145292266192.61283925527275.668228872
2266445.47023874527147.738441492
#Sta/Elev= 30
       0 3891.43    65.2 3888.69    85.4 3889.61     121 3888.84     142 3887.73
   162.2 3888.08   170.3  3886.8   187.3 3886.43   207.5 3887.55   247.9 3887.14
   265.8 3884.99   275.5 3885.38   283.9 3884.31   328.5 3882.09     342 3882.97
   349.4 3882.22     360 3882.09   370.3 3880.64   377.9 3879.59   395.8 3879.83
   399.5 3880.56   404.8 3884.21   413.8 3892.76   419.3 3896.89   426.8 3903.96
   438.7 3914.24   441.7 3916.37   445.1 3917.93   450.6 3918.77   482.5 3919.54
#Mann= 3 ,-1,0
       0      .1       0   370.3    .045       0   399.5      .1       0
#XS Ineff= 2 , 0
          300.28 3888.05
Permanent Ineff=
       F       F
Bank Sta=370.3,399.5
XS Rating Curve= 0 ,0
Exp/Cntr(USF)=0,0
Exp/Cntr=0.3,0.1

Type RM Length L Ch R = 1 ,40903   ,259.4,265.9,272.9
XS GIS Cut Line= 2
2266065.62943115 527321.386149852266464.83268395527326.234772354
#Sta/Elev= 30
       0 3889.74    22.5 3888.53    34.5 3889.15    86.6 3888.81   110.6 3887.19
   130.6 3887.57   146.6 3887.26   154.6  3886.5   170.6  3886.6   186.6 3885.63
   198.6 3883.52   202.6  3883.3   214.6 3883.79   222.6 3883.04   235.5 3884.02
   250.6 3884.47   266.6 3883.17   278.6 3883.94   282.6 3882.89   286.6 3880.56
   290.3 3879.52   294.6 3879.03   326.6 3879.06   332.63879.571   334.6 3879.98
   338.3 3882.29   358.6 3895.88   382.6  3914.7   386.6 3915.44   399.2 3915.03
#Mann= 4 ,-1,0
       0      .1       0     230     .12       0   290.3    .045       0
   332.6      .1       0
#XS Ineff= 2 , 0
          276.69 3886.15
Permanent Ineff=
       F       F
Bank Sta=290.3,332.6
XS Rating Curve= 0 ,0
Exp/Cntr(USF)=0,0
Exp/Cntr=0.3,0.1

Type RM Length L Ch R = 1 ,40637   ,206.9,209.7,212.9
XS GIS Cut Line= 3
2266101.18599618527531.4931250082266401.80059141527602.606255062
2266479.37855146527596.141425057
#Sta/Elev= 30
       0 3890.62    19.5 3888.83    31.8 3884.27    48.3 3885.06    64.7 3883.48
    81.2 3883.68   101.7 3882.99   114.1 3882.09   134.6 3883.19   175.7 3879.48
     188 3880.54   196.3 3880.56   223.3 3877.17   229.1 3876.59   249.4 3876.56
   257.9 3876.61   263.2 3877.28   269.8 3879.69   278.5  3880.7   290.8 3883.28
   296.4 3886.09   303.1 3890.65   311.3 3894.08   323.3 3899.97   327.3 3901.28
   339.4 3903.39   355.4 3905.48   363.5 3910.16   367.5    3911   386.8 3910.19
#Mann= 4 ,-1,0
       0      .1       0     100     .12       0   223.3    .045       0
   263.2     .12       0
#XS Ineff= 2 , 0
          194.02 3882.61
Permanent Ineff=
       F       F
Bank Sta=223.3,263.2
XS Rating Curve= 0 ,0
Exp/Cntr(USF)=0,0
Exp/Cntr=0.3,0.1

Type RM Length L Ch R = 1 ,40428   ,133.4,118.8,102.9
XS GIS Cut Line= 3
2266054.31597864527710.8921576432266343.61712136527811.097022719
2266489.07579647527782.005287697
#Sta/Elev= 30
       0 3911.15    14.7 3906.11    23.1 3905.01    27.4 3903.76    35.8 3900.11
    61.2 3892.07    78.2 3888.21   116.3 3878.14   163.6 3876.97   179.8 3878.41
   196.7 3876.75   201.3 3877.31   207.6 3876.07   226.3 3875.56   245.4 3876.06
   245.4 3876.07   261.1 3878.45   272.9 3878.14   289.4 3876.29   302.5 3879.34
   338.9 3878.74   349.1  3876.9   355.7 3877.15   359.8 3878.93   380.2 3892.52
   388.3 3896.04     400 3897.76   416.9 3897.45   445.4 3906.35   454.5 3906.53
#Mann= 4 ,-1,0
       0      .1       0   207.6    .045       0   245.4      .1       0
   454.5     .12       0
#XS Ineff= 2 , 0
          139.87  3883.7
Permanent Ineff=
       F       F
Bank Sta=207.6,245.4
XS Rating Curve= 0 ,0
Exp/Cntr(USF)=0,0
Exp/Cntr=0.3,0.1

Type RM Length L Ch R = 1 ,40309   ,184.8,176.1,166.3
XS GIS Cut Line= 2
2266080.17529866527940.3936228162266502.00545648527825.642890229
#Sta/Elev= 30
       0 3925.72    24.9 3920.33    37.3 3919.67    48.2 3913.89    64.5 3907.98
    99.5 3888.19   111.9 3883.42   119.9 3879.08   124.4  3878.3     133 3878.52
     146  3874.6   161.7 3874.13   176.53874.558   182.4  3877.3   194.8 3876.87
   203.1 3875.19   215.6 3875.09   240.4 3875.92   261.2 3878.79   294.3 3877.55
   302.6 3879.03   310.9 3879.23   327.5 3877.07   331.8 3877.29   348.1 3880.42
   364.8 3888.83   373.1 3892.17   393.8 3895.04   422.8 3904.61   437.2 3905.47
#Mann= 4 ,-1,0
       0      .1       0     146    .045       0   176.5      .1       0
     420     .12       0
Bank Sta=146,176.5
XS Rating Curve= 0 ,0
Exp/Cntr(USF)=0,0
Exp/Cntr=0.3,0.1

Type RM Length L Ch R = 1 ,40133   ,177.9,183.2,191.8
XS GIS Cut Line= 3
2266243.41225629528110.0954104432266455.13543895527948.474660322
2266516.55132399527933.928792811
#Sta/Elev= 30
       0 3901.89    26.9 3897.49    55.4  3889.4    61.1 3887.01    81.5 3880.14
    86.5 3879.19    96.6 3878.45   106.6 3876.55   116.7  3875.6   121.7 3873.86
   126.8 3873.38   139.9 3873.31     157 3873.35     161 3873.94   166.7 3876.28
   169.6 3876.62   175.3 3876.78   182.1 3876.07   197.2 3875.94   237.5 3876.55
     252 3878.81   257.6 3881.48   262.6  3884.6   271.5 3890.96   275.7 3891.83
   283.9  3892.6     288 3894.33   296.2 3899.83   304.4  3903.4   329.5 3903.46
#Mann= 3 ,-1,0
       0      .1       0   121.7    .045       0     161      .1       0
Bank Sta=121.7,161
XS Rating Curve= 0 ,0
Exp/Cntr(USF)=0,0
Exp/Cntr=0.3,0.1

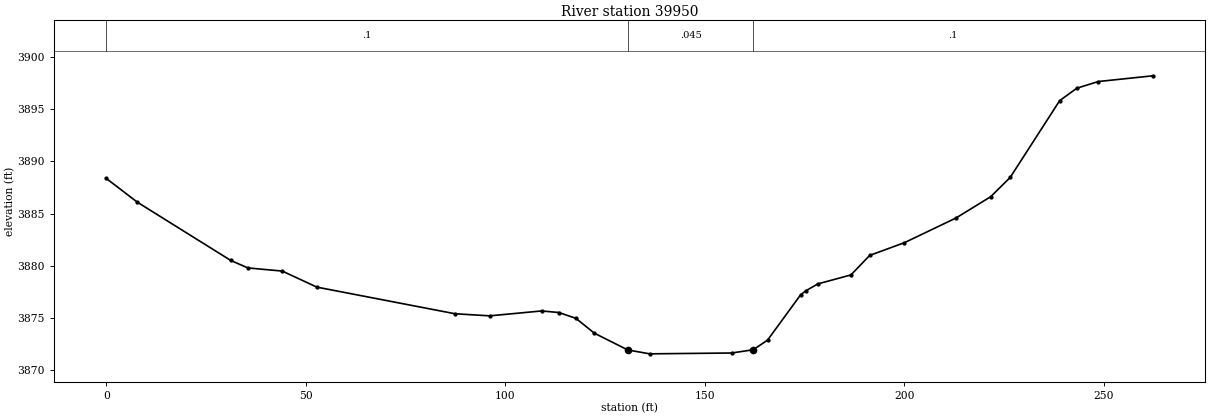
Type RM Length L Ch R = 1 ,39950   ,382.2,384,389.7
XS GIS Cut Line= 2
2266319.37400884528236.1595955382266561.80513403528135.954730463
#Sta/Elev= 30
       0 3888.38     7.8  3886.1    31.2 3880.52    35.5  3879.8    44.1  3879.5
    52.8 3877.96    87.4 3875.41    96.1 3875.21   109.1 3875.68   113.4 3875.53
   117.7 3874.97   122.3 3873.55   130.7 3871.94   136.2 3871.57   156.7 3871.65
   162.1 3871.96   165.7 3872.88     174 3877.23   175.3 3877.61   178.3 3878.27
   186.6 3879.13   191.3    3881     200 3882.22   212.9 3884.58   221.6 3886.62
   226.5 3888.47   238.9 3895.83   243.2 3897.02   248.6 3897.66   262.3 3898.21
#Mann= 3 ,-1,0
       0      .1       0   130.7    .045       0   162.1      .1       0
Bank Sta=130.7,162.1
XS Rating Curve= 0 ,0
Exp/Cntr(USF)=0,0
Exp/Cntr=0.3,0.1