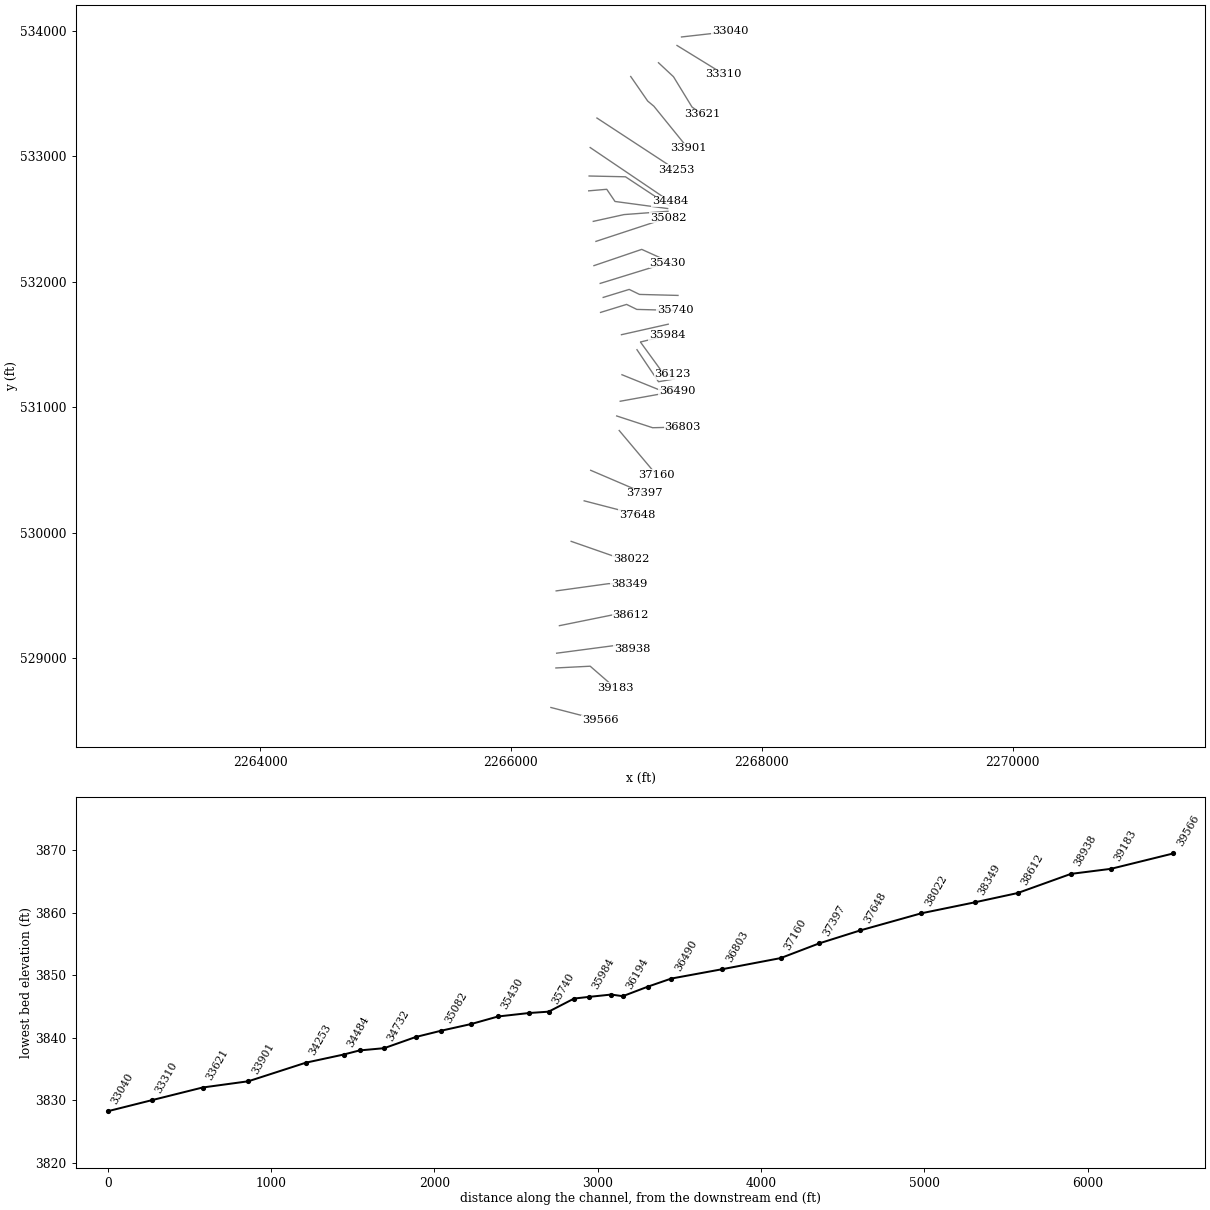
HEC-RAS study SHVRSFK.prj: SHVRSFK

--- SHVRSFK.g01 (geometry) --- (continued)

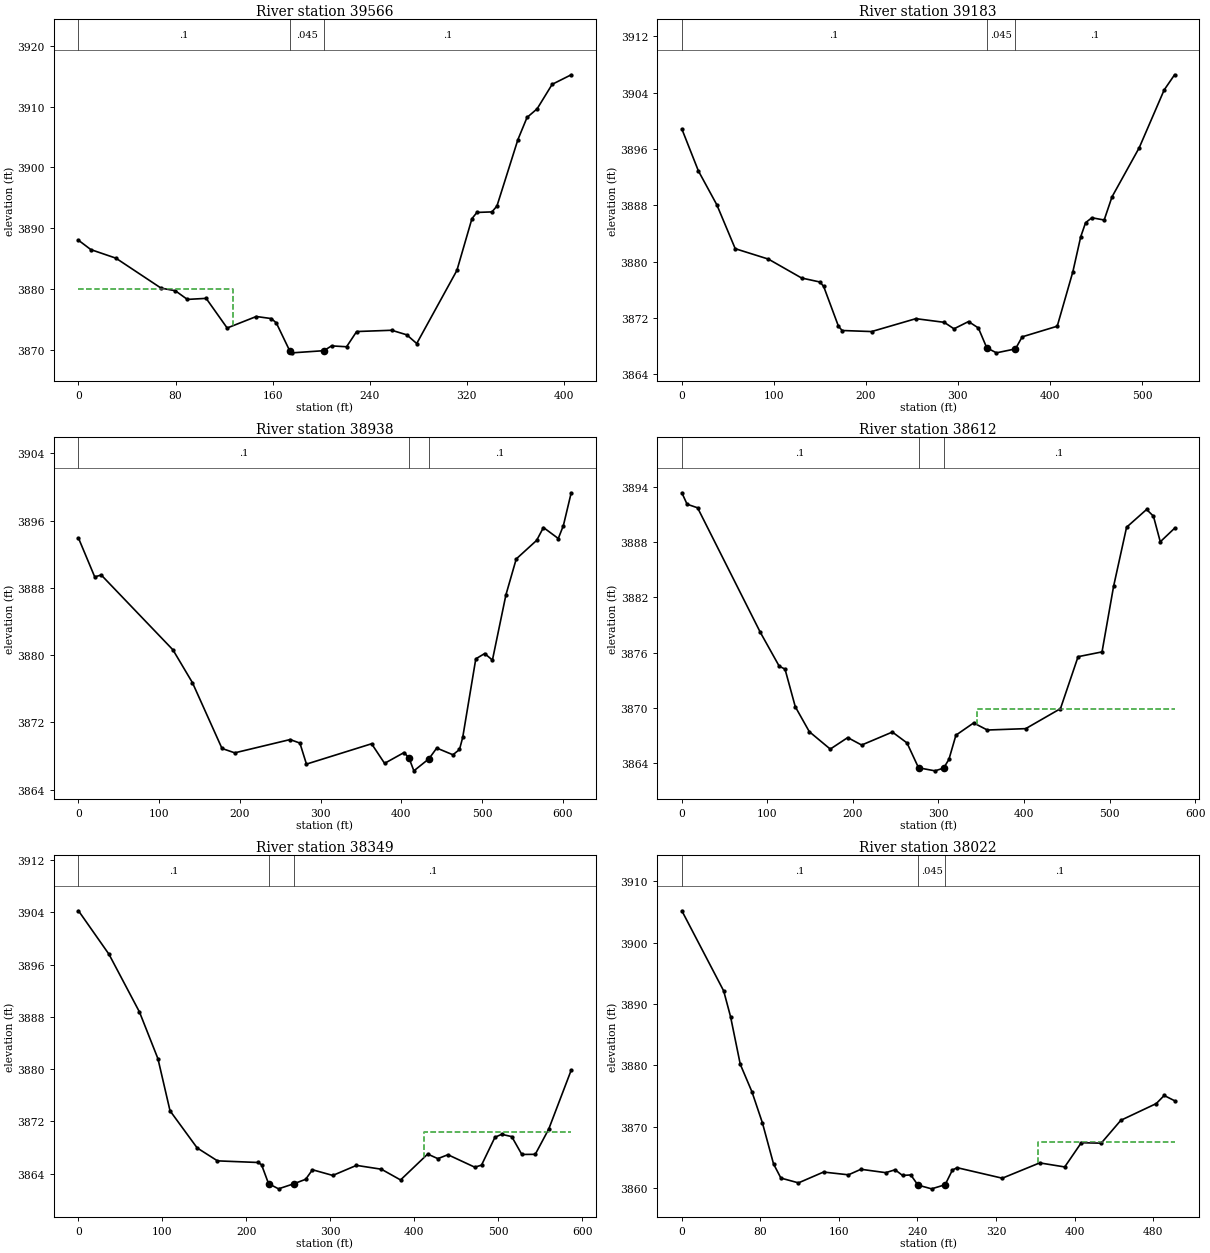
Type RM Length L Ch R = 1 ,39566   ,393.8,382.8,371
XS GIS Cut Line= 2
2266318.33644353528604.6149994572266711.41407037528502.853786417
#Sta/Elev= 30
       0 3888.03    10.2 3886.49    30.8 3885.09      68 3880.17    79.8 3879.73
    89.7 3878.31   105.2 3878.48   122.5 3873.61   146.5  3875.5   158.9 3875.16
     163 3874.45     1743869.886   176.2 3869.53   202.23869.885   208.5 3870.67
   220.9 3870.53   229.2 3873.03   258.1 3873.24   270.5 3872.49   278.7 3871.06
   311.8 3883.07   324.2 3891.58   328.3  3892.6   340.7 3892.69   344.8 3893.65
   362.1 3904.58   369.6 3908.21   377.9 3909.62   390.3 3913.65     406 3915.22
#Mann= 3 ,-1,0
       0      .1       0     174    .045       0   202.2      .1       0
#XS Ineff= 2 , 0
          127.37 3880.04
Permanent Ineff=
       F       F
Bank Sta=174,202.2
XS Rating Curve= 0 ,0
Exp/Cntr(USF)=0,0
Exp/Cntr=0.3,0.1

Type RM Length L Ch R = 1 ,39183   ,227.4,245,266.6
XS GIS Cut Line= 3
2266358.24280159528919.8752280892266631.60135426528933.842453408
2266829.13782663528762.245113773
#Sta/Elev= 30
       0 3898.83      18 3892.87      38 3888.07      58 3881.84    94.1 3880.36
   130.1 3877.68   150.1 3877.11   154.1 3876.48   170.2 3870.82   174.2 3870.23
   206.2 3870.08   254.3 3871.91   285.1 3871.39   295.7 3870.47   311.5  3871.5
   322.2 3870.59   331.3 3867.78   341.8 3867.06   362.5 3867.62   369.8 3869.33
   407.9 3870.84   424.9 3878.58   433.4 3883.52   438.7 3885.53   445.5 3886.23
   458.9 3885.91   467.4 3889.19     497 3896.17   524.1 3904.37   535.4 3906.52
#Mann= 3 ,-1,0
       0      .1       0   331.3    .045       0   362.5      .1       0
Bank Sta=331.3,362.5
XS Rating Curve= 0 ,0
Exp/Cntr(USF)=0,0
Exp/Cntr=0.3,0.1

Type RM Length L Ch R = 1 ,38938   ,324.2,326.3,320
XS GIS Cut Line= 3
 2266364.2287553 529037.598984352266863.05823098 529103.44447514
2266964.81944402529069.524070794
#Sta/Elev= 30
       0 3893.93    20.1 3889.32    28.2 3889.54     117 3880.64   141.2 3876.73
   177.8 3868.91   193.6 3868.39   262.2 3869.97   274.3 3869.55   282.4 3867.05
   363.1 3869.47   379.2 3867.14   403.4 3868.43   409.5 3867.76   415.5 3866.25
   434.23867.687   443.8 3868.96   463.9 3868.16     472 3868.79     476 3870.23
   492.2 3879.57   503.2  3880.2   512.8 3879.42   529.6 3887.21   542.3 3891.45
   567.6 3893.66     576 3895.19   594.4 3893.88   600.7 3895.42   610.4 3899.32
#Mann= 3 ,-1,0
       0      .1       0   409.5    .045       0   434.2      .1       0
Bank Sta=409.5,434.2
XS Rating Curve= 0 ,0
Exp/Cntr(USF)=0,0
Exp/Cntr=0.3,0.1

Type RM Length L Ch R = 1 ,38612   ,264.7,263,261.4
XS GIS Cut Line= 3
2266386.17725223529257.0839536512266839.11441615529348.868577177
 2266952.8475366529342.882623469
#Sta/Elev= 30
       0 3893.36     6.1 3892.12    18.4 3891.73    91.8  3878.2   113.8 3874.54
   120.6 3874.22   132.6 3870.14     149 3867.43   173.5 3865.54   193.9 3866.79
   210.2 3865.98   246.1 3867.39   263.2 3866.21   276.7 3863.51   295.9 3863.18
     3063863.476   312.2 3864.42   320.4 3867.05   341.1 3868.38   357.1 3867.61
     402 3867.76   442.6 3869.93   463.2 3875.57   491.2 3876.09   504.7  3883.2
   519.9 3889.62   543.3 3891.55   551.3 3890.82   559.3 3888.04     576 3889.51
#Mann= 3 ,-1,0
       0      .1       0   276.7    .045       0     306      .1       0
#XS Ineff= 2 , 0
                          344.89         3869.94
Permanent Ineff=
       F       F
Bank Sta=276.7,306
XS Rating Curve= 0 ,0
Exp/Cntr(USF)=0,0
Exp/Cntr=0.3,0.1

Type RM Length L Ch R = 1 ,38349   ,336.8,326.2,312
XS GIS Cut Line= 3
2266360.23811949529534.4331421312266779.25487907 529592.29736131
2266942.87094709529588.306725505
#Sta/Elev= 30
       0 3904.23    36.3 3897.58    72.6 3888.75    94.6  3881.6     109 3873.63
   141.3 3867.95   165.5 3865.97   213.9 3865.72     218 3865.37   226.3 3862.49
   238.2 3861.69   256.53862.471   270.5 3863.15   278.6 3864.61   302.8 3863.74
     331 3865.28   360.7 3864.69   383.5 3863.05   415.8 3867.01   427.9 3866.31
   439.9 3866.91   471.9    3865   479.9 3865.32   495.9 3869.58   503.9 3870.03
   515.9 3869.68   527.9 3866.95   543.9 3866.97     560 3870.85   586.7 3879.85
#Mann= 3 ,-1,0
       0      .1       0   226.3    .045       0   256.5      .1       0
#XS Ineff= 2 , 0
                          411.27         3870.42
Permanent Ineff=
       F       F
Bank Sta=226.3,256.5
XS Rating Curve= 0 ,0
Exp/Cntr(USF)=0,0
Exp/Cntr=0.3,0.1

Type RM Length L Ch R = 1 ,38022   ,371.9,373.9,374.5
XS GIS Cut Line= 3
2266479.95719366529929.5060868722266869.04418469529793.824469486
2266958.83349031529789.833833681
#Sta/Elev= 30
       0 3905.16    42.6 3892.13    49.6 3887.95    59.5  3880.2    71.4 3875.72
    82.1 3870.65    93.4 3863.99   100.9 3861.69   118.8 3860.91   144.3 3862.67
   169.7 3862.22   182.4 3863.12   207.7 3862.57   217.2 3863.04   224.8 3862.12
   233.2  3862.2   240.5 3860.55   254.4 3859.94   268.2 3860.61   275.6    3863
   280.4 3863.38   326.4 3861.67   364.5 3864.16     390  3863.5   406.9 3867.44
   427.2 3867.37   447.2 3871.09   483.3 3873.81   491.3 3875.12   501.9 3874.27
#Mann= 3 ,-1,0
       0      .1       0   240.5    .045       0   268.2      .1       0
#XS Ineff= 2 , 0
                          363.26         3867.49
Permanent Ineff=
       F       F
Bank Sta=240.5,268.2
XS Rating Curve= 0 ,0
Exp/Cntr(USF)=0,0
Exp/Cntr=0.3,0.1

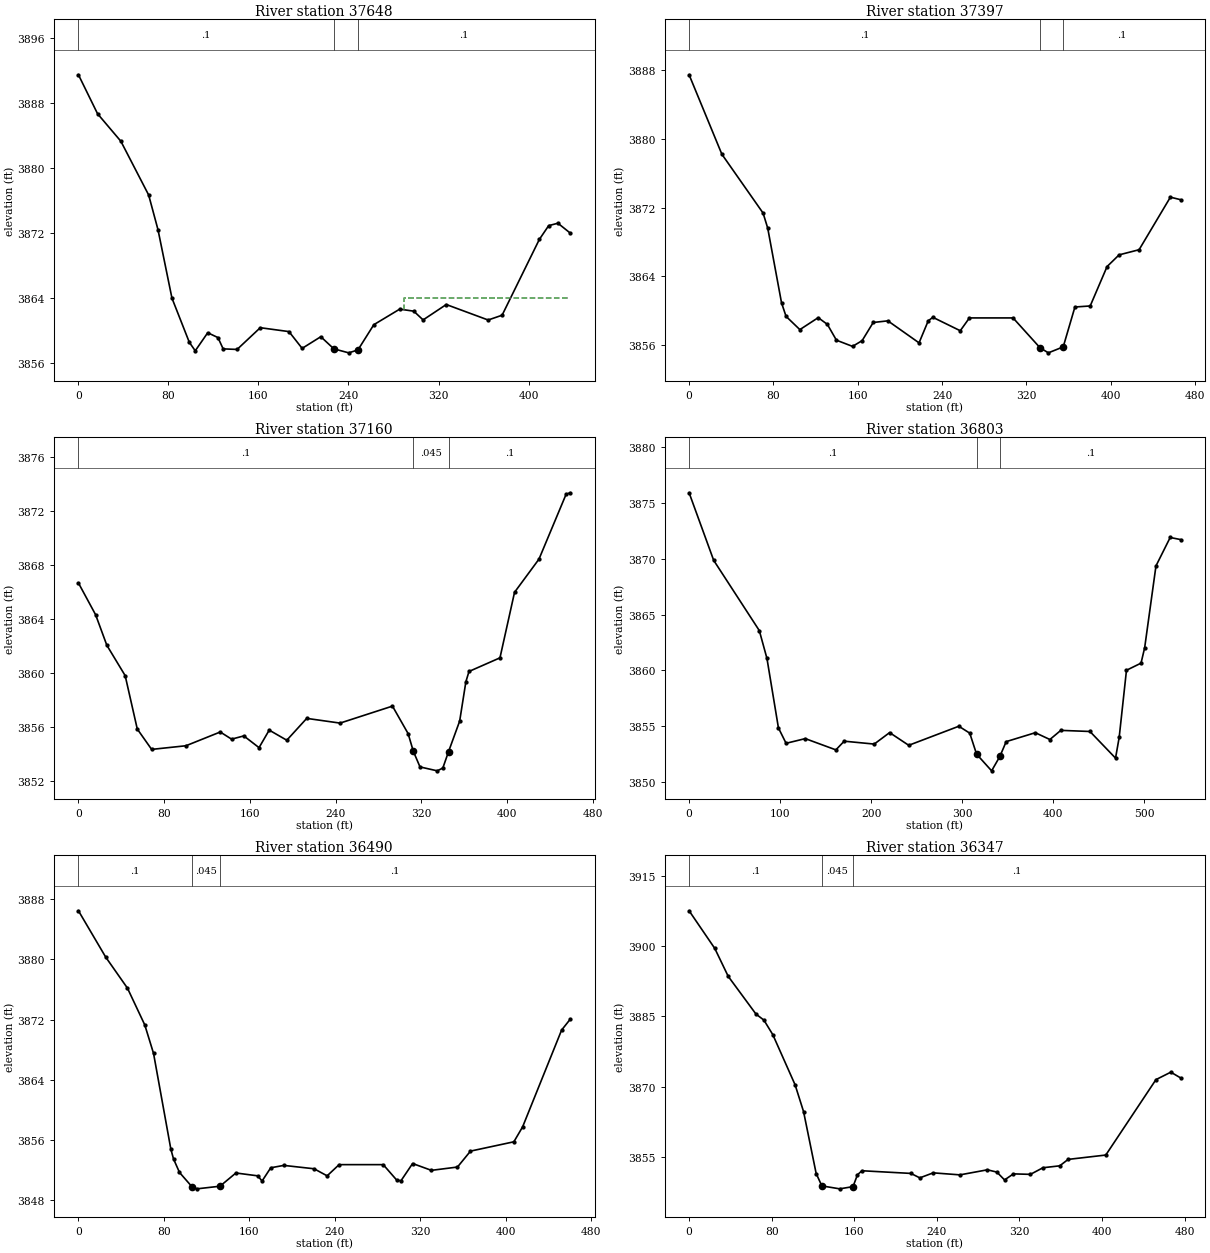
Type RM Length L Ch R = 1 ,37648   ,252.6,251.9,246.1
XS GIS Cut Line= 2
 2266583.7137246530252.7475871152267006.72111998530143.005102465
#Sta/Elev= 30
       0  3891.5      17 3886.69    37.7  3883.3    62.4 3876.67    70.7 3872.39
    83.1 3863.95    98.5 3858.51   103.8 3857.45   114.9 3859.68     124 3859.08
   128.6 3857.69     141 3857.62   161.6  3860.3   187.1 3859.82   198.8 3857.75
   215.4 3859.19     227 3857.69   240.2  3857.2   248.4 3857.56   262.5 3860.67
   285.5 3862.59     298 3862.34   306.3 3861.26   326.9 3863.16   364.1 3861.25
   376.5 3861.84   409.6 3871.19   417.9 3872.89   426.1 3873.19     437 3871.98
#Mann= 3 ,-1,0
       0      .1       0     227    .045       0   248.4      .1       0
#XS Ineff= 2 , 0
                          289.49         3863.94
Permanent Ineff=
       F       F
Bank Sta=227,248.4
XS Rating Curve= 0 ,0
Exp/Cntr(USF)=0,0
Exp/Cntr=0.3,0.1

Type RM Length L Ch R = 1 ,37397   ,248,236.2,224.8
XS GIS Cut Line= 2
2266635.59199007530496.1763712492267064.58533916530312.607124197
#Sta/Elev= 30
       0 3887.45    31.1 3878.21    70.2 3871.37    74.6 3869.62    87.7 3860.94
      92 3859.36   105.1 3857.82   122.5 3859.21   131.2 3858.43   139.8 3856.59
   155.1 3855.87   164.2 3856.54   174.7 3858.65   188.6 3858.84   218.2 3856.28
   226.9 3858.84   231.3 3859.25   257.3 3857.69     266 3859.18   307.4 3859.18
     333 3855.71   340.9 3855.12     3553855.814   366.1 3860.45   380.6 3860.57
   396.6 3865.15     408 3866.51     427 3867.11   456.7 3873.22   466.6 3872.92
#Mann= 3 ,-1,0
       0      .1       0     333    .045       0     355      .1       0
Bank Sta=333,355
XS Rating Curve= 0 ,0
Exp/Cntr(USF)=0,0
Exp/Cntr=0.3,0.1

Type RM Length L Ch R = 1 ,37160   ,335.3,357.8,379.7
XS GIS Cut Line= 2
2266863.05823098530813.4319177842267158.36528059530462.255966902
#Sta/Elev= 30
       0 3866.69      16 3864.34    26.5 3862.07    43.6 3859.82    54.9 3855.86
    68.3 3854.35   100.3 3854.62   132.3 3855.64   142.9 3855.11   154.3 3855.35
   168.5 3854.48     178 3855.78   194.4 3855.03     213 3856.65   244.1  3856.3
     293 3857.56   307.6 3855.52   312.5  3854.2   318.7 3853.05   334.8 3852.76
     340 3852.97   345.3 3854.18   355.7 3856.45   361.5 3859.37   364.4 3860.13
   393.3 3861.14   406.9    3866   429.7 3868.46     455 3873.27   458.8 3873.38
#Mann= 3 ,-1,0
       0      .1       0   312.5    .045       0   345.3      .1       0
Bank Sta=312.5,345.3
XS Rating Curve= 0 ,0
Exp/Cntr(USF)=0,0
Exp/Cntr=0.3,0.1

Type RM Length L Ch R = 1 ,36803   ,309.5,312.2,314.8
XS GIS Cut Line= 3
2266842.94213963530929.5972790672267129.43156743530835.764920081
2267367.87366037530841.366368422
#Sta/Elev= 30
       0 3875.92      27 3869.86    77.1 3863.56    85.5 3861.06    98.1 3854.83
   106.5 3853.45   127.6 3853.87   161.2 3852.86   170.3 3853.64   203.3 3853.38
   220.2 3854.41   241.2 3853.27   296.2 3854.98   308.2 3854.36315.6801 3852.48
   332.2 3850.98341.27943852.272   348.2  3853.6   380.2  3854.4   396.2 3853.79
   408.2 3854.61   440.2 3854.51   468.3 3852.12   472.3 3853.98   480.3    3860
   496.3 3860.64   500.3 3862.03   512.7 3869.36   528.3 3871.91     540 3871.72
#Mann= 3 ,-1,0
       0      .1       0315.6801    .045       0341.2794      .1       0
Bank Sta=315.6801,341.2794
XS Rating Curve= 0 ,0
Exp/Cntr(USF)=0,0
Exp/Cntr=0.3,0.1

Type RM Length L Ch R = 1 ,36490   ,154.8,143.9,128
XS GIS Cut Line= 2
2266871.03950259531046.8841124042267323.97666651531128.692146416
#Sta/Elev= 30
       0 3886.48    25.5 3880.32    45.9 3876.18    62.1 3871.29    70.3  3867.5
    86.5 3854.76      89 3853.46    94.6 3851.66   106.2 3849.77   110.9 3849.48
   132.5 3849.83   147.4 3851.59   167.8 3851.21   171.9 3850.52     180 3852.28
   192.2  3852.6   220.6 3852.15   232.8 3851.21     244  3852.7   285.3  3852.7
   297.9 3850.65   301.9 3850.55   312.8 3852.85   330.4 3851.94   354.8 3852.38
     367  3854.5   407.6 3855.74   415.8 3857.73   452.3 3870.61   460.3 3872.04
#Mann= 3 ,-1,0
       0      .1       0   106.2    .045       0   132.5      .1       0
Bank Sta=106.2,132.5
XS Rating Curve= 0 ,0
Exp/Cntr(USF)=0,0
Exp/Cntr=0.3,0.1

Type RM Length L Ch R = 1 ,36347   ,166,152.7,135.1
BEGIN DESCRIPTION:
Structure XS 4
END DESCRIPTION:
XS GIS Cut Line= 3
2266885.00672791531258.3878100932267180.31377752531138.668735929
2267335.94857393531164.607868665
#Sta/Elev= 30
       0  3907.5    24.9 3899.46    37.9 3893.51    64.8 3885.46    72.5 3884.17
    81.1 3881.07   102.7 3870.37   110.9 3864.65   123.1 3851.45   128.6 3848.81
   145.9 3848.18   158.8 3848.65   163.1 3851.17   167.4 3852.04   214.9 3851.47
   223.5 3850.52   236.5 3851.59   262.4 3851.16     289 3852.24   298.2 3851.75
   305.6 3850.08   314.2 3851.37   330.7 3851.27   342.8 3852.68   359.1 3853.09
   367.2 3854.46   403.7 3855.39   452.3 3871.48   466.7 3873.07   476.4 3871.82
#Mann= 3 ,-1,0
       0      .1       0   128.6    .045       0   158.8      .1       0
Bank Sta=128.6,158.8
XS Rating Curve= 0 ,0
Exp/Cntr(USF)=0,0
Exp/Cntr=0.5,0.3

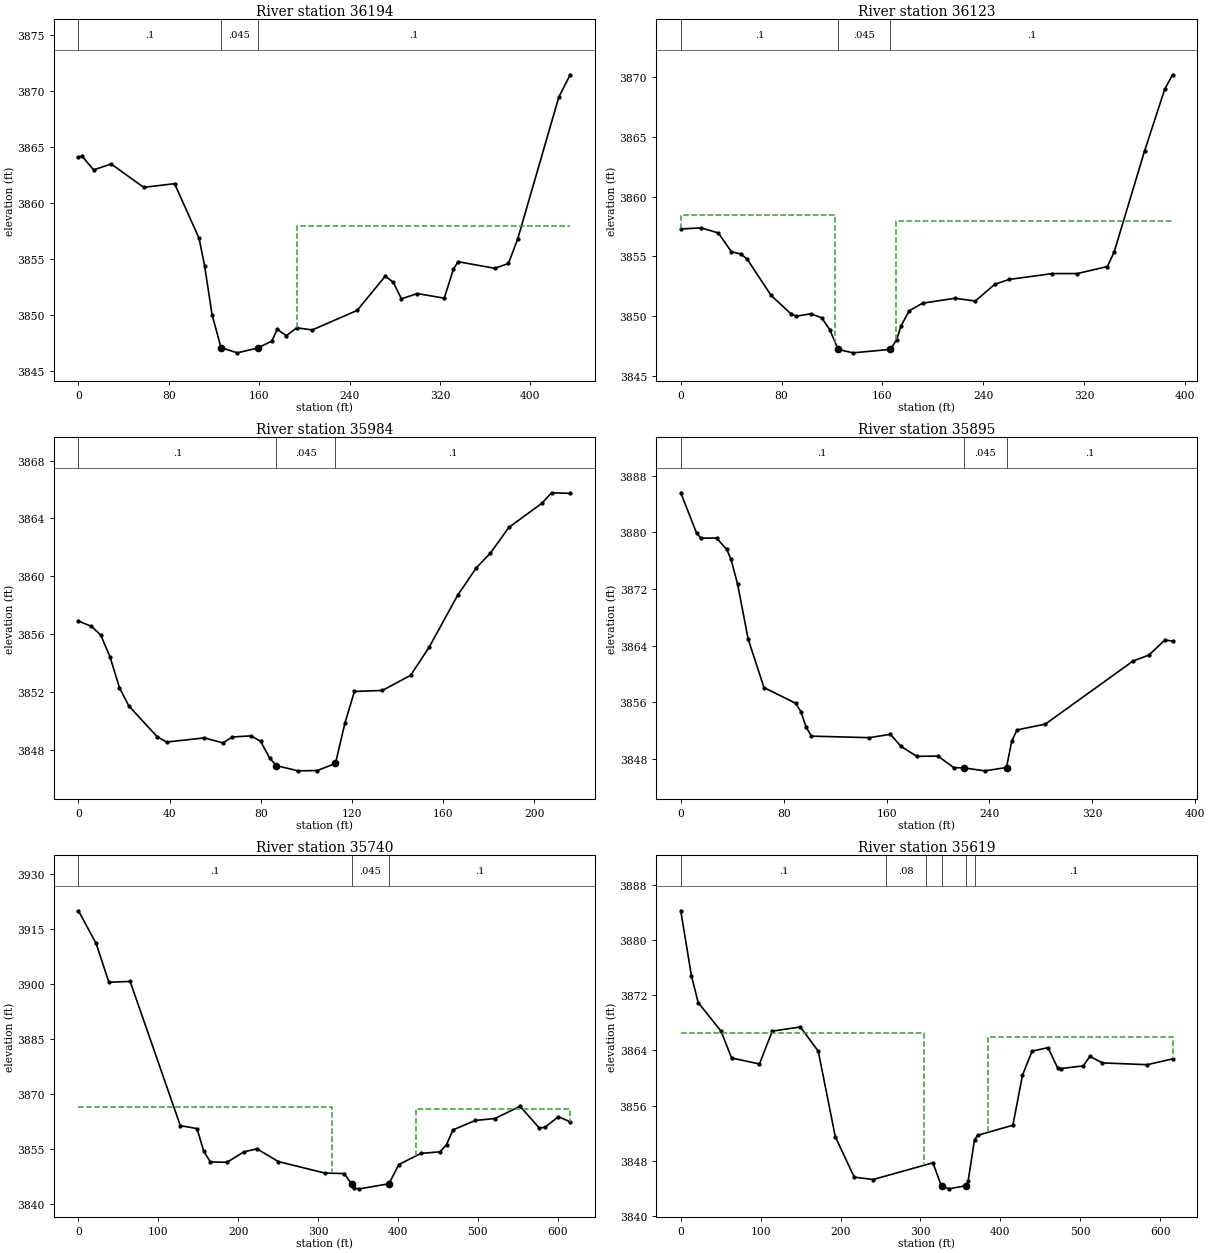
Type RM Length L Ch R = 1 ,36194   ,71.1,70.9,68.3
BEGIN DESCRIPTION:
Structure XS 3
END DESCRIPTION:
XS GIS Cut Line= 3
2267004.72580208531457.9196003672267176.32314171531202.518908817
2267302.02816958531224.467405747
#Sta/Elev= 30
       0 3864.07       3  3864.2    13.4 3862.96      29 3863.48    57.8  3861.4
    85.1 3861.73   106.8 3856.86   111.7  3854.4   118.3 3850.05   126.2 3847.12
   140.6 3846.66   158.7 3847.09   171.2 3847.71     176 3848.75     184 3848.19
   193.3 3848.89     207  3848.7   246.7 3850.44   271.6 3853.49   278.7 3852.94
   285.9 3851.47   299.9 3851.94   323.8 3851.53   331.9 3854.11     336 3854.78
   368.5 3854.19   380.6 3854.62   388.8  3856.8   425.3 3869.47   435.3 3871.43
#Mann= 3 ,-1,0
       0      .1       0   126.2    .045       0   158.7      .1       0
#XS Ineff= 2 , 0
            96.5  3858.5   193.5            3858
Permanent Ineff=
       F       F
Bank Sta=126.2,158.7
XS Rating Curve= 0 ,0
Exp/Cntr(USF)=0,0
Exp/Cntr=0.5,0.3

Type RM Length L Ch R = 1 ,36123   ,113.9,139.1,179.4
BEGIN DESCRIPTION:
Structure XS 2
END DESCRIPTION:
XS GIS Cut Line= 3
2267034.65557062531515.7838195462267226.20608928531252.401856385
2267290.05626217531262.378445899
#Sta/Elev= 30
       0 3857.29    16.2 3857.39    29.8 3856.96    40.2 3855.39    47.7  3855.2
    52.7 3854.77    71.7 3851.73    87.3  3850.2    91.7 3849.99   103.2 3850.19
   111.8 3849.86   118.2 3848.87     125  3847.2   136.8 3846.92   166.4 3847.21
   171.4 3848.03   174.8 3849.17   181.3 3850.44   191.9 3851.08   217.7 3851.49
   233.8 3851.26   249.2 3852.66   260.7 3853.07     295 3853.56   314.8 3853.56
   338.6 3854.15   343.9 3855.35   368.1 3863.82   384.1    3869   390.3 3870.21
#Mann= 3 ,-1,0
       0      .1       0     125    .045       0   166.4      .1       0
#XS Ineff= 2 , 0
           122.8  3858.5   171.2            3858
Permanent Ineff=
       F       F
Bank Sta=125,166.4
XS Rating Curve= 0 ,0
Exp/Cntr(USF)=0,0
Exp/Cntr=0.5,0.3

Type RM Length L Ch R = 1 ,35984   ,88.7,88.3,87.6
BEGIN DESCRIPTION:
Structure XS 1
END DESCRIPTION:
XS GIS Cut Line= 2
2267034.65557062531519.774455351 2267244.1639504531571.652720823
#Sta/Elev= 30
       0  3856.9     5.7 3856.53     9.8 3855.93    13.9  3854.4      18 3852.29
    22.1 3851.03    34.5 3848.91    38.7 3848.53    55.3 3848.82    63.4 3848.47
    67.5 3848.88    75.7 3848.96    79.9 3848.59      84  3847.4    86.93846.899
    96.3 3846.54   104.8 3846.56   112.8 3847.05   116.9 3849.82   121.1 3852.03
   133.4  3852.1   145.8 3853.15     154 3855.12   166.4 3858.68   174.6 3860.58
   180.8  3861.6   188.9 3863.38   203.5 3865.06   207.6 3865.77   215.8 3865.73
#Mann= 3 ,-1,0
       0      .1       0    86.9    .045       0   112.8      .1       0
Bank Sta=86.9,112.8
XS Rating Curve= 0 ,0
Exp/Cntr(USF)=0,0
Exp/Cntr=0.3,0.1

Type RM Length L Ch R = 1 ,35895   ,167.1,155.8,149.4
BEGIN DESCRIPTION:
Structure XS 4
END DESCRIPTION:
XS GIS Cut Line= 2
2266881.01609211531577.6386745312267254.14053992531661.442026446
#Sta/Elev= 30
       0 3885.61    12.3 3879.91    15.7 3879.19    27.8 3879.21    35.7 3877.61
    39.1 3876.19    44.2 3872.67    52.4 3864.93    64.7 3858.06    89.3 3855.84
    93.4 3854.66    97.5 3852.44   101.6 3851.19   146.7 3850.97     163 3851.45
   171.3 3849.73   183.6 3848.33     200 3848.37   212.3 3846.73   219.9  3846.7
   236.6 3846.28   253.3 3846.75   253.3 3846.77   257.4 3850.51   261.5 3852.07
   283.5 3852.89   351.7 3861.81     364 3862.65   376.3 3864.76   382.4 3864.65
#Mann= 3 ,-1,0
       0      .1       0   219.9    .045       0   253.3      .1       0
Bank Sta=219.9,253.3
XS Rating Curve= 0 ,0
Exp/Cntr(USF)=0,0
Exp/Cntr=0.5,0.3

Type RM Length L Ch R = 1 ,35740   ,120.4,121.2,121
BEGIN DESCRIPTION:
Structure XS 3
END DESCRIPTION:
XS GIS Cut Line= 4
2266714.35235594531755.3246133582266921.86541782531819.174786246
2267003.67345183531779.2684281912267310.95240885 531771.28715658
#Sta/Elev= 30
       0 3919.97    22.1 3911.06    38.1 3900.49    64.7 3900.71   127.5 3861.41
   148.4  3860.6   156.8 3854.44   165.1 3851.51     186 3851.42     207 3854.26
   223.3 3855.09   250.2 3851.61   308.6 3848.47   332.6 3848.35   341.9 3845.49
   344.7 3844.33   351.7 3844.18   388.6 3845.56     401 3850.81   428.7 3853.84
   452.7 3854.28   460.7 3856.23   468.7 3860.24   496.7 3862.82   521.3 3863.35
   552.7 3866.68   576.7 3860.79   583.7  3860.9   600.7 3863.86   615.5 3862.43
#Mann= 3 ,-1,0
       0      .1       0   341.9    .045       0   388.6      .1       0
#XS Ineff= 2 , 0
             317  3866.5     423            3866
Permanent Ineff=
       F       F
Bank Sta=341.9,388.6
XS Rating Curve= 0 ,0
Exp/Cntr(USF)=0,0
Exp/Cntr=0.5,0.3

Type RM Length L Ch R = 1 ,35619   ,180.7,188.2,196.8
BEGIN DESCRIPTION:
Structure XS 2
END DESCRIPTION:
XS GIS Cut Line= 4
2266735.35788521531874.9410420382266942.87094709531938.791214926
 2267024.6789811531898.8848568712267331.95793812 531890.90358526
#Sta/Elev= 30
       0 3884.21    13.4 3874.77    21.8 3870.93    50.4 3866.78    63.6 3862.91
    98.5 3862.03   114.5 3866.79   149.7 3867.39   172.1 3863.88   193.4 3851.52
   217.1 3845.65   240.8 3845.31   315.6 3847.73   326.4 3844.31   335.6 3843.96
   356.63844.412   359.6 3845.03   367.7  3851.1   371.6 3851.71   415.7 3853.17
   427.7 3860.42   439.7 3863.89   459.7  3864.4   471.7 3861.46   475.7 3861.37
   503.7 3861.76   512.1 3863.13   527.7 3862.19   583.7 3861.93   615.5 3862.77
#Mann= 6 ,-1,0
       0      .1       0  257.11     .08       0  307.11     .07       0
   326.4    .045       0   356.6     .07       0  368.14      .1       0
#XS Ineff= 2 , 0
             305  3866.5     385            3866
Permanent Ineff=
       F       F
Bank Sta=326.4,356.6
XS Rating Curve= 0 ,0
Exp/Cntr(USF)=0,0
Exp/Cntr=0.5,0.3

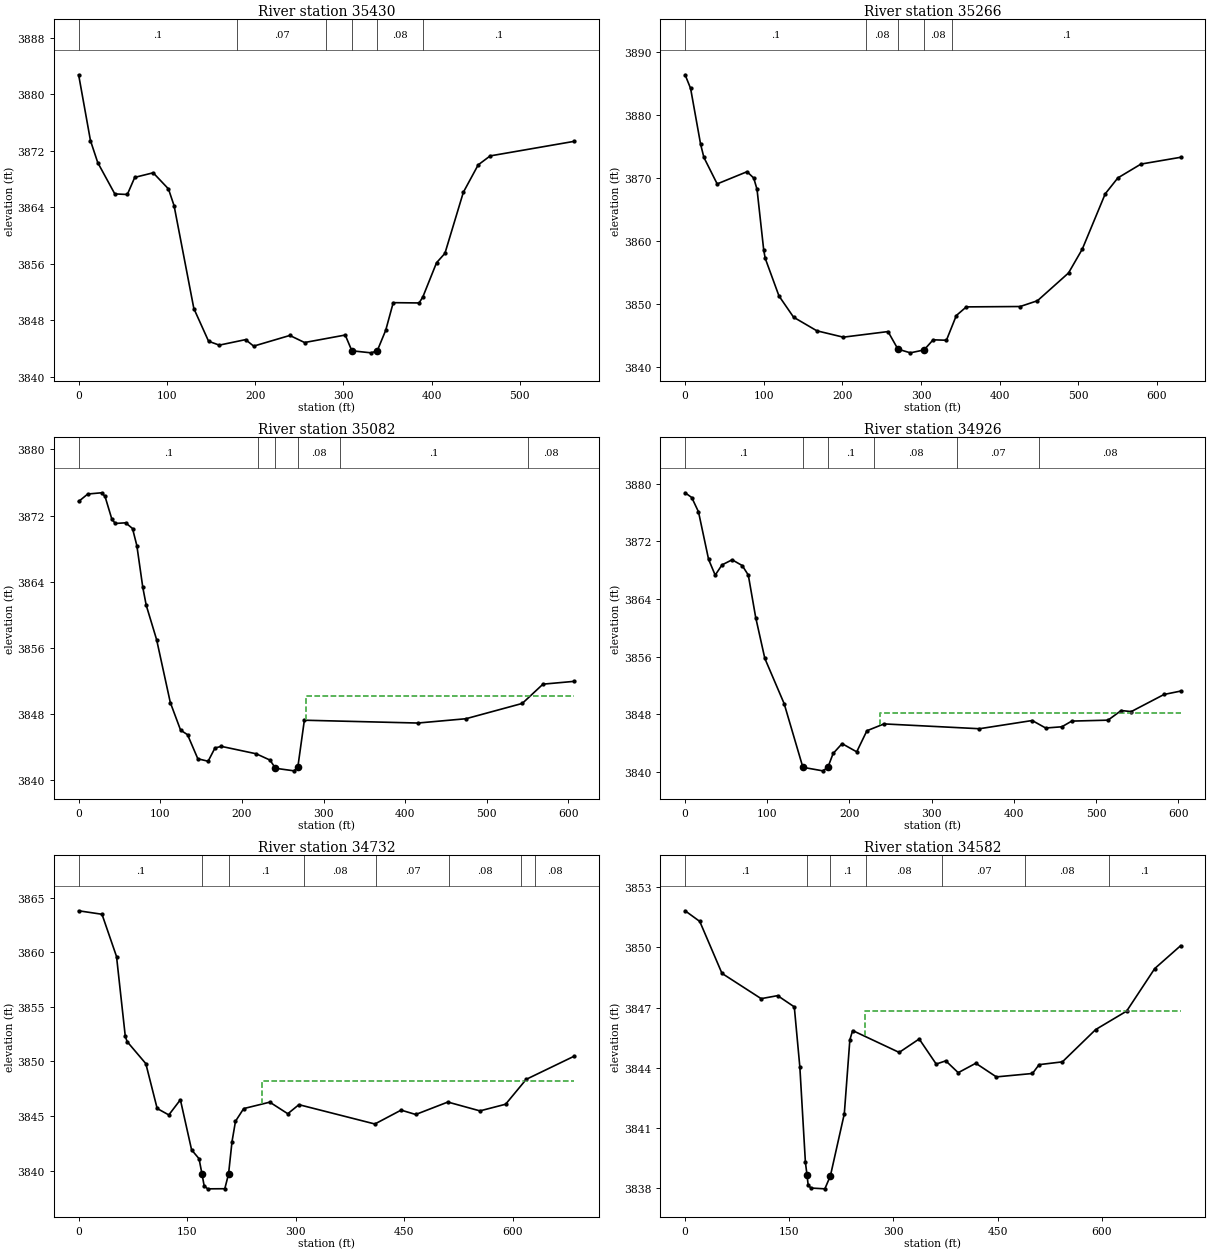
Type RM Length L Ch R = 1 ,35430   ,164.3,164.9,164.5
BEGIN DESCRIPTION:
Structure XS 1
END DESCRIPTION:
XS GIS Cut Line= 2
2266711.41407037531986.6788445912267248.15458621532152.290230518
#Sta/Elev= 30
       0 3882.76    13.4 3873.45    21.7 3870.32      41  3865.9    55.2 3865.82
    63.6 3868.24    84.5 3868.89   101.8 3866.61   108.2 3864.23   130.6 3849.68
   147.3 3845.05   159.4  3844.5   189.2 3845.28   198.4 3844.36   239.4 3845.87
   256.1 3844.87   302.2 3845.93   309.7  3843.7   331.5 3843.41   338.5  3843.7
   348.1 3846.61   356.6 3850.51   385.9 3850.47   390.1  3851.3   405.7 3856.16
   415.2 3857.49   436.1 3866.14   452.9 3870.01   466.5 3871.28   561.7 3873.34
#Mann= 6 ,-1,0
       0      .1       0     180     .07       0     280     .08       0
   309.7    .045       0   338.5     .08       0     390      .1       0
Bank Sta=309.7,338.5
XS Rating Curve= 0 ,0
Exp/Cntr(USF)=0,0
Exp/Cntr=0.3,0.1

Type RM Length L Ch R = 1 ,35266   ,184,183.7,181.5
XS GIS Cut Line= 3
2266661.53112281532128.3464156852267042.63684223532258.042079363
2267250.14990411532164.262137935
#Sta/Elev= 30
       0 3886.38       7 3884.21    19.7 3875.36    23.9 3873.25    40.8 3869.04
    78.8 3870.98    87.3 3869.97    91.5 3868.17     100 3858.53   101.9 3857.22
   119.4 3851.24     138 3847.86   167.6  3845.7   201.2 3844.69   258.1 3845.58
   270.7 3842.79   286.5  3842.2   303.9 3842.66   315.5 3844.27   332.4  3844.2
     345 3848.13   357.7  3849.5   426.2 3849.56   448.2 3850.48   487.7 3854.89
   505.2 3858.68   534.4 3867.47   550.4 3869.99   579.8 3872.19   630.3 3873.27
#Mann= 5 ,-1,0
       0      .1       0     230     .08       0   270.7    .045       0
   303.9     .08       0     340      .1       0
Bank Sta=270.7,303.9
XS Rating Curve= 0 ,0
Exp/Cntr(USF)=0,0
Exp/Cntr=0.3,0.1

Type RM Length L Ch R = 1 ,35082   ,162.7,155.9,156.3
XS GIS Cut Line= 2
2266677.49366603532321.8922522512267254.14053992 532511.44745301
#Sta/Elev= 30
       0  3873.7    11.2  3874.6    28.1 3874.75    32.3 3874.32    40.7 3871.56
    44.9 3871.04    57.6 3871.12      66 3870.43    71.3 3868.37    78.6 3863.31
    82.8 3861.15    95.5    3857   112.3 3849.39   124.9 3846.05   133.4  3845.5
     146 3842.59   158.6 3842.29     167 3843.89   174.7 3844.09   217.6 3843.19
   234.4 3842.43   241.1 3841.44   263.9 3841.13   268.53841.577   276.5 3847.25
   415.5 3846.91   474.4 3847.43   543.4 3849.28   568.8 3851.61     607 3851.95
#Mann= 6 ,-1,0
       0      .1       0     220     .08       0   241.1    .045       0
   268.5     .08       0     320      .1       0     550     .08       0
#XS Ineff= 2 , 0
                          278.64         3850.15
Permanent Ineff=
       F       F
Bank Sta=241.1,268.5
XS Rating Curve= 0 ,0
Exp/Cntr(USF)=0,0
Exp/Cntr=0.3,0.1

Type RM Length L Ch R = 1 ,34926   ,222.8,193.5,158.1
XS GIS Cut Line= 3
2266656.28691807532481.4279795582266901.33648898532535.539872189
2267252.29076405532561.822791467
#Sta/Elev= 30
       0 3878.75     8.1 3878.09    16.3  3876.1    28.6 3869.49    36.6 3867.31
    44.9 3868.73    57.2 3869.44    69.5 3868.64    76.9 3867.32    85.9 3861.42
      97 3855.74   120.5 3849.46   143.3 3840.61   167.5 3840.12   173.7  3840.6
   180.1 3842.53     191  3843.9   208.8 3842.76   221.2 3845.69     242 3846.64
   358.1 3845.97   422.3 3847.11   438.7 3846.07   458.4 3846.24   470.4 3847.03
   514.5 3847.16   530.6  3848.5   542.8 3848.35   582.7 3850.73   602.9  3851.2
#Mann= 6 ,-1,0
       0      .1       0   143.3    .045       0   173.7      .1       0
     230     .08       0  330.95     .07       0  430.95     .08       0
#XS Ineff= 2 , 0
                          237.23         3848.16
Permanent Ineff=
       F       F
Bank Sta=143.3,173.7
XS Rating Curve= 0 ,0
Exp/Cntr(USF)=0,0
Exp/Cntr=0.3,0.1

Type RM Length L Ch R = 1 ,34732   ,122.7,150.7,176
BEGIN DESCRIPTION:
Structure - abutments, no deck
END DESCRIPTION:
XS GIS Cut Line= 4
 2266619.9546473532724.9314963992266763.73767629   532737.299929
2266829.59990952532640.1409909452267249.37537134532583.798786959
#Sta/Elev= 30
       0  3863.8    32.3 3863.48    52.4 3859.61    64.5 3852.31      67 3851.82
    92.9  3849.8   108.6 3845.69   124.7  3845.1   140.7 3846.49   156.2  3841.9
   166.5 3841.09   170.6 3839.68   173.5 3838.63   178.3 3838.33   202.1 3838.34
   207.3 3839.69   212.1 3842.66   216.9 3844.52   228.2 3845.68   264.3 3846.27
   289.2 3845.21   304.6 3846.04   409.6 3844.27   445.9 3845.54   466.1 3845.14
   510.5 3846.28   554.9 3845.47   590.4 3846.08   618.9 3848.36   685.2 3850.48
#Mann= 8 ,-1,0
       0      .1       0   170.6    .045       0   207.3      .1       0
  311.69     .08       0  411.69     .07       0  511.69     .08       0
  611.69      .1       0  631.69     .08       0
#XS Ineff= 2 , 0
                          253.31         3848.23
Permanent Ineff=
       F       F
Bank Sta=170.6,207.3
XS Rating Curve= 0 ,0
Exp/Cntr(USF)=0,0
Exp/Cntr=0.5,0.3

Type RM Length L Ch R = 1 ,34582   ,114.6,97.4,83
BEGIN DESCRIPTION:
Structure - abutments, no deck
END DESCRIPTION:
XS GIS Cut Line= 3
2266623.04675545 532843.204633152266912.93189455532837.020416849
2267266.20525072532603.566251497
#Sta/Elev= 30
       0 3851.83    21.1  3851.3    53.1 3848.71   109.5 3847.45   133.2  3847.6
   157.2 3847.04   165.2 3844.04   173.2 3839.29   175.5 3838.67   177.2 3838.15
   181.2 3838.01   201.2 3837.97   209.2 3838.62   229.2 3841.71   237.2  3845.4
   241.2 3845.86   308.2 3844.77     337 3845.44   361.5 3844.19   375.3 3844.35
   393.2 3843.76   418.5 3844.23   448.1 3843.55   500.1 3843.72   509.6 3844.16
   543.2  3844.3   591.1 3845.91   635.7 3846.83   676.1 3848.95   713.4 3850.09
#Mann= 7 ,-1,0
       0      .1       0   175.5    .045       0   209.2      .1       0
     260     .08       0  369.95     .07       0  489.95     .08       0
  609.95      .1       0
#XS Ineff= 2 , 0
                          258.32         3846.83
Permanent Ineff=
       F       F
Bank Sta=175.5,209.2
XS Rating Curve= 0 ,0
Exp/Cntr(USF)=0,0
Exp/Cntr=0.5,0.3

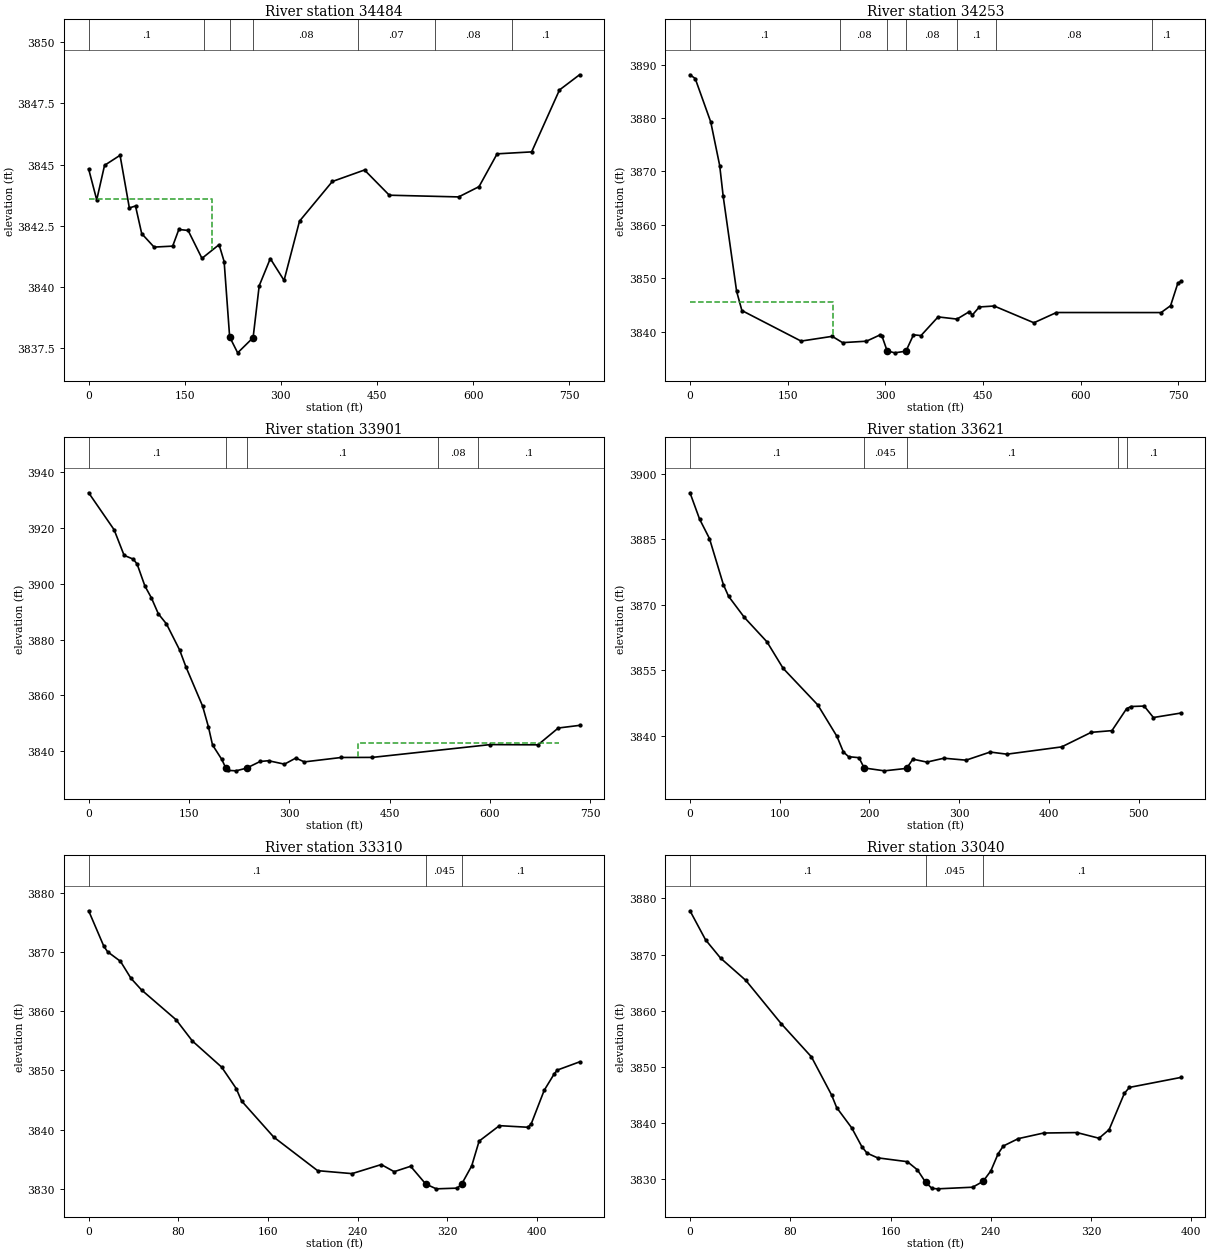
Type RM Length L Ch R = 1 ,34484   ,230.2,230.9,231.4
XS GIS Cut Line= 2
2266631.60135426533070.1364657762267266.11244733532641.143116688
#Sta/Elev= 30
       0 3844.82    12.6 3843.56    24.8 3844.97      49 3845.38    63.5 3843.23
    73.1 3843.31    82.8 3842.18   102.1 3841.63   131.1 3841.67   140.7 3842.35
   155.2 3842.31   176.8 3841.17   203.5 3841.73   211.4 3841.04     220 3837.96
   232.5 3837.31   256.6 3837.93   266.1 3840.05   283.4 3841.16   304.9 3840.27
     329 3842.69   380.2 3844.31   430.4 3844.78   469.1 3843.75   577.3 3843.68
   609.1  3844.1   637.3 3845.44   691.2 3845.52   734.6 3848.05   765.9 3848.67
#Mann= 7 ,-1,0
       0      .1       0     180     .08       0     220    .045       0
   256.6     .08       0     420     .07       0     540     .08       0
     660      .1       0
#XS Ineff= 2 , 0
          193.18 3843.61
Permanent Ineff=
       F       F
Bank Sta=220,256.6
XS Rating Curve= 0 ,0
Exp/Cntr(USF)=0,0
Exp/Cntr=0.3,0.1

Type RM Length L Ch R = 1 ,34253   ,363.5,352.6,345.2
XS GIS Cut Line= 2
2266685.47493764533305.583978298 2267315.9953949532892.553172432
#Sta/Elev= 30
       0 3888.08       8 3887.38    31.9 3879.23    45.6 3871.09      51 3865.31
    71.6 3847.53    79.7 3843.93   170.6 3838.21   218.4  3839.1   234.3 3837.92
     271 3838.19   291.2 3839.33   294.9 3839.12   302.7 3836.39   314.3 3836.01
   331.6 3836.32   343.2 3839.39   354.7 3839.24     381 3842.74     410 3842.33
   428.8 3843.71   433.6  3843.1   444.3  3844.6   467.1 3844.78   528.1 3841.64
   562.7 3843.56   723.4 3843.55     738 3844.84   749.2 3849.07   753.8 3849.38
#Mann= 7 ,-1,0
       0      .1       0     230     .08       0   302.7    .045       0
   331.6     .08       0     410      .1       0     470     .08       0
     710      .1       0
#XS Ineff= 2 , 0
           219.9 3845.59
Permanent Ineff=
       F       F
Bank Sta=302.7,331.6
XS Rating Curve= 0 ,0
Exp/Cntr(USF)=0,0
Exp/Cntr=0.3,0.1

Type RM Length L Ch R = 1 ,33901   ,280.9,280.2,276.9
XS GIS Cut Line= 4
2266954.84285451533636.8067501522267090.24672867533440.923317401
 2267139.7037514533399.5192831852267411.28556419533064.494487383
#Sta/Elev= 30
       0 3932.52    38.1 3919.28      53 3910.14    66.8 3908.76    72.5    3907
    84.1 3899.16    93.8 3894.92   104.2 3889.21   116.3 3885.61     136 3876.28
   145.4 3870.25   170.3 3856.23     179 3848.84   185.2 3842.29   199.1  3837.1
204.87923834.116   208.6  3833.2   220.4 3833.03 236.0763833.997   256.4 3836.38
   268.9 3836.65   292.8 3835.42   309.7  3837.6   322.4 3836.23   377.7 3837.81
   424.1 3837.84   600.4 3842.42   671.8 3842.34   702.1 3848.35   733.9  3849.3
#Mann= 5 ,-1,0
       0      .1       0204.8792    .045       0 236.076      .1       0
  522.63     .08       0  582.63      .1       0
#XS Ineff= 1 ,-1
  403.06   702.6 3842.84
Permanent Ineff=
       F
Bank Sta=204.8792,236.076
XS Rating Curve= 0 ,0
Exp/Cntr(USF)=0,0
Exp/Cntr=0.3,0.1

Type RM Length L Ch R = 1 ,33621   ,295.4,310.8,317.9
XS GIS Cut Line= 4
2267176.32314171533746.5492348032267296.04221587533634.811432249
2267443.69574068533393.3779660192267525.50377469533335.513746839
#Sta/Elev= 30
       0 3895.65    10.7 3889.62    21.7 3885.18    37.2 3874.64      43 3871.96
    60.6 3867.13    85.8 3861.54   103.8 3855.48   142.4 3847.11   163.8  3839.9
   170.9 3836.36   176.7 3835.27   188.3 3835.04   194.1 3832.69   216.6 3832.03
   241.33832.588   248.4  3834.7     264 3834.03   282.9 3834.92   307.6 3834.47
   334.5 3836.33   353.2 3835.84   414.2 3837.51   447.1 3840.84   470.2 3841.23
   486.5 3846.25   491.4 3846.75   506.1 3846.85   516.4 3844.23     547 3845.25
#Mann= 5 ,-1,0
       0      .1       0   194.1    .045       0   241.3      .1       0
  476.77     .08       0  486.77      .1       0
Bank Sta=194.1,241.3
XS Rating Curve= 0 ,0
Exp/Cntr(USF)=0,0
Exp/Cntr=0.3,0.1

Type RM Length L Ch R = 1 ,33310   ,248.5,269.7,282.7
XS GIS Cut Line= 2
2267323.97666651533884.2261700912267697.10111432533654.764611277
#Sta/Elev= 30
       0 3876.96    13.5 3870.99    16.9 3870.04    28.4 3868.42    37.8 3865.54
    47.2 3863.59      78 3858.56    92.5 3854.98   118.7 3850.55   131.7 3846.93
   136.4 3844.85   165.2 3838.73   204.3 3833.07     235 3832.57   261.1  3834.1
   272.6  3832.9   287.3 3833.81   300.8 3830.81   310.2    3830   328.9 3830.12
   332.8 3830.79   341.8 3833.88   348.4 3838.06   366.5 3840.67     392  3840.4
   394.9 3840.98   406.5 3846.65   415.3 3849.38   418.2 3850.06     438 3851.44
#Mann= 3 ,-1,0
       0      .1       0   300.8    .045       0   332.8      .1       0
Bank Sta=300.8,332.8
XS Rating Curve= 0 ,0
Exp/Cntr(USF)=0,0
Exp/Cntr=0.3,0.1

Type RM Length L Ch R = 1 ,33040   ,332.6,317.4,300.6
XS GIS Cut Line= 2
2267359.89238876533952.066978784 2267748.9793798533995.963972644
#Sta/Elev= 30
       0  3877.8    12.4 3872.63    24.4 3869.36    44.6 3865.38    72.7 3857.69
    96.9 3851.75     113 3844.94     117 3842.72   129.1 3839.07   137.1 3835.75
   141.2  3834.6   149.6 3833.76   173.4 3833.07   181.4 3831.62   187.93829.427
     193 3828.31   197.5 3828.23   225.5 3828.52   233.8 3829.56     240 3831.43
   245.8 3834.48   249.9 3835.86   261.9 3837.18   282.1 3838.18   308.7 3838.26
   326.3 3837.25   334.4  3838.8   346.5 3845.24   350.5 3846.31   391.6 3848.09
#Mann= 3 ,-1,0
       0      .1       0   187.9    .045       0   233.8      .1       0
Bank Sta=187.9,233.8
XS Rating Curve= 0 ,0
Exp/Cntr(USF)=0,0
Exp/Cntr=0.3,0.1