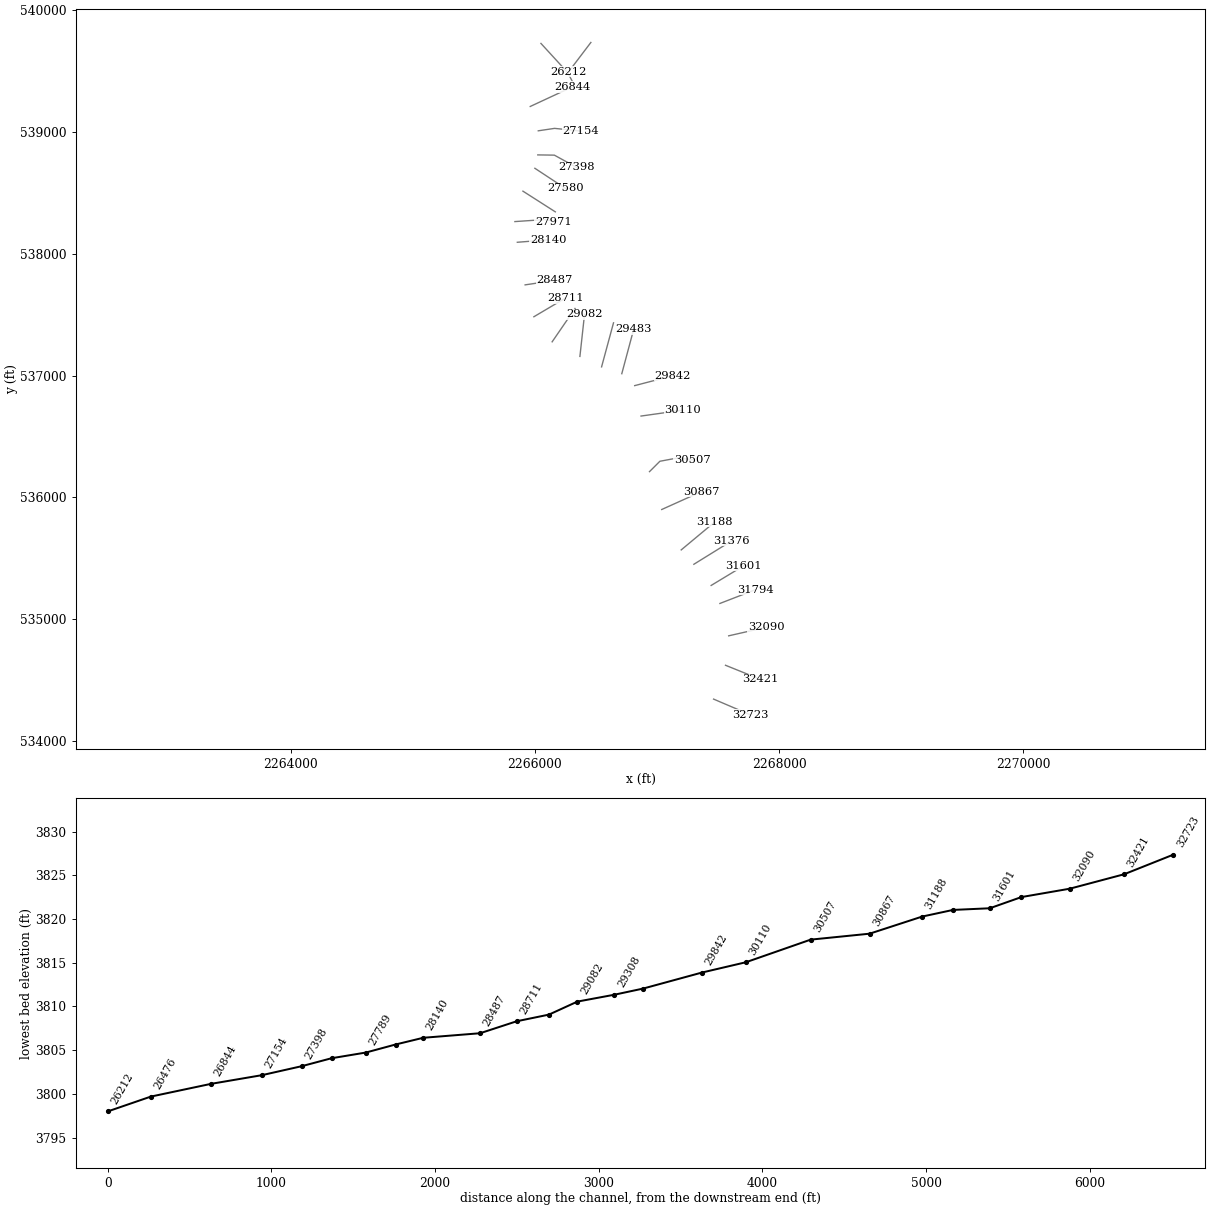
HEC-RAS study SHVRSFK.prj: SHVRSFK

--- SHVRSFK.g01 (geometry) --- (continued)

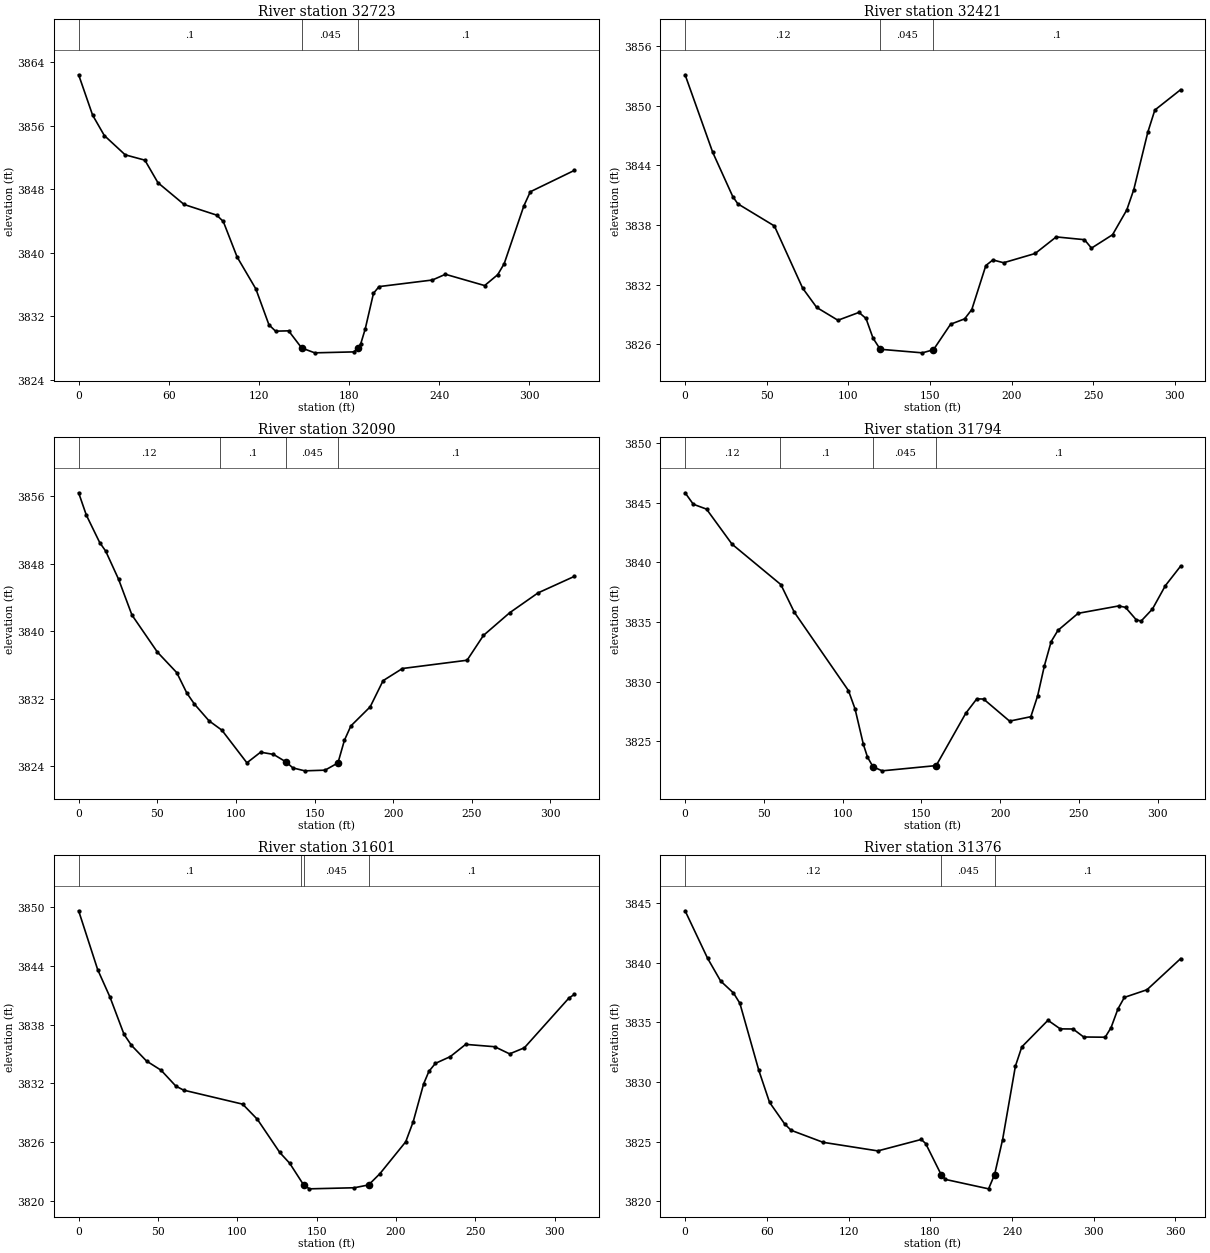
Type RM Length L Ch R = 1 ,32723   ,301.2,301.5,303
XS GIS Cut Line= 2
 2267463.6489197534347.1399235262267766.93724092534217.444259848
#Sta/Elev= 30
       0 3862.39     9.3 3857.31    17.1 3854.74      31 3852.31    44.1 3851.64
    52.8  3848.8    70.2 3846.06    91.9 3844.72    96.3 3843.92   105.5 3839.45
     118 3835.42   126.7 3830.91   131.1 3830.11   139.8 3830.15   148.5 3827.99
   157.2 3827.38   183.3  3827.5   185.7 3827.96   187.8 3828.51   190.8 3830.39
   196.3 3834.88     200 3835.72   235.5 3836.55   244.2 3837.27   270.3 3835.85
     279 3837.22   283.3  3838.6   296.4 3845.88   300.7 3847.66   329.9 3850.34
#Mann= 3 ,-1,0
       0      .1       0   148.5    .045       0   185.7      .1       0
Bank Sta=148.5,185.7
XS Rating Curve= 0 ,0
Exp/Cntr(USF)=0,0
Exp/Cntr=0.3,0.1

Type RM Length L Ch R = 1 ,32421   ,319,331.4,350.8
XS GIS Cut Line= 2
2267561.41949694534624.4891120062267842.75932122 534510.75599155
#Sta/Elev= 30
       0 3853.12    16.9 3845.32    29.2 3840.86    32.3 3840.13    54.7  3837.9
      72 3831.64    80.6  3829.7    93.6 3828.41   106.5  3829.2   110.8 3828.59
   115.1 3826.61   119.5 3825.49   145.3 3825.13   152.1 3825.44   162.6 3828.01
   171.2 3828.55   175.6 3829.49   184.2 3833.92   188.5 3834.48   195.1  3834.2
   214.4 3835.13   227.3  3836.8   244.6 3836.52   248.9 3835.67   261.8 3837.02
   270.5 3839.51   274.8 3841.56   283.4 3847.34   287.7 3849.57   303.5 3851.62
#Mann= 3 ,-1,0
       0     .12       0   119.5    .045       0   152.1      .1       0
Bank Sta=119.5,152.1
XS Rating Curve= 0 ,0
Exp/Cntr(USF)=0,0
Exp/Cntr=0.3,0.1

Type RM Length L Ch R = 1 ,32090   ,291.9,295.9,300.2
XS GIS Cut Line= 2
2267587.35862967534865.9225782372267894.63758669534935.758704832
#Sta/Elev= 30
       0 3856.44     4.9 3853.79    13.4 3850.54    17.2 3849.53    25.4 3846.19
    33.9 3841.95    50.1 3837.55    62.4 3835.12    68.8  3832.7    73.6  3831.4
    82.9 3829.41    91.1  3828.3     107 3824.43   115.7 3825.69   123.9 3825.43
   132.1 3824.51   136.2 3823.83   143.8 3823.48   156.7 3823.56   164.9 3824.42
     169  3827.1   173.1  3828.8   185.4 3831.07   193.6 3834.17   205.9 3835.61
     247 3836.59   257.4 3839.53   274.1 3842.22   292.1 3844.57   315.1 3846.52
#Mann= 4 ,-1,0
       0     .12       0      90      .1       0   132.1    .045       0
   164.9      .1       0
Bank Sta=132.1,164.9
XS Rating Curve= 0 ,0
Exp/Cntr(USF)=0,0
Exp/Cntr=0.3,0.1

Type RM Length L Ch R = 1 ,31794   ,186.8,193.3,197.4
XS GIS Cut Line= 2
2267515.52718517  535131.29985932267808.83891688535245.032979756
#Sta/Elev= 30
       0 3845.84     5.2 3844.88    13.6 3844.47    29.8 3841.53    60.8 3838.14
    69.3 3835.83   103.7 3829.25   107.9 3827.71   113.2 3824.73   115.8 3823.67
   119.33822.861   125.1 3822.52   159.4 3822.96   178.2 3827.35   185.2 3828.56
   189.5 3828.54     206 3826.69   219.5 3827.06   223.8  3828.8   228.1 3831.33
   232.4 3833.36   236.7  3834.3   249.5 3835.73   275.3 3836.35   279.6 3836.23
   286.4 3835.19   289.5 3835.08   296.7 3836.09   304.9 3838.05   314.6 3839.69
#Mann= 4 ,-1,0
       0     .12       0      60      .1       0   119.3    .045       0
   159.4      .1       0
Bank Sta=119.3,159.4
XS Rating Curve= 0 ,0
Exp/Cntr(USF)=0,0
Exp/Cntr=0.3,0.1

Type RM Length L Ch R = 1 ,31601   ,224.3,224.4,224.9
XS GIS Cut Line= 2
2267443.69574068535278.9533841032267711.06833964535440.574134224
#Sta/Elev= 30
       0 3849.61      12 3843.61    19.8 3840.79    28.6 3837.01    33.3 3835.88
    42.8 3834.28      52 3833.34    61.3 3831.72    66.2 3831.31   103.4 3829.88
   112.7 3828.33   126.8 3824.95   133.1 3823.84   141.8 3821.65   145.5 3821.24
   173.8 3821.35   182.8 3821.64   189.9 3822.78   206.2 3826.04   210.9 3828.08
   217.5 3831.95   220.8 3833.22   224.9 3834.04   234.3 3834.73     244 3835.98
   262.3 3835.74   271.7 3835.01     281 3835.63     309 3840.69   312.4 3841.07
#Mann= 4 ,-1,0
       0      .1       0     140     .12       0   141.8    .045       0
   182.8      .1       0
Bank Sta=141.8,182.8
XS Rating Curve= 0 ,0
Exp/Cntr(USF)=0,0
Exp/Cntr=0.3,0.1

Type RM Length L Ch R = 1 ,31376   ,184,188.4,192.8
XS GIS Cut Line= 2
2267302.02816958535452.5460416412267611.30244451535644.096560303
#Sta/Elev= 30
       0 3844.36    16.5 3840.38    26.1 3838.47    35.5 3837.47    40.2 3836.61
    54.1 3830.99      62  3828.3    73.1 3826.49    77.8 3825.96   101.3 3824.95
   141.5 3824.23   173.4 3825.19   176.6 3824.85     188 3822.24   191.1 3821.84
   222.8 3821.05   227.2 3822.24   233.1 3825.18   242.5 3831.34   247.2 3832.95
   266.4 3835.18   275.4 3834.46   284.8 3834.45   292.6 3833.78   308.4 3833.76
   312.7 3834.56   317.8 3836.14   322.5  3837.1   339.1 3837.74   363.8 3840.35
#Mann= 3 ,-1,0
       0     .12       0     188    .045       0   227.2      .1       0
Bank Sta=188,227.2
XS Rating Curve= 0 ,0
Exp/Cntr(USF)=0,0
Exp/Cntr=0.3,0.1

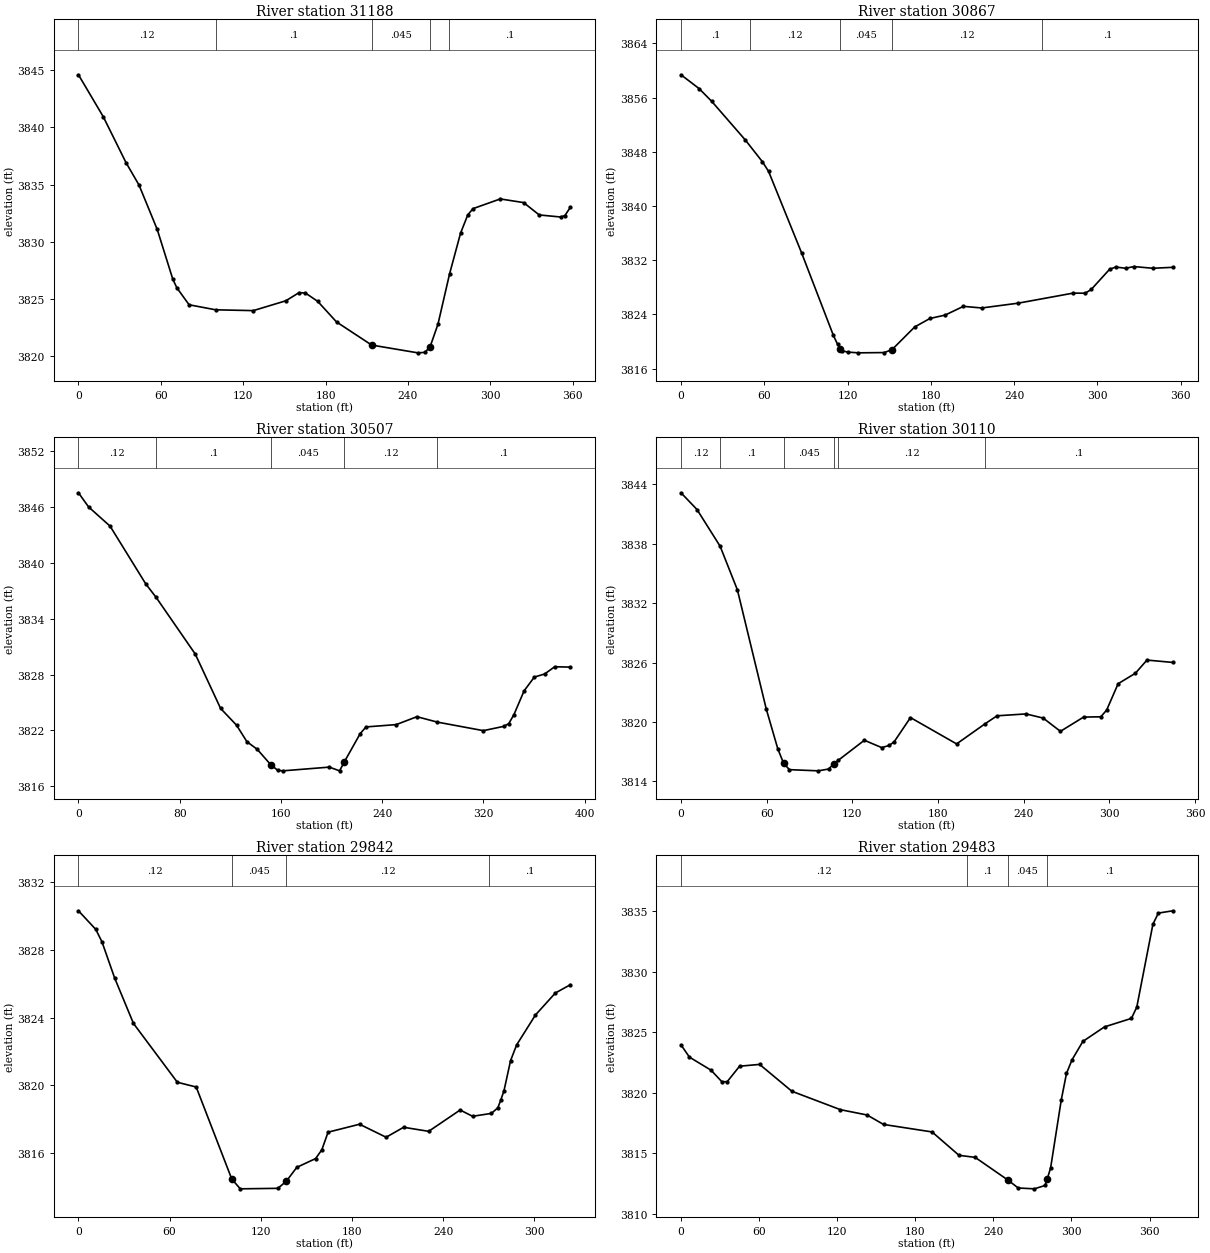
Type RM Length L Ch R = 1 ,31188   ,330.3,321.3,315.3
XS GIS Cut Line= 2
2267198.27163864535570.2697979022267473.62550922535799.731356716
#Sta/Elev= 30
       0 3844.59    18.1 3840.92    34.7  3836.9    44.1 3834.96    57.4 3831.07
    68.7 3826.74    71.6 3825.99    80.6 3824.49     100 3824.05   127.4 3823.98
   151.1 3824.84   160.7 3825.55   165.3 3825.52   174.3 3824.79     188 3822.99
   213.6 3820.97   247.2 3820.29   252.4 3820.33   256.2 3820.83   261.9 3822.79
   270.4 3827.21   278.4 3830.76   283.6 3832.34   287.4 3832.89   307.3 3833.74
   324.3 3833.42   335.7 3832.34   351.3 3832.16   354.4 3832.29   358.4 3833.02
#Mann= 5 ,-1,0
       0     .12       0     100      .1       0   213.6    .045       0
   256.2     .12       0     270      .1       0
Bank Sta=213.6,256.2
XS Rating Curve= 0 ,0
Exp/Cntr(USF)=0,0
Exp/Cntr=0.3,0.1

Type RM Length L Ch R = 1 ,30867   ,368,360,353.8
XS GIS Cut Line= 2
2267038.64620642535901.4925697562267361.88770666536047.150776655
#Sta/Elev= 30
       0 3859.36      13 3857.33    22.1 3855.45    46.3 3849.75    58.7 3846.52
    63.1 3845.11    86.9 3833.08   109.8 3820.91   112.8  3819.6   114.93818.955
   115.8 3818.66   120.1 3818.44   127.9 3818.33   146.5 3818.37   152.1 3818.81
   168.4 3822.15   179.4  3823.4   190.3  3823.9   203.5 3825.19   216.7 3824.95
     243 3825.66   282.5 3827.14   291.3 3827.13   295.6 3827.68   308.8 3830.65
   313.2 3830.99   320.5 3830.81   326.3 3831.06     340 3830.81   354.5 3830.95
#Mann= 5 ,-1,0
       0      .1       0      50     .12       0   114.9    .045       0
   152.1     .12       0     260      .1       0
Bank Sta=114.9,152.1
XS Rating Curve= 0 ,0
Exp/Cntr(USF)=0,0
Exp/Cntr=0.3,0.1

Type RM Length L Ch R = 1 ,30507   ,395.9,396.1,397.5
XS GIS Cut Line= 4
2266938.49156044 536211.986357922267023.59959204 536296.94914574
2267173.09713782536324.9799355742267288.44969511536309.658898925
#Sta/Elev= 30
       0 3847.54       8 3846.02      25 3843.95    53.2 3837.74    61.4 3836.29
    92.3  3830.2   112.3 3824.36   124.9 3822.56   133.1 3820.78   141.2 3819.97
151.92053818.311   157.5  3817.7   161.5 3817.65   198.2 3818.05   206.3 3817.65
   210.1 3818.62   222.6 3821.65   227.2 3822.37   251.1 3822.62   267.4 3823.47
   283.5 3822.89   319.9 3821.97     336 3822.43     340 3822.73   344.1  3823.7
   352.1 3826.25   360.2 3827.73   368.3 3828.06   376.3 3828.84   388.7  3828.8
#Mann= 5 ,-1,0
       0     .12       0    61.4      .1       0151.9205    .045       0
   210.1     .12       0   283.5      .1       0
Bank Sta=151.9205,210.1
XS Rating Curve= 0 ,0
Exp/Cntr(USF)=0,0
Exp/Cntr=0.3,0.1

Type RM Length L Ch R = 1 ,30110   ,266.4,268.8,272.9
XS GIS Cut Line= 2
2266869.04418469536667.6946444062267210.24354606536715.582274071
#Sta/Elev= 30
       0 3843.15    11.2 3841.46    27.4 3837.75    39.5 3833.34    59.7 3821.31
    67.8 3817.28    71.8 3815.84    75.9 3815.18    96.1 3815.06   103.3 3815.24
   106.8 3815.74     110 3816.11   128.4 3818.15   140.5 3817.41   145.8 3817.62
   149.3    3818   160.7 3820.44     193 3817.78   213.1 3819.83   221.3 3820.62
   241.6 3820.81   253.6 3820.39   265.7 3819.05   281.9 3820.49     294 3820.52
   298.1 3821.21   306.1 3823.86   318.2 3824.92   326.3 3826.25   344.5 3826.01
#Mann= 6 ,-1,0
       0     .12       0    27.4      .1       0    71.8    .045       0
   106.8      .1       0     110     .12       0   213.1      .1       0
Bank Sta=71.8,106.8
XS Rating Curve= 0 ,0
Exp/Cntr(USF)=0,0
Exp/Cntr=0.3,0.1

Type RM Length L Ch R = 1 ,29842   ,340.2,358.5,392.9
XS GIS Cut Line= 2
2266817.16591922536917.1093822472267130.43082995 536998.91741626
#Sta/Elev= 30
       0 3830.32    11.4 3829.22    15.5 3828.48    23.8 3826.35    36.2 3823.66
    65.1 3820.18    77.5  3819.9   100.9 3814.46   106.5 3813.88   131.3 3813.91
   136.9 3814.34   143.7 3815.15   156.1 3815.67   160.2 3816.19   164.3 3817.23
     185  3817.7   202.5 3816.93     214 3817.52   230.5 3817.28   251.2 3818.54
   259.4 3818.17   271.8 3818.34     276 3818.67   277.9 3819.11   280.1 3819.69
   284.4 3821.46   288.4 3822.39   300.8 3824.16   313.9 3825.46   323.8 3825.95
#Mann= 4 ,-1,0
       0     .12       0   100.9    .045       0   136.9     .12       0
     270      .1       0
Bank Sta=100.9,136.9
XS Rating Curve= 0 ,0
Exp/Cntr(USF)=0,0
Exp/Cntr=0.3,0.1

Type RM Length L Ch R = 1 ,29483   ,174.5,174.8,174.5
XS GIS Cut Line= 2
2266711.41407037537014.8799594812266809.18464761537380.023135682
#Sta/Elev= 30
       0 3823.94     6.5 3822.93    23.1 3821.85    31.4  3820.9    35.5  3820.9
      45 3822.18    60.4 3822.33    85.2 3820.11   122.5 3818.59     143 3818.15
   155.6 3817.37   192.9 3816.75   213.6 3814.82     226 3814.65     251 3812.79
   259.1 3812.12   271.5 3812.05   279.8 3812.33   281.3 3812.83     284 3813.78
   292.2 3819.41   296.2 3821.59   300.5 3822.72   308.8 3824.23   325.4 3825.43
   346.1 3826.13   350.2 3827.06   362.6 3833.91   366.8 3834.83     378 3835.02
#Mann= 4 ,-1,0
       0     .12       0     220      .1       0     251    .045       0
   281.3      .1       0
Bank Sta=251,281.3
XS Rating Curve= 0 ,0
Exp/Cntr(USF)=0,0
Exp/Cntr=0.3,0.1

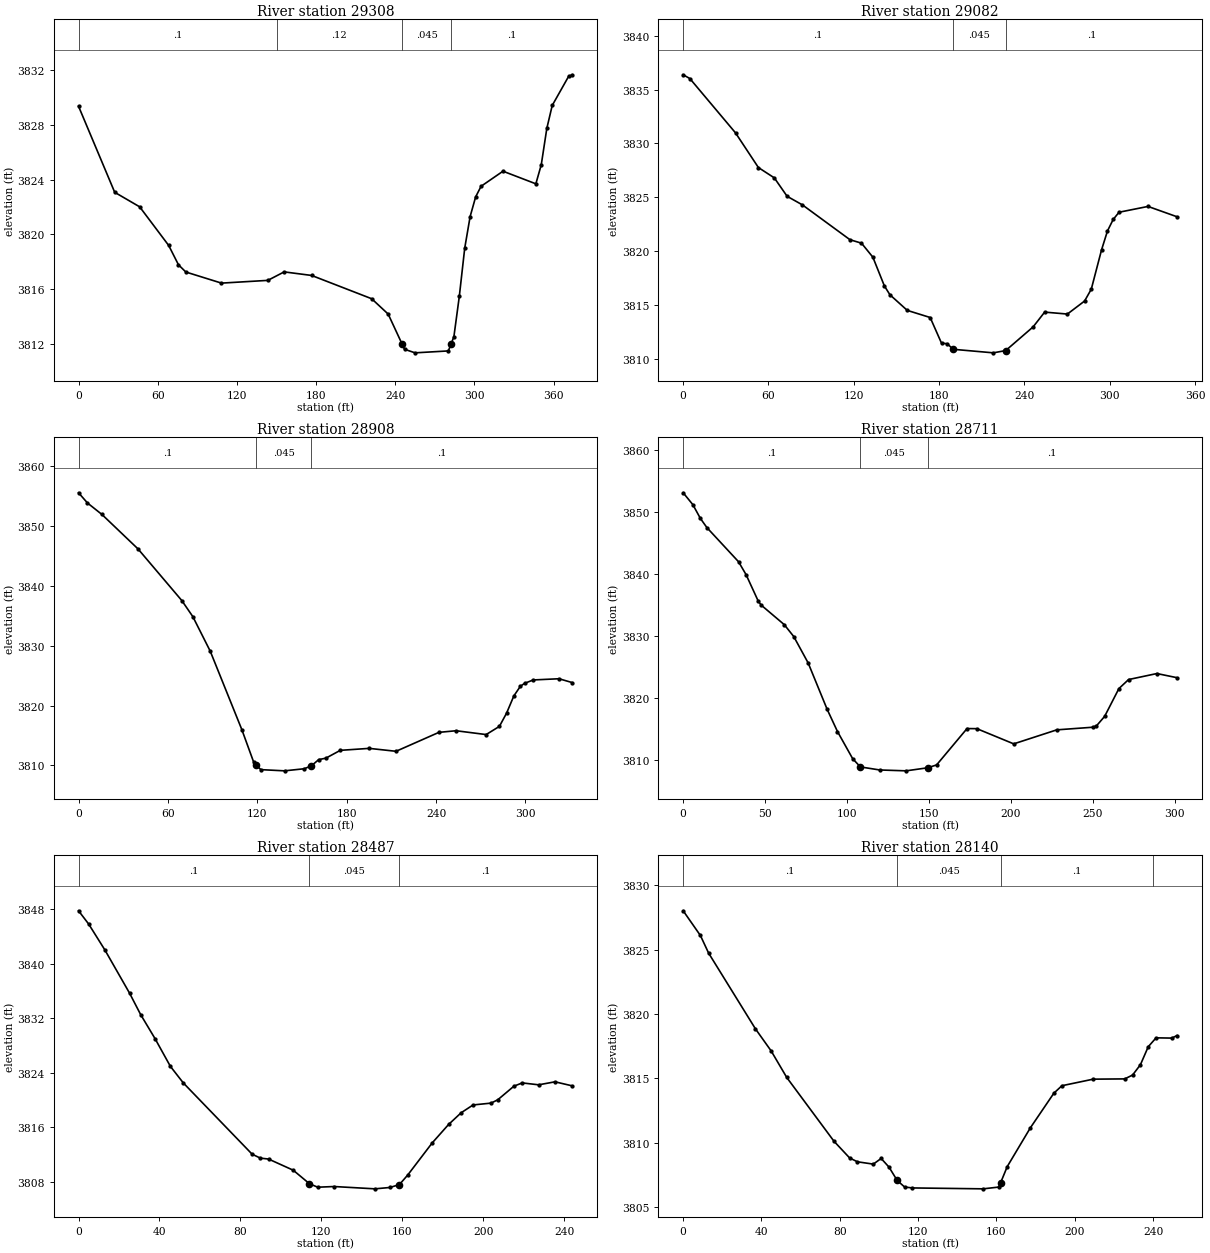
Type RM Length L Ch R = 1 ,29308   ,222.8,226.7,231.6
XS GIS Cut Line= 2
2266545.80268445537070.7488607582266643.57326168537431.901401153
#Sta/Elev= 30
       0 3829.35    27.4 3823.07    46.3 3822.01    68.3 3819.19    75.7 3817.78
    81.3 3817.25   108.3 3816.44   143.4 3816.64   155.8 3817.26   176.6    3817
   222.1  3815.3   234.6 3814.18   245.2 3811.98     247 3811.61     255 3811.35
   280.2 3811.49   282.33812.004   284.4 3812.53   288.5 3815.47   292.6 3818.99
   296.7  3821.3   300.9 3822.74     305 3823.51   321.6 3824.61   346.5 3823.69
   350.6 3825.08   354.8 3827.73   358.9 3829.41   371.3 3831.53   374.2 3831.65
#Mann= 4 ,-1,0
       0      .1       0     150     .12       0   245.2    .045       0
   282.3      .1       0
Bank Sta=245.2,282.3
XS Rating Curve= 0 ,0
Exp/Cntr(USF)=0,0
Exp/Cntr=0.3,0.1

Type RM Length L Ch R = 1 ,29082   ,189.1,173.8,161.1
XS GIS Cut Line= 2
 2266368.2193911537156.5475305762266406.13043126537501.737527748
#Sta/Elev= 30
       0 3836.37     4.7 3836.02    36.8 3830.98    52.9 3827.76    64.1  3826.8
    73.1 3825.09    83.9 3824.29   117.3 3821.06   125.4 3820.74   133.4 3819.44
   141.5 3816.77   145.4 3815.95   157.6  3814.5   173.7 3813.84   181.7 3811.45
   185.7 3811.41   189.8 3810.89   218.1 3810.56   226.8 3810.77   246.1 3812.97
   254.2 3814.34   270.2 3814.16   282.3 3815.37     287 3816.47   294.2 3820.11
   298.4 3821.88   302.4 3822.94   306.5 3823.61   326.9 3824.15   347.3 3823.19
#Mann= 3 ,-1,0
       0      .1       0   189.8    .045       0   226.8      .1       0
Bank Sta=189.8,226.8
XS Rating Curve= 0 ,0
Exp/Cntr(USF)=0,0
Exp/Cntr=0.3,0.1

Type RM Length L Ch R = 1 ,28908   ,210.6,196.9,185.6
XS GIS Cut Line= 2
2266140.75315019 537276.266604742266328.31303305537549.625157414
#Sta/Elev= 30
       0  3855.6       6 3853.89    15.7 3851.97    39.9 3846.21    69.3 3837.57
    76.7 3834.88    88.4 3829.09   109.6 3815.97   117.5 3810.56   119.2 3810.01
   122.4 3809.27   138.3 3809.07   151.5 3809.42   156.3 3809.91   161.2 3810.95
     166 3811.19   175.7  3812.5   195.1 3812.83   213.1 3812.34   241.9 3815.51
   253.4 3815.78   273.6 3815.14   282.5 3816.51   287.3 3818.72   292.2 3821.61
   296.6 3823.23   299.4 3823.71   305.2 3824.28   322.5 3824.48   331.5 3823.83
#Mann= 3 ,-1,0
       0      .1       0   119.2    .045       0   156.3      .1       0
Bank Sta=119.2,156.3
XS Rating Curve= 0 ,0
Exp/Cntr(USF)=0,0
Exp/Cntr=0.3,0.1

Type RM Length L Ch R = 1 ,28711   ,235.3,223.6,211.5
XS GIS Cut Line= 2
2265991.10430749537481.7843487212266250.49563484537635.423827232
#Sta/Elev= 30
       0 3853.15     5.9 3851.24    10.5 3849.02    14.5 3847.53    33.8 3842.03
    38.4 3839.95    45.9 3835.64    47.7 3835.02    61.7 3831.89    67.5 3829.97
    76.3 3825.71    87.9 3818.23    94.2 3814.65   103.5 3810.26   108.2 3808.94
     120 3808.45   136.1 3808.31   149.2  3808.8   154.7 3809.26   173.3 3815.13
   179.3 3815.11   201.8 3812.66   228.1 3814.92     250 3815.34   252.3 3815.56
   257.3 3817.09     266 3821.57   271.9 3823.03   289.2    3824   301.5 3823.33
#Mann= 3 ,-1,0
       0      .1       0   108.2    .045       0   149.2      .1       0
Bank Sta=108.2,149.2
XS Rating Curve= 0 ,0
Exp/Cntr(USF)=0,0
Exp/Cntr=0.3,0.1

Type RM Length L Ch R = 1 ,28487   ,348.6,347.1,343.2
XS GIS Cut Line= 2
2265919.27286299537743.1709939792266160.70632922537779.086716229
#Sta/Elev= 30
       0 3847.81       5 3845.86      13 3842.06    25.2 3835.71    30.7 3832.55
    37.8 3829.02    45.4 3824.94    51.8  3822.5    85.8 3812.03    89.9 3811.45
    93.9 3811.32   106.1 3809.68   114.1  3807.7   118.2 3807.18   126.3 3807.28
   146.5 3806.94   153.9 3807.14   158.6 3807.57   162.7 3808.97   174.8 3813.69
   182.9  3816.4   189.1 3818.12     195 3819.27   203.9 3819.54   207.2 3820.03
   215.2 3822.03   219.3 3822.51   227.4 3822.23   235.5 3822.67   244.1 3822.07
#Mann= 3 ,-1,0
       0      .1       0   114.1    .045       0   158.6      .1       0
Bank Sta=114.1,158.6
XS Rating Curve= 0 ,0
Exp/Cntr(USF)=0,0
Exp/Cntr=0.3,0.1

Type RM Length L Ch R = 1 ,28140   ,169.7,169.3,169
XS GIS Cut Line= 2
 2265855.4226901538092.3516269582266106.83274584538112.304805985
#Sta/Elev= 30
       0 3828.02     8.8  3826.1      13 3824.73    36.9 3818.85    44.9 3817.14
    52.9 3815.07      77 3810.12      85 3808.82      89 3808.52    97.1 3808.34
   101.1 3808.78   105.1 3808.11   109.3 3807.07   113.1 3806.56   117.1 3806.49
   153.2 3806.42   161.3 3806.56   162.1 3806.89   165.5 3808.15   177.3 3811.16
   189.3 3813.85   193.4 3814.43   209.4 3814.94   225.5 3814.96   229.5 3815.26
   233.5 3816.06   237.5 3817.46   241.5 3818.15   249.5 3818.13   252.2 3818.33
#Mann= 4 ,-1,0
       0      .1       0   109.3    .045       0   162.1      .1       0
     240     .08       0
Bank Sta=109.3,162.1
XS Rating Curve= 0 ,0
Exp/Cntr(USF)=0,0
Exp/Cntr=0.3,0.1

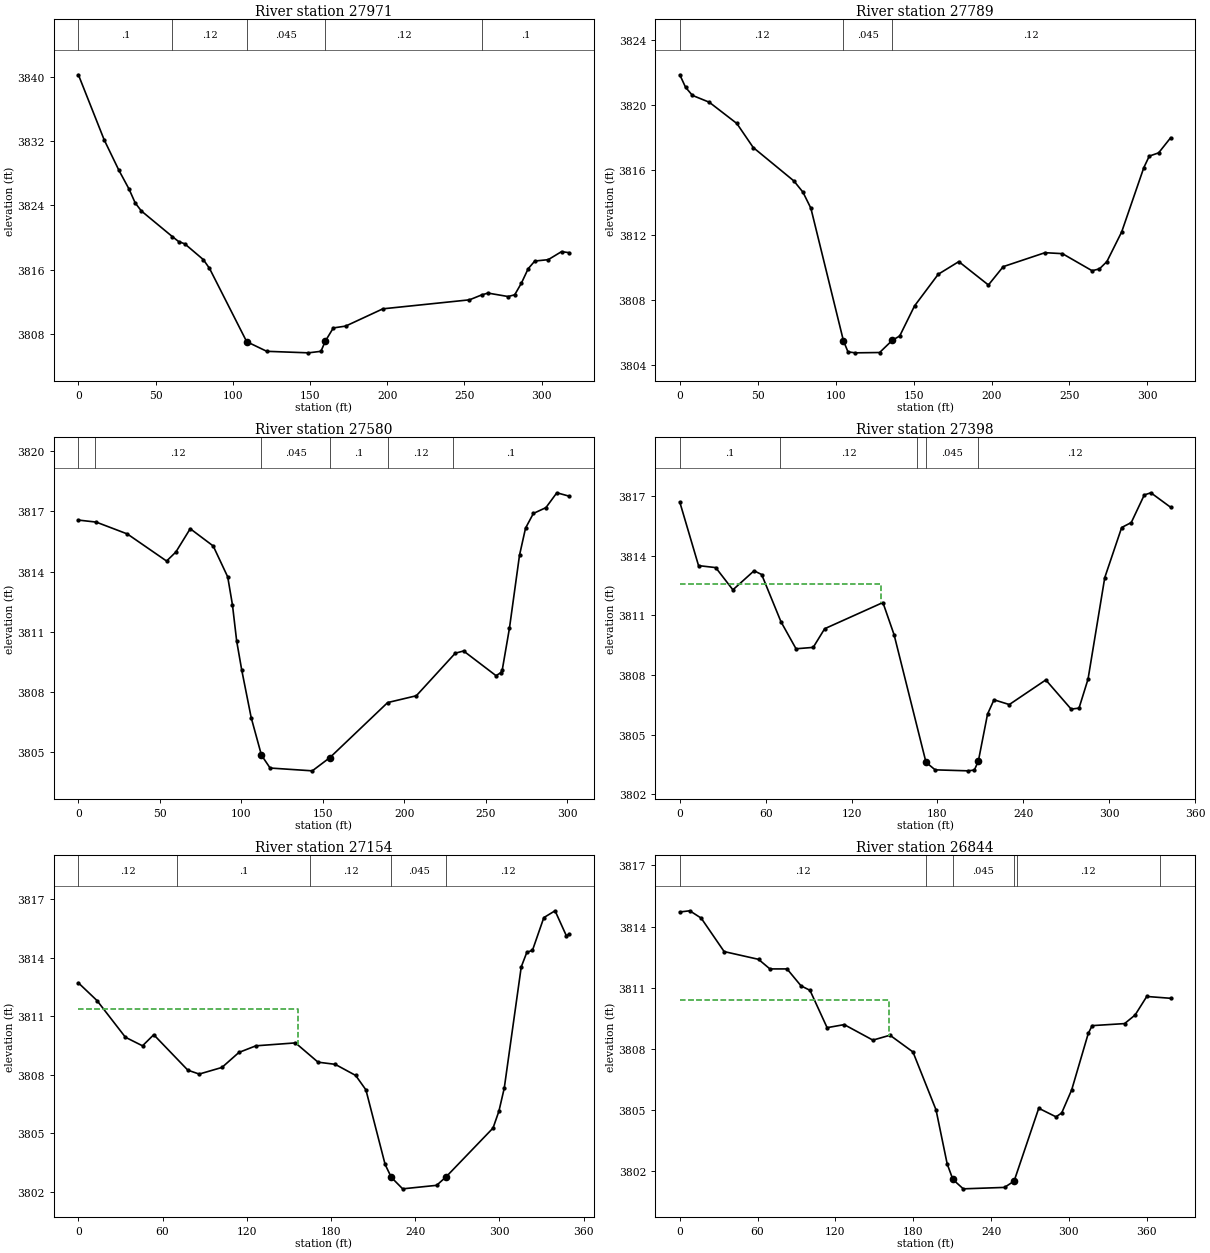
Type RM Length L Ch R = 1 ,27971   ,199.4,181.5,162.1
XS GIS Cut Line= 3
2265835.46951107 538261.953648692266100.84679214538279.911509815
 2266148.7344218538259.958330787
#Sta/Elev= 30
       0 3840.27    16.7 3832.17    26.2 3828.39    32.8 3826.04    36.8 3824.31
    40.8 3823.31    60.8 3820.13    64.9 3819.51    68.9 3819.22    80.9 3817.26
    84.9 3816.17     109 3807.04     122 3805.84     149 3805.65   157.1 3805.84
   159.93807.099   165.1 3808.75   173.1 3808.98   197.2 3811.13   253.3 3812.25
   261.3 3812.87   265.3 3813.09   278.3 3812.66   282.6 3812.88   286.9 3814.32
   291.3 3816.12   295.6 3817.08   304.3 3817.25   312.9 3818.25   317.9 3818.12
#Mann= 5 ,-1,0
       0      .1       0    60.8     .12       0     109    .045       0
   159.9     .12       0   261.3      .1       0
Bank Sta=109,159.9
XS Rating Curve= 0 ,0
Exp/Cntr(USF)=0,0
Exp/Cntr=0.3,0.1

Type RM Length L Ch R = 1 ,27789   ,210.1,209.3,208.8
XS GIS Cut Line= 2
2265901.31500186538511.3683865322266166.69228293  538341.7663648
#Sta/Elev= 30
       0 3821.86     3.7 3821.09     8.1 3820.59    18.9 3820.17    36.6 3818.86
    47.1 3817.38    73.2 3815.32      79 3814.63    84.1 3813.64     105 3805.47
   107.9 3804.79   112.6 3804.73   128.2 3804.75   136.3  3805.5   141.1 3805.77
   150.6 3807.62   165.8 3809.57     179 3810.35     198 3808.91   207.5 3810.04
   234.3  3810.9   245.5 3810.84   264.5 3809.79   269.2  3809.9     274 3810.35
   283.5 3812.18   297.7 3816.14   301.2 3816.85   307.2 3817.05   314.9 3817.98
#Mann= 3 ,-1,0
       0     .12       0     105    .045       0   136.3     .12       0
Bank Sta=105,136.3
XS Rating Curve= 0 ,0
Exp/Cntr(USF)=0,0
Exp/Cntr=0.3,0.1

Type RM Length L Ch R = 1 ,27580   ,180,182.3,184.6
XS GIS Cut Line= 2
 2265999.0855791538698.9282693892266250.49563484538533.316883462
#Sta/Elev= 30
       0 3816.57    10.9 3816.47      30 3815.88    54.1 3814.53    59.8 3814.98
    68.6 3816.14    82.7 3815.28    91.6 3813.74    94.5 3812.35    97.1 3810.54
   100.2  3809.1     106 3806.73   112.3 3804.86   117.6 3804.22   143.5 3804.08
   154.33804.741   189.7 3807.48   207.3 3807.82   231.2 3809.94   236.3 3810.05
   256.2 3808.82   259.1 3808.97     260  3809.1   264.4 3811.17   270.6 3814.82
   274.3 3816.17   279.1  3816.9   286.8 3817.19   293.5 3817.93   301.1 3817.76
#Mann= 6 ,-1,0
       0      .1       0      10     .12       0   112.3    .045       0
   154.3      .1       0     190     .12       0     230      .1       0
Bank Sta=112.3,154.3
XS Rating Curve= 0 ,0
Exp/Cntr(USF)=0,0
Exp/Cntr=0.3,0.1

Type RM Length L Ch R = 1 ,27398   ,232.5,243.6,255.5
XS GIS Cut Line= 3
2266023.02939393538808.6707540392266158.71101132538806.675436137
2266340.28494047   538706.909541
#Sta/Elev= 30
       0 3816.71    13.1 3813.51    25.1 3813.41    37.1 3812.29    51.9 3813.25
    57.2 3813.06    70.7 3810.68    81.2 3809.32    93.2 3809.39   101.2 3810.33
   141.9 3811.65   149.7 3810.03     172  3803.6   178.4 3803.22   201.3 3803.17
   205.8 3803.21   208.6 3803.67     215 3806.03   219.5 3806.75   230.2 3806.51
   255.7 3807.75   273.4 3806.28   278.9 3806.33   285.2 3807.79   296.9 3812.91
   308.7 3815.43   315.4 3815.68   324.5 3817.07   329.1 3817.18   342.9 3816.45
#Mann= 5 ,-1,0
       0      .1       0      70     .12       0   165.7      .1       0
     172    .045       0   208.6     .12       0
#XS Ineff= 2 , 0
          140.54 3812.56
Permanent Ineff=
       F       F
Bank Sta=172,208.6
XS Rating Curve= 0 ,0
Exp/Cntr(USF)=0,0
Exp/Cntr=0.3,0.1

Type RM Length L Ch R = 1 ,27154   ,293,309.8,325.5
XS GIS Cut Line= 3
2266027.02002974 539006.207226412266160.70632922539026.160405437
2266374.20534481539004.211908507
#Sta/Elev= 30
       0 3812.71    13.3  3811.8    33.5 3809.92    45.7 3809.48    53.7 3810.05
      78 3808.23    86.1 3808.03   102.3 3808.37   114.4 3809.14   126.5 3809.48
   154.7 3809.63   170.8 3808.64     183 3808.53   197.6 3807.96   204.9 3807.22
   218.6 3803.39     223 3802.73   231.1 3802.14   255.3 3802.32   262.1 3802.76
   295.5 3805.26   299.7 3806.13   303.5 3807.31   315.6 3813.53   319.6 3814.28
   323.6 3814.38   331.7 3816.06   339.7 3816.41   347.8 3815.12   349.8 3815.22
#Mann= 5 ,-1,0
       0     .12       0      70      .1       0  165.17     .12       0
     223    .045       0   262.1     .12       0
#XS Ineff= 2 , 0
          156.61 3811.38
Permanent Ineff=
       F       F
Bank Sta=223,262.1
XS Rating Curve= 0 ,0
Exp/Cntr(USF)=0,0
Exp/Cntr=0.3,0.1

Type RM Length L Ch R = 1 ,26844   ,394.1,368.3,322.7
XS GIS Cut Line= 2
2265961.17453895539205.7390166832266304.36921822539365.364448902
#Sta/Elev= 30
       0 3814.72     7.7 3814.78    16.5 3814.42    34.2 3812.78    60.7  3812.4
    69.5 3811.93    82.7 3811.93    93.5  3811.1   100.4 3810.88   113.6 3809.05
   126.8  3809.2   148.9 3808.44   162.1 3808.68   179.8 3807.86   197.6 3805.02
   206.2 3802.37   210.6 3801.61   218.6 3801.15   250.4 3801.22   257.8 3801.53
   276.8  3805.1   290.1 3804.68   294.5 3804.87   302.2    3806     315 3808.77
     318 3809.15     343 3809.25   351.1 3809.67   360.1 3810.58   378.5 3810.49
#Mann= 6 ,-1,0
       0     .12       0     190      .1       0   210.6    .045       0
   257.8      .1       0     260     .12       0     370      .1       0
#XS Ineff= 2 , 0
          161.17 3810.42
Permanent Ineff=
       F       F
Bank Sta=210.6,257.8
XS Rating Curve= 0 ,0
Exp/Cntr(USF)=0,0
Exp/Cntr=0.3,0.1

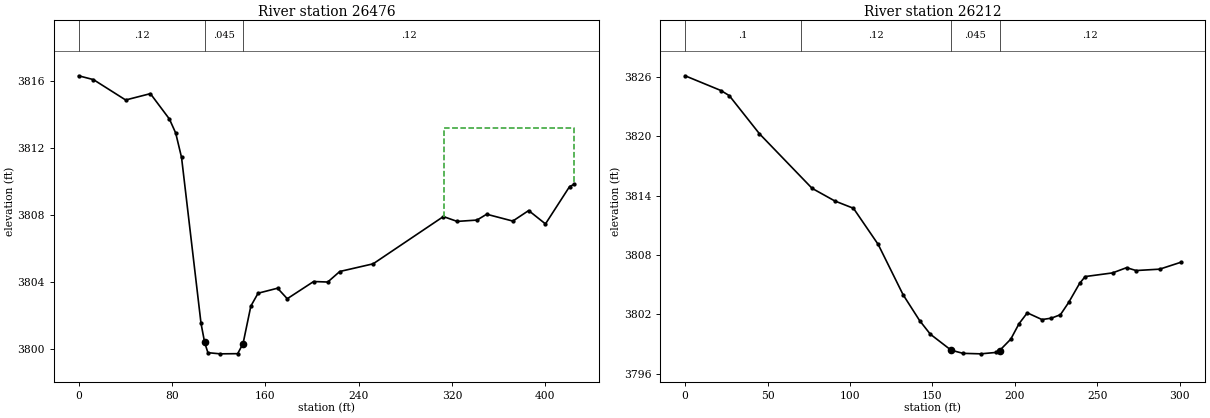
Type RM Length L Ch R = 1 ,26476   ,290.8,263.8,218
XS GIS Cut Line= 3
2266048.96852667539722.5263534912266268.45349597539483.088205163
2266314.86522344539394.672250901
#Sta/Elev= 30
       0 3816.34    12.7 3816.11    40.3 3814.89    61.5 3815.27    77.8 3813.75
    83.2 3812.91    88.2 3811.45   104.9 3801.51     108 3800.37   110.8 3799.76
   121.2 3799.69   136.3  3799.7   140.9  3800.3   147.6 3802.55   153.8 3803.32
   170.5 3803.62   178.8 3802.99   201.4 3804.02   213.5 3803.99   223.8 3804.62
   252.4 3805.08   312.6 3807.91   324.4 3807.62   341.4  3807.7   349.7 3808.05
   372.1 3807.64   385.7 3808.27   400.1 3807.47   420.8 3809.71   424.7 3809.84
#Mann= 3 ,-1,0
       0     .12       0     108    .045       0   140.9     .12       0
#XS Ineff= 2 , 0
                          313.25         3813.23
Permanent Ineff=
       F       F
Bank Sta=108,140.9
XS Rating Curve= 0 ,0
Exp/Cntr(USF)=0,0
Exp/Cntr=0.3,0.1

Type RM Length L Ch R = 1 ,26212   ,109.2,119.1,126.2
BEGIN DESCRIPTION:
Structure XS 4
END DESCRIPTION:
XS GIS Cut Line= 2
2266458.00869673539730.5076251032266276.43476758539491.069476774
#Sta/Elev= 30
       0 3826.13    21.7 3824.64    26.8 3824.12    45.1 3820.26      77 3814.74
    90.8 3813.46   102.1 3812.72   117.1 3809.06   132.2 3803.97   142.2 3801.36
   148.7 3799.98   161.33798.362   168.5 3798.04   179.3 3797.99   188.4 3798.13
   190.7 3798.32   197.5 3799.48   202.5 3801.04   207.5 3802.14   216.4 3801.46
   222.1  3801.6   227.6 3801.95   232.6 3803.19   239.2 3805.11   242.6 3805.81
   259.2 3806.18   267.7 3806.71   273.5 3806.42   287.8 3806.56   300.5 3807.25
#Mann= 4 ,-1,0
       0      .1       0      70     .12       0   161.3    .045       0
   190.7     .12       0
Bank Sta=161.3,190.7
XS Rating Curve= 0 ,0
Exp/Cntr(USF)=0,0
Exp/Cntr=0.5,0.3