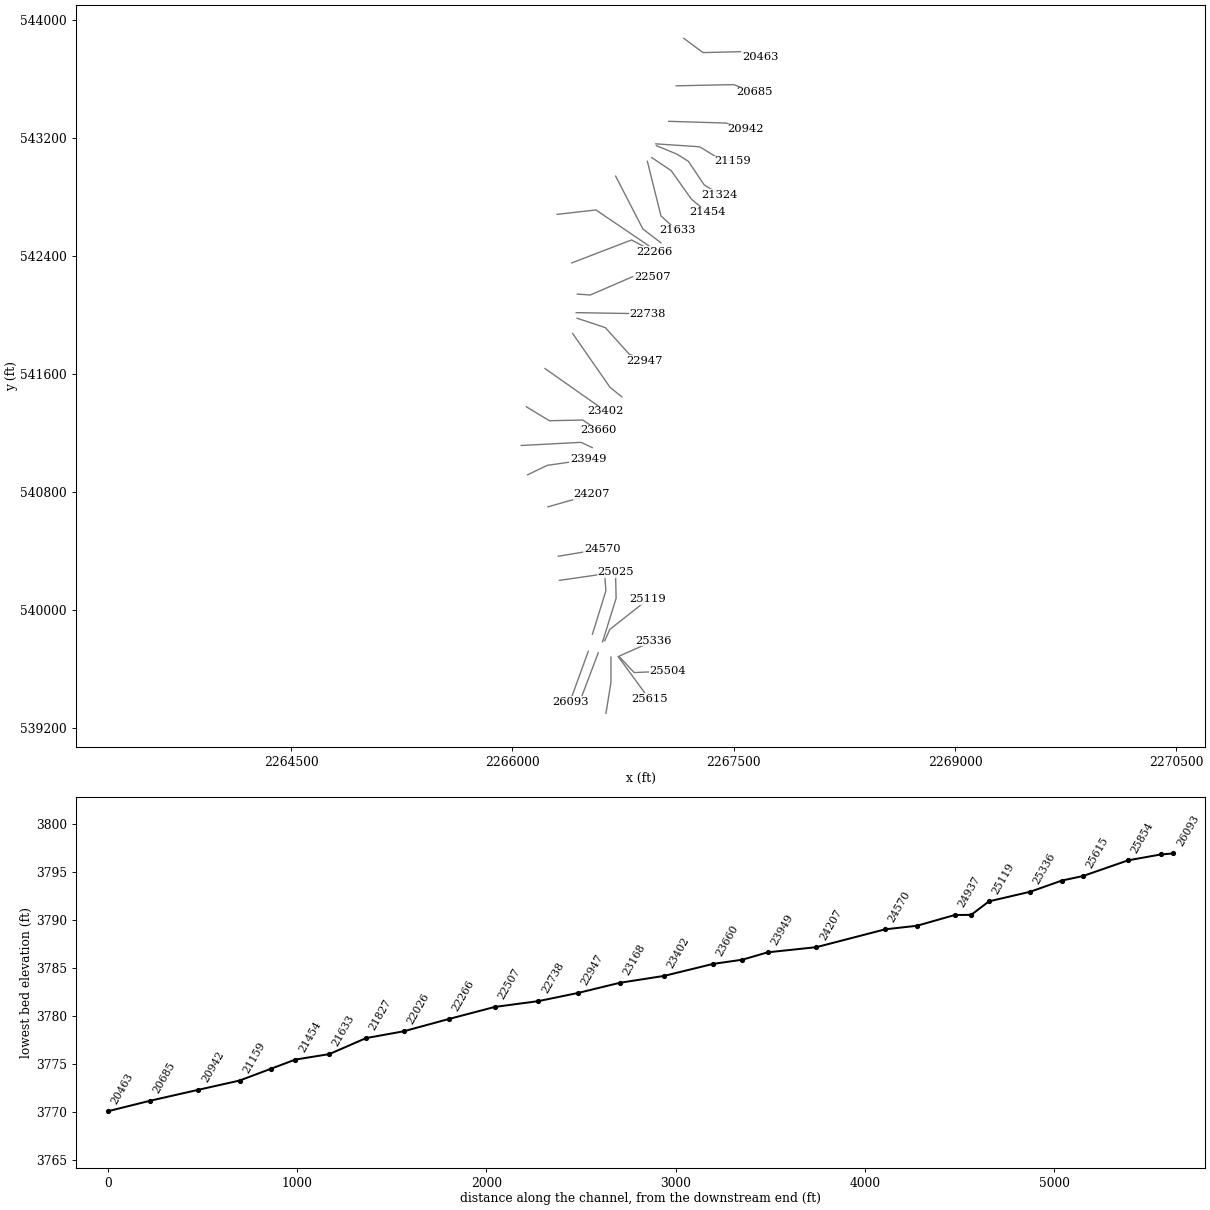
HEC-RAS study SHVRSFK.prj: SHVRSFK

--- SHVRSFK.g01 (geometry) --- (continued)

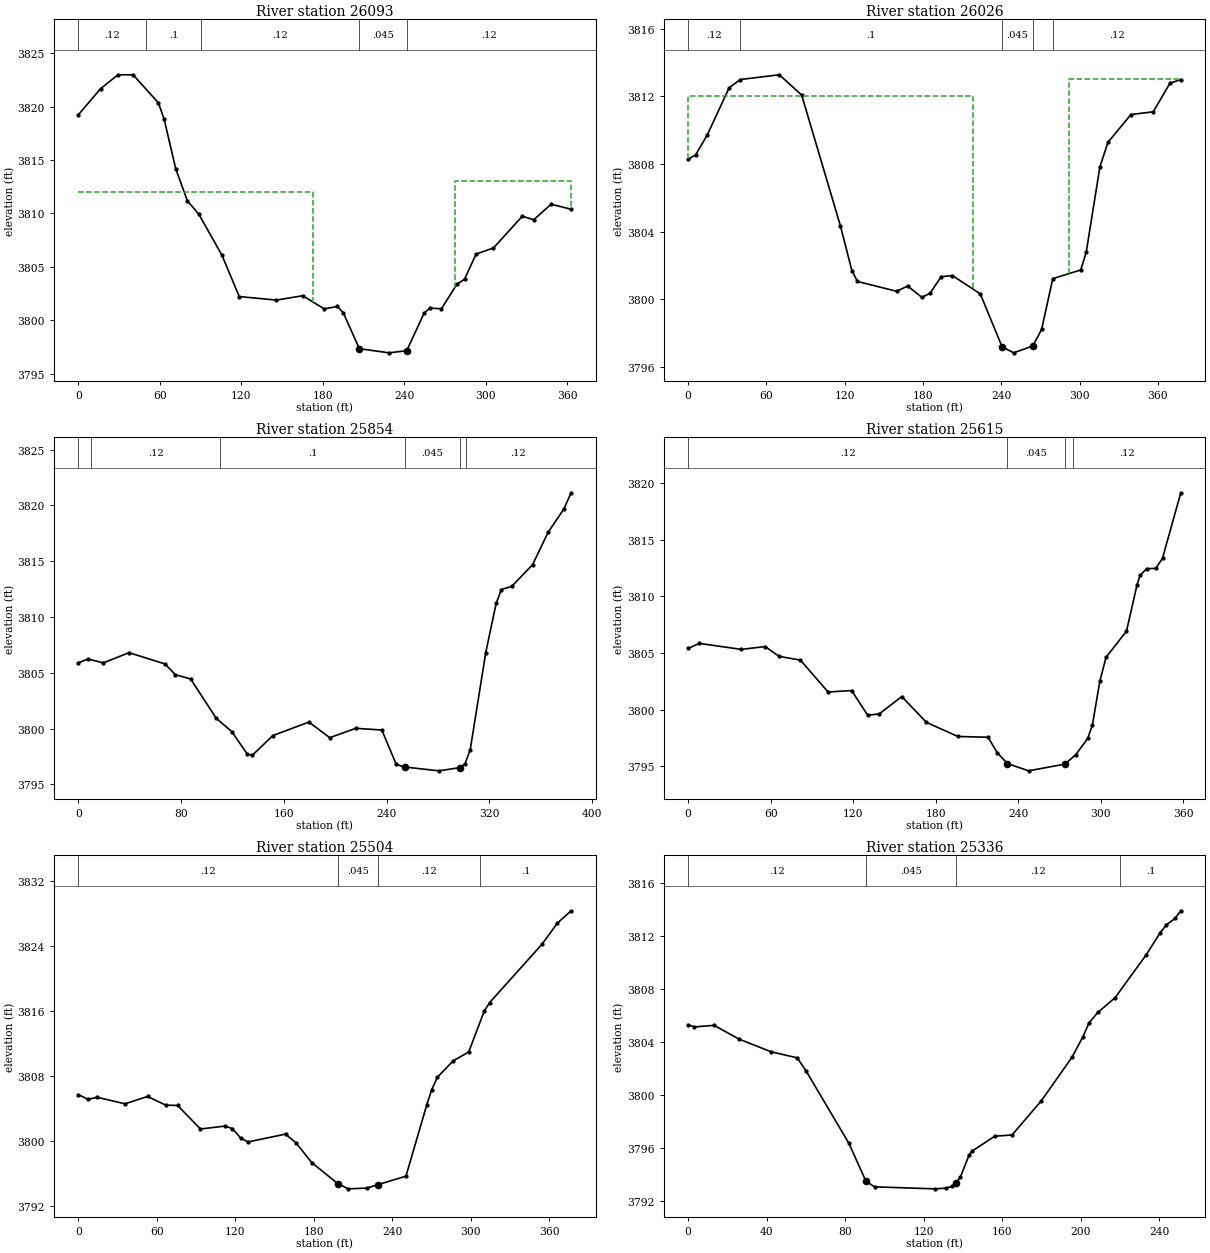
Type RM Length L Ch R = 1 ,26093   ,67.3,66.8,64.1
BEGIN DESCRIPTION:
Structure XS 3
END DESCRIPTION:
XS GIS Cut Line= 2
  2266513.877598539720.5310355892266390.16788803539379.331674221
#Sta/Elev= 30
       0 3819.25    16.3 3821.68    29.1 3822.98    40.2 3822.98    58.9 3820.35
    63.1 3818.82    71.6 3814.19    80.2 3811.18    88.7 3809.91   105.7 3806.08
   118.4 3802.21   145.8 3801.88   165.2 3802.29     181 3801.06   190.8 3801.28
     195 3800.71   206.9 3797.33   228.8 3796.94   241.8 3797.14   254.6 3800.66
   258.9 3801.13   267.4 3801.07   278.7 3803.35   284.4 3803.84   292.9 3806.19
   305.7 3806.76   326.9 3809.73   335.4 3809.41   348.2 3810.86   362.9 3810.39
#Mann= 5 ,-1,0
       0     .12       0      50      .1       0      90     .12       0
   206.9    .045       0   241.8     .12       0
#XS Ineff= 2 , 0
             173    3812     277            3813
Permanent Ineff=
       F       F
Bank Sta=206.9,241.8
XS Rating Curve= 0 ,0
Exp/Cntr(USF)=0,0
Exp/Cntr=0.5,0.3

Type RM Length L Ch R = 1 ,26026   ,166.4,172.5,180
BEGIN DESCRIPTION:
Structure XS 2
END DESCRIPTION:
XS GIS Cut Line= 2
 2266581.7184067539710.5544460752266448.03210721539357.383177291
#Sta/Elev= 30
       0 3808.28     5.7 3808.53    14.7 3809.72    31.4  3812.5      40 3812.99
    69.9 3813.27      87 3812.07   116.7 3804.34   125.5 3801.69   129.8 3801.05
   159.7 3800.47   168.3 3800.78   179.1 3800.11   185.4 3800.35   193.9 3801.33
   202.5  3801.4   223.9 3800.32   240.6 3797.19   249.5 3796.83   264.2 3797.24
   270.9 3798.21   279.5 3801.22   300.9 3801.73   305.1 3802.77   315.6 3807.83
   321.8 3809.28   339.4 3810.92   356.5 3811.08   369.3 3812.77   377.6 3812.99
#Mann= 5 ,-1,0
       0     .12       0      40      .1       0   240.6    .045       0
   264.2      .1       0     280     .12       0
#XS Ineff= 2 , 0
             218    3812     292            3813
Permanent Ineff=
       F       F
Bank Sta=240.6,264.2
XS Rating Curve= 0 ,0
Exp/Cntr(USF)=0,0
Exp/Cntr=0.5,0.3

Type RM Length L Ch R = 1 ,25854   ,211.1,238.7,260.6
BEGIN DESCRIPTION:
Structure XS 1
END DESCRIPTION:
XS GIS Cut Line= 3
2266667.51707651539680.6246775342266667.51707651539509.027337899
2266633.59667217539299.518958112
#Sta/Elev= 30
       0 3805.91     7.4 3806.24    19.4  3805.9    39.4 3806.81    67.4  3805.8
    75.4 3804.84    87.4 3804.45   107.4 3800.92   119.4 3799.74   131.4 3797.74
   135.4 3797.61   151.4 3799.38   179.5 3800.59   195.8 3799.19     216 3800.03
   236.3 3799.88   247.6 3796.79   254.4 3796.56   280.9 3796.22   297.1 3796.51
   301.1 3796.85   305.2 3798.11   317.3 3806.82   325.4 3811.23   329.5 3812.47
   337.6 3812.76   353.8  3814.7   365.9  3817.6   378.1 3819.68   383.8 3821.14
#Mann= 6 ,-1,0
       0      .1       0      10     .12       0     110      .1       0
   254.4    .045       0   297.1      .1       0   301.6     .12       0
Bank Sta=254.4,297.1
XS Rating Curve= 0 ,0
Exp/Cntr(USF)=0,0
Exp/Cntr=0.3,0.1

Type RM Length L Ch R = 1 ,25615   ,73.5,111.2,131.1
XS GIS Cut Line= 2
2266715.40470618539686.6106312422266926.90840387539397.289535346
#Sta/Elev= 30
       0  3805.4     8.1 3805.85    38.8 3805.32      56 3805.57    66.2  3804.7
    81.7 3804.37   101.8 3801.55   118.9 3801.68   130.6  3799.5     139 3799.61
   155.4 3801.15   173.3 3798.87   196.2 3797.62   218.2 3797.55   224.8 3796.19
   232.33795.224   247.7 3794.58   274.13795.177   282.1 3796.02   290.7 3797.45
   294.1 3798.64   299.5  3802.5     304 3804.62   318.9 3806.93   326.6 3811.05
   328.8 3811.87   333.6 3812.46   340.2 3812.48   345.1 3813.38   358.4 3819.17
#Mann= 4 ,-1,0
       0     .12       0   232.3    .045       0   274.1      .1       0
     280     .12       0
Bank Sta=232.3,274.1
XS Rating Curve= 0 ,0
Exp/Cntr(USF)=0,0
Exp/Cntr=0.3,0.1

Type RM Length L Ch R = 1 ,25504   ,156.1,167.5,177.8
XS GIS Cut Line= 3
2266724.27095573539683.6269162472266825.18179913539576.320848144
2267054.33350602539585.869536701
#Sta/Elev= 30
       0 3805.71     7.3 3805.13    14.3 3805.39    35.6 3804.58    52.8 3805.49
    66.7 3804.42    75.8 3804.38    93.3 3801.48     112 3801.84   117.7 3801.53
   124.2 3800.34   129.7 3799.89   158.3 3800.85   166.4 3799.77   178.3 3797.35
   198.3 3794.75   206.3 3794.11   220.5  3794.2   228.9 3794.62   250.4 3795.67
   266.3 3804.44   270.1 3806.32   274.4 3807.85   286.4 3809.86   298.4 3810.97
   310.4 3816.05   314.4 3817.05   354.5 3824.25   366.2 3826.84   376.7 3828.36
#Mann= 4 ,-1,0
       0     .12       0   198.3    .045       0   228.9     .12       0
   307.3      .1       0
Bank Sta=198.3,228.9
XS Rating Curve= 0 ,0
Exp/Cntr(USF)=0,0
Exp/Cntr=0.3,0.1

Type RM Length L Ch R = 1 ,25336   ,209.6,217.6,228.4
XS GIS Cut Line= 2
 2266729.3719315539690.6012670482266958.83349031539792.362480087
#Sta/Elev= 30
       0 3805.31     3.1 3805.15    13.2 3805.27    26.1 3804.22    42.4 3803.27
    55.6 3802.82      60 3801.85    81.8  3796.4    90.6 3793.51      95 3793.09
   125.6 3792.94   131.4 3792.99   134.3 3793.12   136.53793.399   138.7 3793.82
   143.1 3795.48   144.5 3795.77   156.2 3796.91     165    3797   179.9 3799.57
   195.6 3802.87   201.1  3804.4   204.3 3805.47   208.7 3806.24   217.5 3807.35
   233.3 3810.57   240.5 3812.25   243.6 3812.84   248.1 3813.34     251 3813.91
#Mann= 4 ,-1,0
       0     .12       0    90.6    .045       0   136.5     .12       0
     220      .1       0
Bank Sta=90.6,136.5
XS Rating Curve= 0 ,0
Exp/Cntr(USF)=0,0
Exp/Cntr=0.3,0.1

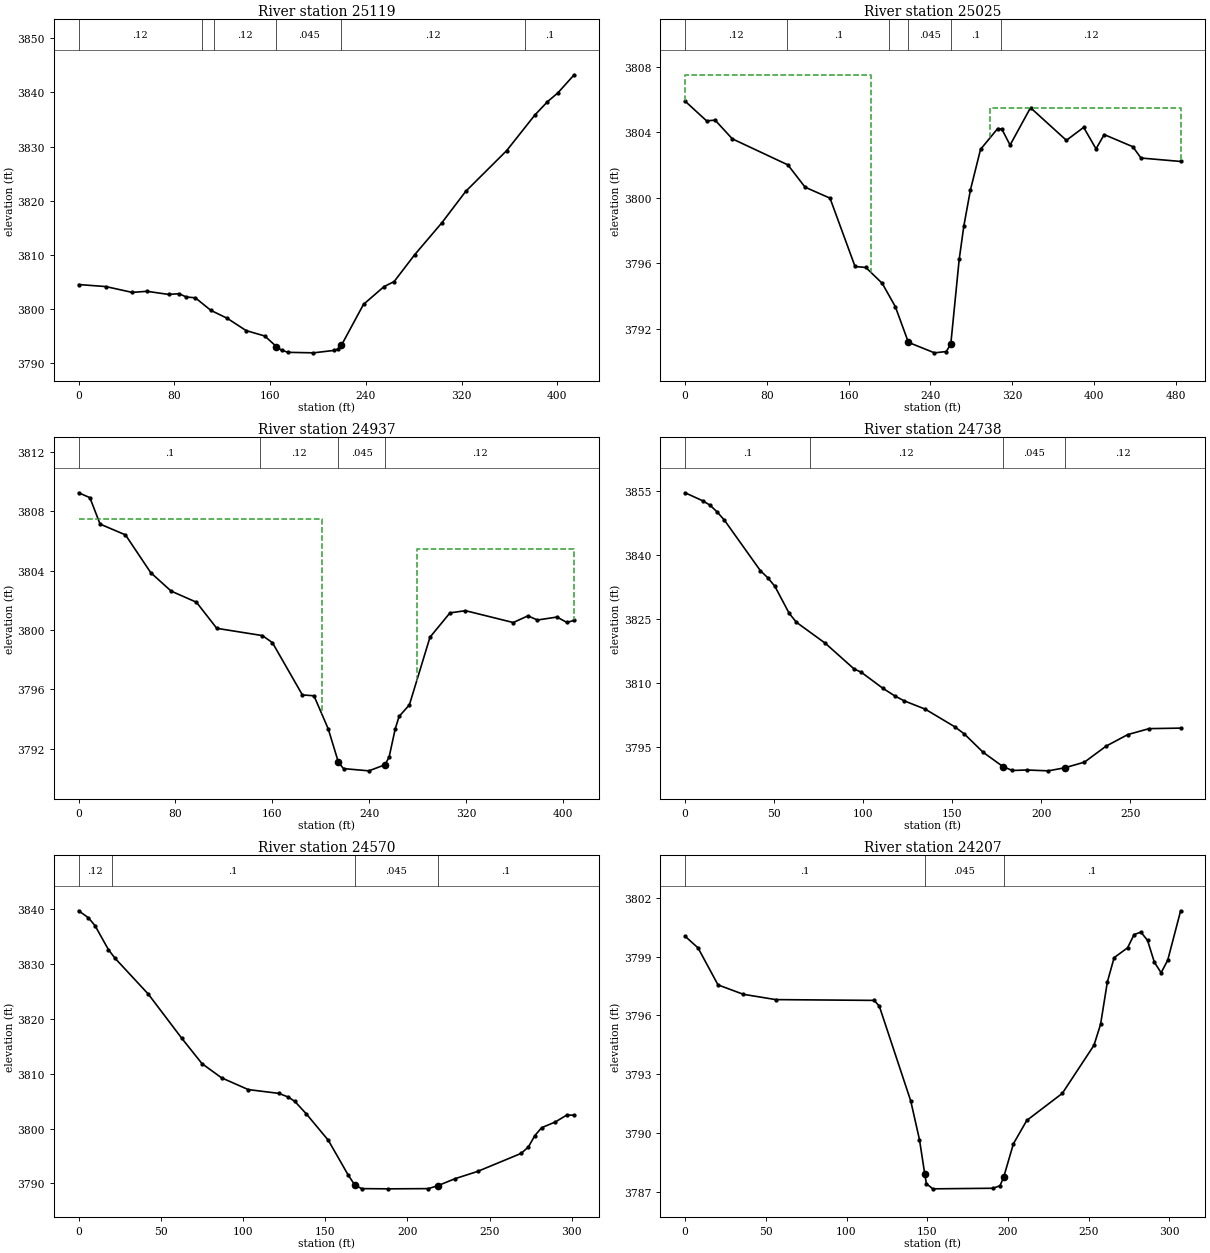
Type RM Length L Ch R = 1 ,25119   ,81.9,94.2,118.6
BEGIN DESCRIPTION:
Structure XS 4
END DESCRIPTION:
XS GIS Cut Line= 3
2266625.61540056539792.362480087 2266659.5358049539868.184560391
2266918.92713226540073.702304373
#Sta/Elev= 30
       0 3804.55    22.8 3804.17    44.7  3803.1    57.1  3803.3    75.2 3802.72
    83.9 3802.86    89.9 3802.25    97.5  3802.1   110.4 3799.79   124.1 3798.32
     140 3796.04   155.5 3795.05   165.33793.081   169.6  3792.4   175.3 3792.03
   196.2 3791.94   213.5 3792.39   216.6 3792.62   219.53793.318     238 3800.89
   255.1 3804.16   263.6  3805.1   280.7 3810.04   303.5 3815.96   323.4 3821.75
   357.6 3829.27     381  3835.8   391.7  3838.3   400.3 3839.91     414 3843.27
#Mann= 6 ,-1,0
       0     .12       0  103.06      .1       0  113.06     .12       0
   165.3    .045       0   219.5     .12       0  373.06      .1       0
Bank Sta=165.3,219.5
XS Rating Curve= 0 ,0
Exp/Cntr(USF)=0,0
Exp/Cntr=0.5,0.3

Type RM Length L Ch R = 1 ,25025   ,85.5,87.6,85
BEGIN DESCRIPTION:
Structure XS 3
END DESCRIPTION:
XS GIS Cut Line= 3
2266610.81871106539785.0874039972266702.60333458540080.394453602
2266698.61269878540255.982429042
#Sta/Elev= 30
       0 3805.89      21 3804.69    29.4 3804.73    46.2 3803.59   100.6    3802
   117.4 3800.64   141.8 3799.97   166.3  3795.8   176.9 3795.74   192.9 3794.77
   205.7 3793.35   218.5 3791.17     244 3790.53   255.6 3790.61     260 3791.07
   268.2 3796.23   272.8 3798.29   279.2 3800.47   289.1 3802.95   305.9 3804.22
     310 3804.18     318 3803.21     338 3805.49   373.1  3803.5     390 3804.29
   402.1 3802.98   410.1 3803.85   438.1 3803.11   446.1 3802.42   484.9 3802.21
#Mann= 6 ,-1,0
       0     .12       0     100      .1       0     200     .12       0
   218.5    .045       0     260      .1       0  309.24     .12       0
#XS Ineff= 2 , 0
             182  3807.5     298          3805.5
Permanent Ineff=
       F       F
Bank Sta=218.5,260
XS Rating Curve= 0 ,0
Exp/Cntr(USF)=0,0
Exp/Cntr=0.5,0.3

Type RM Length L Ch R = 1 ,24937   ,230,199.2,166.7
BEGIN DESCRIPTION:
Structure XS 2
END DESCRIPTION:
XS GIS Cut Line= 3
2266541.81204864539836.2594739472266633.59667217540131.566523552
2266625.61540056540231.332418689
#Sta/Elev= 30
       0 3809.26     9.3 3808.93    17.7 3807.15    38.7 3806.42    59.6 3803.87
    76.4 3802.63    97.3 3801.88   114.1 3800.12   151.8 3799.63   160.1 3799.15
   184.8 3795.63   194.4 3795.57   206.2 3793.33   214.6 3791.08   218.8 3790.66
   239.7 3790.51   253.1 3790.92   256.5 3791.46   261.5 3793.34   264.7 3794.18
   273.2 3794.96   290.2 3799.52   306.7 3801.16   319.5 3801.31     359 3800.51
   371.1 3800.96   378.9 3800.68   395.1 3800.88   403.2 3800.52   409.3 3800.65
#Mann= 4 ,-1,0
       0      .1       0     150     .12       0   214.6    .045       0
   253.1     .12       0
#XS Ineff= 2 , 0
           200.7  3807.5   279.3          3805.5
Permanent Ineff=
       F       F
Bank Sta=214.6,253.1
XS Rating Curve= 0 ,0
Exp/Cntr(USF)=0,0
Exp/Cntr=0.5,0.3

Type RM Length L Ch R = 1 ,24738   ,166.7,167.7,169.5
BEGIN DESCRIPTION:
Structure XS 1
END DESCRIPTION:
XS GIS Cut Line= 2
2266318.33644354540201.4026501482266593.69031411540241.309008202
#Sta/Elev= 30
       0 3854.61     9.9 3852.73      14  3851.7      18 3850.11    22.1 3848.17
    42.3 3836.32    46.3 3834.73    50.4 3832.68    58.4 3826.36    62.5 3824.23
    78.7 3819.32    94.8 3813.31    98.9 3812.52     111 3808.76   117.9 3806.92
   123.1 3805.79   134.8 3803.86   151.4 3799.72   156.8 3798.03   167.3 3793.75
   178.43790.401   183.7 3789.47   191.8 3789.59   203.9 3789.39   213.2 3790.11
   224.2 3791.43   236.3 3795.17   248.5 3797.89   260.5 3799.29   278.2 3799.41
#Mann= 4 ,-1,0
       0      .1       0      70     .12       0   178.4    .045       0
   213.2     .12       0
Bank Sta=178.4,213.2
XS Rating Curve= 0 ,0
Exp/Cntr(USF)=0,0
Exp/Cntr=0.3,0.1

Type RM Length L Ch R = 1 ,24570   ,359.3,363,367.1
XS GIS Cut Line= 2
2266310.35517192540365.0187181722266607.65753943 540414.90166574
#Sta/Elev= 30
       0 3839.73     5.9 3838.47      10 3837.01    18.1 3832.66    22.1 3831.09
    42.4 3824.53    62.7  3816.5    75.1 3811.84      87 3809.26   103.2 3807.12
   121.8 3806.43   127.6 3805.75   131.6 3804.95   138.5  3802.7   151.9 3797.88
   164.1 3791.49   168.1 3789.69   172.2 3789.06   188.4 3789.02   212.8 3789.06
   218.5 3789.59     229 3790.87   242.7 3792.19   269.2 3795.48   273.6 3796.64
   277.6 3798.74   281.7 3800.17     290 3801.21   296.9 3802.46   301.5 3802.47
#Mann= 4 ,-1,0
       0     .12       0      20      .1       0   168.1    .045       0
   218.5      .1       0
Bank Sta=168.1,218.5
XS Rating Curve= 0 ,0
Exp/Cntr(USF)=0,0
Exp/Cntr=0.3,0.1

Type RM Length L Ch R = 1 ,24207   ,261.4,257.8,252.5
XS GIS Cut Line= 2
2266240.51904533540700.2321258312266535.82609493540784.035477746
#Sta/Elev= 30
       0 3800.04       8 3799.45    20.4 3797.56    36.1 3797.08    56.2 3796.81
   117.1 3796.77   120.3 3796.48   139.8 3791.64   145.2 3789.67   148.53787.903
   149.5 3787.42   153.5 3787.16   190.9 3787.19   195.1 3787.32   197.43787.765
   203.4 3789.46   211.7 3790.65   233.7 3792.03   253.3 3794.48   257.4 3795.55
   261.6 3797.71   265.8 3798.95   274.1 3799.45   278.2 3800.13   282.4 3800.25
   286.5 3799.83   290.7 3798.72   294.9 3798.18     299 3798.82     307 3801.34
#Mann= 3 ,-1,0
       0      .1       0   148.5    .045       0   197.4      .1       0
Bank Sta=148.5,197.4
XS Rating Curve= 0 ,0
Exp/Cntr(USF)=0,0
Exp/Cntr=0.3,0.1

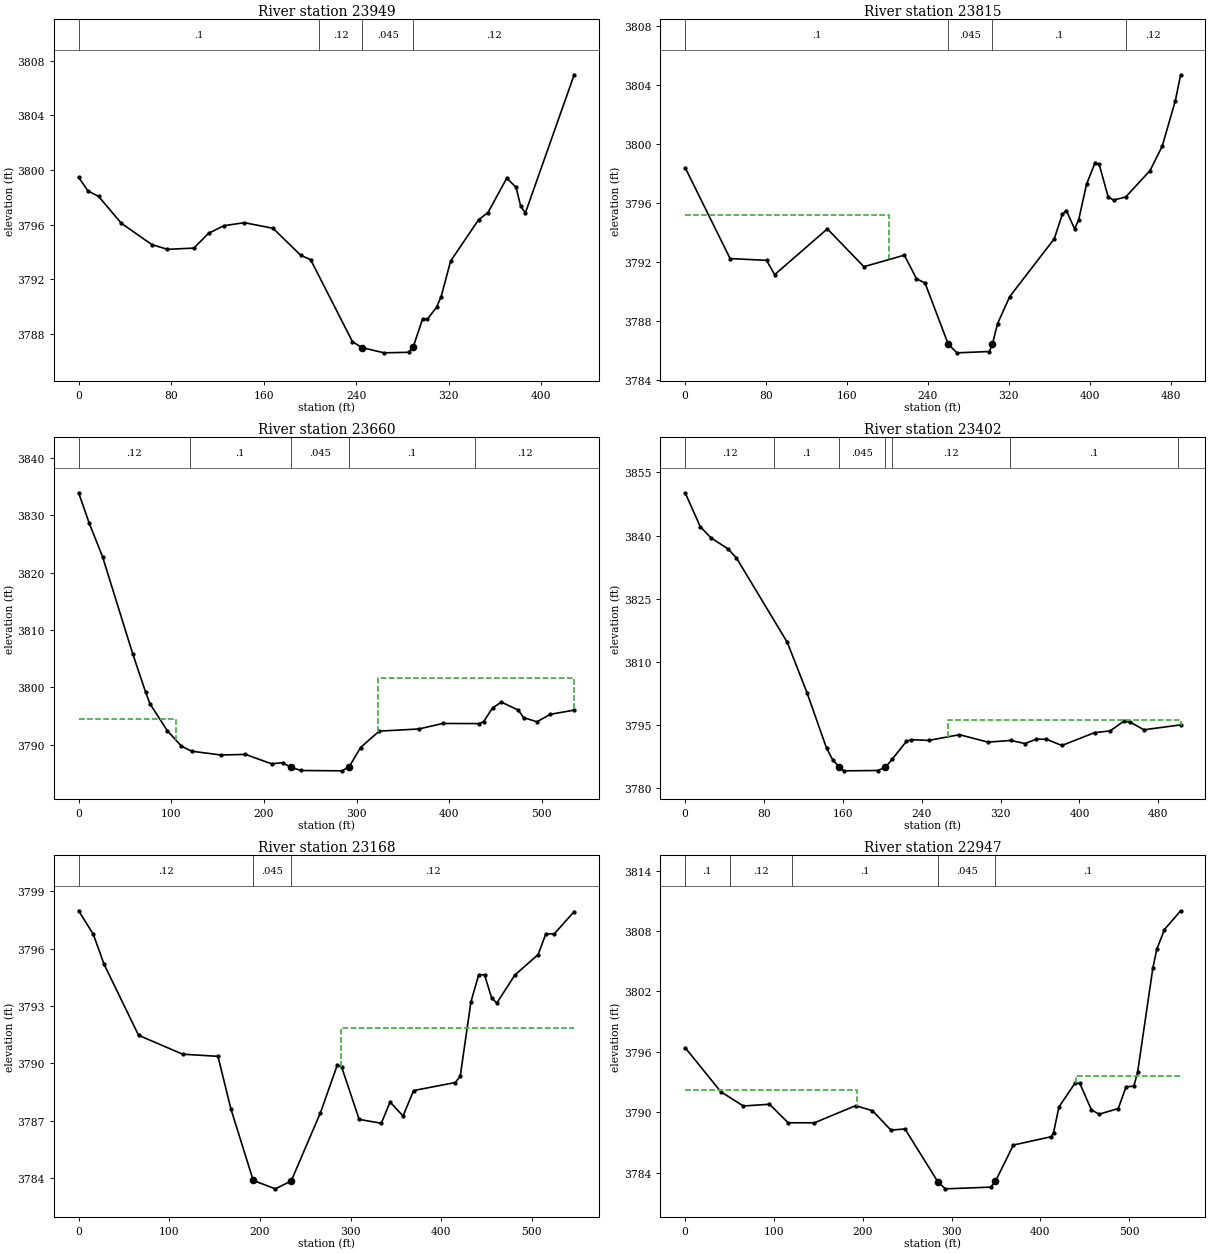
Type RM Length L Ch R = 1 ,23949   ,136.6,133.8,130.2
XS GIS Cut Line= 3
2266102.84211004540917.7217772292266236.52840952540981.571950117
  2266513.877598541021.478308172
#Sta/Elev= 30
       0 3799.47       8 3798.48    17.3 3798.07    36.9 3796.11    63.4 3794.54
    76.8  3794.2    99.6 3794.29   112.3 3795.37   125.6 3795.93   143.3 3796.15
     168 3795.74   192.2 3793.75   200.5 3793.45   236.7 3787.44   244.93787.004
   264.1 3786.62   285.2 3786.66   289.2 3787.04   297.3 3789.09   301.4 3789.08
   309.4 3789.95   313.4 3790.74   321.6 3793.34   345.8 3796.37   353.9 3796.89
   370.1 3799.41   378.1 3798.75   382.2 3797.35   386.2 3796.86   428.4 3806.98
#Mann= 4 ,-1,0
       0      .1       0  208.15     .12       0   244.9    .045       0
   289.2     .12       0
Bank Sta=244.9,289.2
XS Rating Curve= 0 ,0
Exp/Cntr(USF)=0,0
Exp/Cntr=0.3,0.1

Type RM Length L Ch R = 1 ,23815   ,156.8,155.2,153.9
XS GIS Cut Line= 3
2266059.75271615541116.2560698542266464.92824368541137.522188702
2266541.03856376541101.705567485
#Sta/Elev= 30
       0 3798.39    44.5 3792.23    80.5 3792.11    88.5 3791.14   140.6 3794.24
   176.7 3791.68   216.7 3792.46   228.7 3790.87   237.2 3790.57   260.1 3786.43
   268.8 3785.85   300.8 3785.94   303.8 3786.45   308.8 3787.82   320.9 3789.66
   364.9 3793.57   372.9 3795.24   376.9 3795.47     385 3794.24     389 3794.85
   396.8 3797.26     405 3798.68   409.3  3798.6   418.2  3796.4   423.5 3796.19
   435.5  3796.4   459.5 3798.18   471.6 3799.84   484.5  3802.9   489.8 3804.67
#Mann= 4 ,-1,0
       0      .1       0   260.1    .045       0   303.8      .1       0
  435.73     .12       0
#XS Ineff= 2 , 0
          201.46 3795.15
Permanent Ineff=
       F       F
Bank Sta=260.1,303.8
XS Rating Curve= 0 ,0
Exp/Cntr(USF)=0,0
Exp/Cntr=0.3,0.1

Type RM Length L Ch R = 1 ,23660   ,279.2,258.3,234.2
XS GIS Cut Line= 4
2266094.32588175541378.7830245222266250.25814467541284.142590957
2266475.96655785541288.850907138 2266581.7184067541219.014780542
#Sta/Elev= 30
       0 3833.96    11.5 3828.62    25.8  3822.8    58.3 3805.89    72.3 3799.15
      77 3797.12    95.7 3792.43     111 3789.72   121.9 3788.84   153.9 3788.17
     180 3788.28   208.3 3786.64   220.3 3786.84228.77273786.028   240.2 3785.47
   284.3 3785.41292.05893786.118   304.3 3789.48   324.4 3792.34   367.2 3792.72
     393 3793.68   432.4 3793.66   437.2 3794.01   446.8 3796.39   456.3 3797.41
   474.5 3796.02   480.3 3794.71   494.7 3793.97   509.1 3795.28   534.9 3796.01
#Mann= 5 ,-1,0
       0     .12       0     120      .1       0228.7727    .045       0
292.0589      .1       0  428.16     .12       0
#XS Ineff= 2 , 0
          104.73 3794.48   323.2         3801.61
Permanent Ineff=
       F       F
Bank Sta=228.7727,292.0589
XS Rating Curve= 0 ,0
Exp/Cntr(USF)=0,0
Exp/Cntr=0.3,0.1

Type RM Length L Ch R = 1 ,23402   ,245.4,234.2,222.9
XS GIS Cut Line= 2
 2266220.5658663541638.0315401162266631.60135426 541348.71044422
#Sta/Elev= 30
       0 3850.18    15.4 3842.13    26.2 3839.49    43.5 3836.87      52 3834.74
   103.7 3814.65   123.8 3802.61   143.5 3789.52   149.6 3786.82   156.1 3785.11
   161.1 3784.16   195.2 3784.24     203 3784.96     210  3786.9   224.5 3791.16
   229.4 3791.55   247.2 3791.39   278.3 3792.74   307.3 3790.97   330.5 3791.38
   344.8 3790.63   355.9 3791.67   366.4 3791.66   382.2 3790.18   415.3 3793.23
     431 3793.63   444.7  3795.9   451.1 3795.75   465.4 3793.91   502.6 3795.07
#Mann= 7 ,-1,0
       0     .12       0      90      .1       0   156.1    .045       0
     203      .1       0     210     .12       0     330      .1       0
     500     .12       0
#XS Ineff= 2 , 0
                          266.39         3796.19
Permanent Ineff=
       F       F
Bank Sta=156.1,203
XS Rating Curve= 0 ,0
Exp/Cntr(USF)=0,0
Exp/Cntr=0.3,0.1

Type RM Length L Ch R = 1 ,23168   ,215.8,220.6,226
XS GIS Cut Line= 3
2266408.12574916541875.4743705422266661.53112281541510.331194341
2266741.34383891541446.481021454
#Sta/Elev= 30
       0 3797.98    16.1 3796.76    28.1 3795.18    66.1 3791.47   114.8 3790.48
   153.7 3790.37     168 3787.62   192.63783.881     217 3783.44   234.5 3783.85
   266.7 3787.41   285.2 3789.89   290.1 3789.82   309.5 3787.07   333.9 3786.87
   343.6 3787.98   357.9 3787.25   369.6 3788.58   415.6    3789     421 3789.33
   432.8 3793.22   441.4 3794.64   447.8 3794.63   455.7 3793.41   461.4 3793.16
   481.3 3794.62   506.9 3795.69   515.5 3796.78   524.7 3796.77   546.7 3797.94
#Mann= 3 ,-1,0
       0     .12       0   192.6    .045       0   234.5     .12       0
#XS Ineff= 2 , 0
                          288.94         3791.84
Permanent Ineff=
       F       F
Bank Sta=192.6,234.5
XS Rating Curve= 0 ,0
Exp/Cntr(USF)=0,0
Exp/Cntr=0.3,0.1

Type RM Length L Ch R = 1 ,22947   ,182.1,209,241.2
XS GIS Cut Line= 4
 2266438.0555177541979.2309014842266629.60603636541915.380728596
2266791.22678648 541735.802117352266896.97863533 541691.90512349
#Sta/Elev= 30
       0 3796.41    40.2 3792.03    65.5 3790.61      95 3790.78   116.1 3788.94
   145.6 3788.94     192 3790.64     211 3790.14   231.8 3788.21   247.6 3788.33
   284.6 3783.08   293.1 3782.38   344.1 3782.55   349.4 3783.12   369.6 3786.73
   412.1 3787.55   414.9 3787.97     421 3790.52   438.9 3792.86   444.5 3792.86
   457.5 3790.23   466.2 3789.79   487.8 3790.36   496.5 3792.52   505.2 3792.57
   509.5 3793.94   526.8 3804.36   531.2 3806.18   539.8 3808.14     558    3810
#Mann= 5 ,-1,0
       0      .1       0      50     .12       0     120      .1       0
   284.6    .045       0   349.4      .1       0
#XS Ineff= 2 , 0
          193.74 3792.19   440.5         3793.55
Permanent Ineff=
       F       F
Bank Sta=284.6,349.4
XS Rating Curve= 0 ,0
Exp/Cntr(USF)=0,0
Exp/Cntr=0.3,0.1

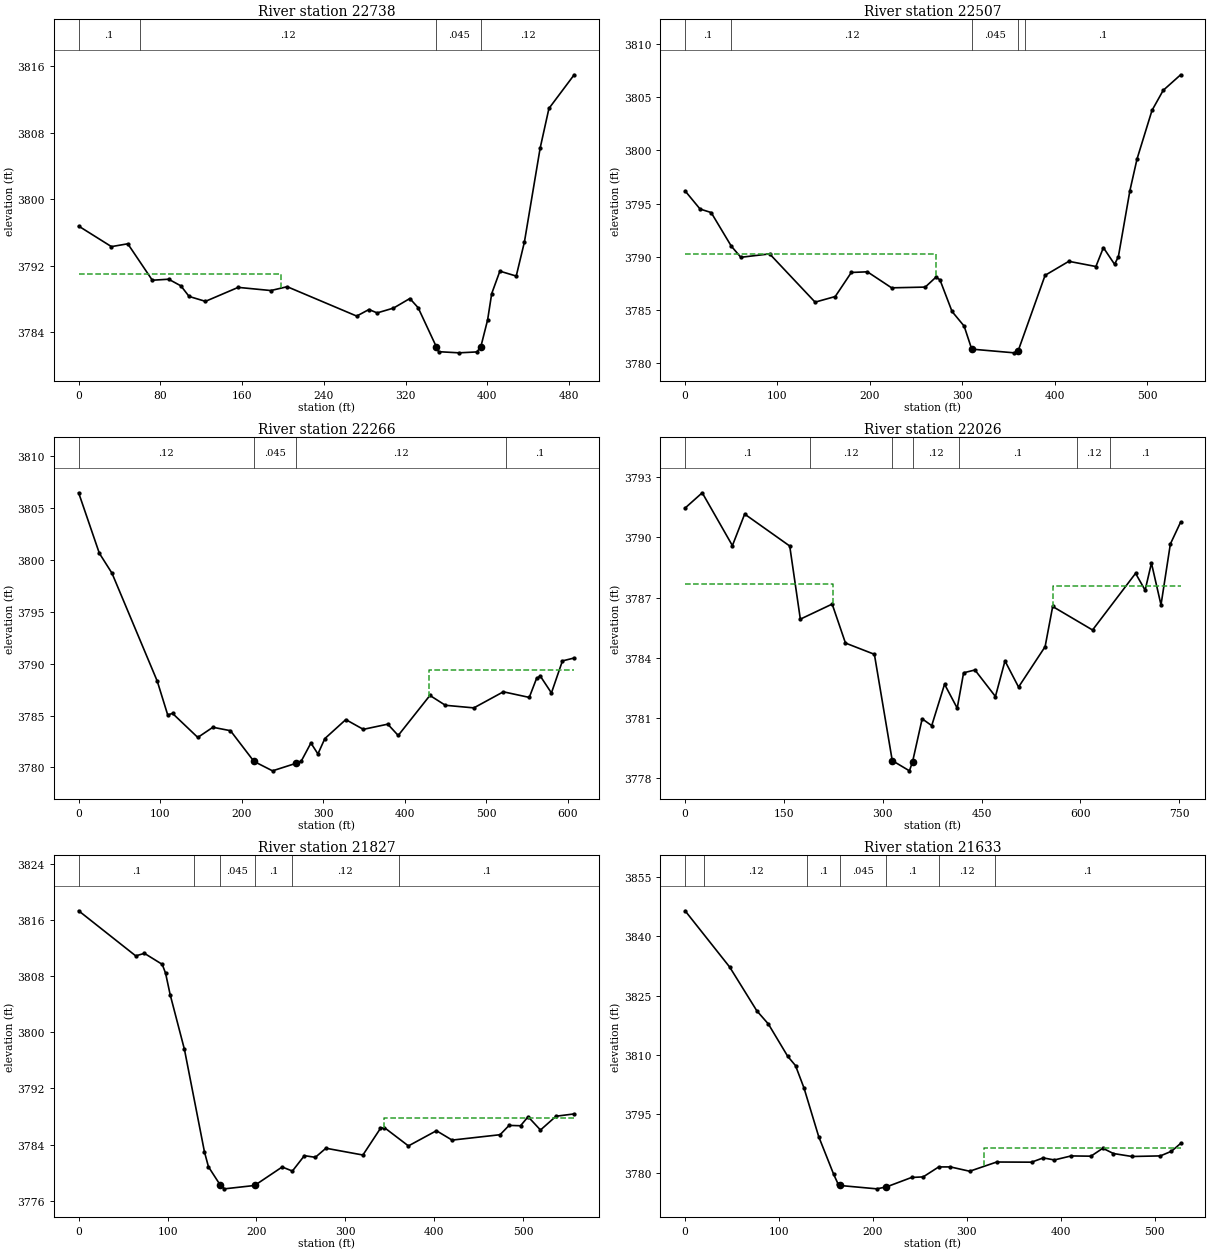
Type RM Length L Ch R = 1 ,22738   ,217.9,231.1,246.1
XS GIS Cut Line= 2
2266432.06956399542017.1419416362266916.93181436542009.160670025
#Sta/Elev= 30
       0 3796.77    32.1  3794.3    48.1 3794.64    72.1 3790.26    88.1 3790.38
   100.1 3789.58   108.1 3788.31   124.1 3787.72   156.1  3789.4   188.1 3789.02
   204.1 3789.48   272.1 3785.95   284.1 3786.74   292.1 3786.33   308.1 3786.91
   324.1 3788.06   332.2 3786.96   349.9 3782.29   352.2 3781.67   372.2 3781.53
   389.7 3781.64   393.6 3782.28   400.2 3785.49   404.2 3788.65   412.2 3791.35
   428.2 3790.76   436.2 3794.85   451.6 3806.14   460.2 3810.91   484.9 3814.96
#Mann= 4 ,-1,0
       0      .1       0      60     .12       0   349.9    .045       0
   393.6     .12       0
#XS Ineff= 2 , 0
          197.98 3791.05
Permanent Ineff=
       F       F
Bank Sta=349.9,393.6
XS Rating Curve= 0 ,0
Exp/Cntr(USF)=0,0
Exp/Cntr=0.3,0.1

Type RM Length L Ch R = 1 ,22507   ,243.8,241.1,240.6
XS GIS Cut Line= 4
 2266440.0508356542142.8469695082266527.84482332  542136.8610158
2266841.10973405542272.542633186 2266946.8615829542256.580089964
#Sta/Elev= 30
       0 3796.19    16.2 3794.48    28.2 3794.15      50 3790.98    60.3 3789.93
    91.5 3790.25   140.7  3785.7   162.5 3786.23   179.9  3788.5   197.3 3788.56
   223.5 3787.05   259.9 3787.12   271.4 3788.05   275.8 3787.81   288.9 3784.82
     302 3783.44   310.2 3781.27   356.2 3780.92   360.5 3781.12   389.6 3788.23
   415.3 3789.55   444.6 3789.06   452.7 3790.84   464.8 3789.27   468.9 3789.98
   481.4 3796.22   489.1  3799.2   505.3 3803.78   517.4 3805.67   536.3 3807.14
#Mann= 5 ,-1,0
       0      .1       0      50     .12       0   310.2    .045       0
   360.5     .12       0     368      .1       0
#XS Ineff= 2 , 0
          271.82 3790.24
Permanent Ineff=
       F       F
Bank Sta=310.2,360.5
XS Rating Curve= 0 ,0
Exp/Cntr(USF)=0,0
Exp/Cntr=0.3,0.1

Type RM Length L Ch R = 1 ,22266   ,268.3,240.1,212.7
XS GIS Cut Line= 3
2266402.13979545542354.350667198 2266807.1893297542509.985463611
2266960.82880822542428.177429599
#Sta/Elev= 30
       0 3806.48    25.4 3800.65    40.9 3798.73    96.5 3788.31   109.3 3785.06
   115.2 3785.21   146.2 3782.89   164.7 3783.87   186.3 3783.54   215.13780.581
   237.9 3779.67   266.9  3780.4   273.1  3780.6     285 3782.35   293.6  3781.3
   302.1 3782.78   327.8 3784.61   349.3 3783.67   379.3 3784.17   392.1 3783.08
     431 3786.94     450 3785.99   484.9 3785.74   521.1 3787.29   552.9 3786.75
   561.9 3788.59   566.5  3788.8   580.1 3787.18   593.6 3790.27     608 3790.55
#Mann= 4 ,-1,0
       0     .12       0   215.1    .045       0   266.9     .12       0
  523.92      .1       0
#XS Ineff= 2 , 0
                          429.65         3789.38
Permanent Ineff=
       F       F
Bank Sta=215.1,266.9
XS Rating Curve= 0 ,0
Exp/Cntr(USF)=0,0
Exp/Cntr=0.3,0.1

Type RM Length L Ch R = 1 ,22026   ,210.3,198.6,184.5
XS GIS Cut Line= 3
2266302.37390031542683.5781211492266565.75586347 542713.50788969
2266968.81007983542440.149337015
#Sta/Elev= 30
       0 3791.46      26 3792.22    71.8 3789.59    90.4 3791.16   158.8 3789.57
   174.9 3785.93   223.2 3786.68   243.4 3784.74   287.3 3784.18   314.4 3778.89
   340.5 3778.38   345.3 3778.84   359.8 3780.97   374.3 3780.63   393.8 3782.69
     413  3781.5   422.7 3783.26   439.9  3783.4     471 3782.08   485.5 3783.85
   506.1 3782.55   546.4 3784.56   557.9 3786.56   618.4 3785.39   683.7 3788.21
   698.2 3787.37   707.8 3788.72   722.3 3786.64   736.5 3789.67   752.1 3790.76
#Mann= 7 ,-1,0
       0      .1       0     190     .12       0   314.4    .045       0
   345.3     .12       0  415.08      .1       0  595.08     .12       0
  645.08      .1       0
#XS Ineff= 2 , 0
          224.36 3787.67  558.39          3787.6
Permanent Ineff=
       F       F
Bank Sta=314.4,345.3
XS Rating Curve= 0 ,0
Exp/Cntr(USF)=0,0
Exp/Cntr=0.3,0.1

Type RM Length L Ch R = 1 ,21827   ,202.4,194.2,187.2
XS GIS Cut Line= 3
2266699.44216296542942.969448504 2266883.6898181542584.829838143
2267006.24224368542490.690739492
#Sta/Elev= 30
       0 3817.38    64.2 3810.94      74  3811.3      94 3809.73    97.8 3808.46
   102.9 3805.42     119 3797.58   141.5 3782.95     146 3780.82   159.43778.185
     164 3777.67   197.9 3778.15   228.9 3780.79   240.4 3780.21   253.9 3782.41
   266.2 3782.17   278.1 3783.47   319.7  3782.5   339.4  3786.3   343.9 3786.41
   370.9  3783.8   402.4 3785.97     420 3784.63     474  3785.4   484.1 3786.73
     497 3786.68   505.5 3787.97   519.4 3786.07   536.9 3788.04   557.3 3788.37
#Mann= 6 ,-1,0
       0      .1       0     130     .12       0   159.4    .045       0
   197.9      .1       0     240     .12       0     360      .1       0
#XS Ineff= 2 , 0
                          343.63         3787.75
Permanent Ineff=
       F       F
Bank Sta=159.4,197.9
XS Rating Curve= 0 ,0
Exp/Cntr(USF)=0,0
Exp/Cntr=0.3,0.1

Type RM Length L Ch R = 1 ,21633   ,166.3,179.1,191.8
XS GIS Cut Line= 3
2266914.39416905543043.2722836892267006.51799662 542673.16076591
 2267114.8038992542574.572108336
#Sta/Elev= 30
       0 3846.48    47.5 3832.21    76.4 3821.12    88.7 3817.78   109.3 3809.59
   117.6 3807.24   126.7 3801.52   142.3 3789.24   158.3 3779.65   162.9 3777.26
   164.9 3776.85   204.1    3776   214.5 3776.49   241.2 3778.88   253.6 3779.03
   270.1 3781.55   282.5 3781.56   303.1 3780.46   331.9  3782.8     369 3782.76
   381.4 3783.84   393.3 3783.32   411.1 3784.34   432.3 3784.28   444.9 3786.29
   456.2 3784.95     476  3784.2   506.2 3784.35     518 3785.52   527.8 3787.51
#Mann= 7 ,-1,0
       0      .1       0      20     .12       0     130      .1       0
   164.9    .045       0   214.5      .1       0     270     .12       0
     330      .1       0
#XS Ineff= 2 , 0
                          318.58         3786.31
Permanent Ineff=
       F       F
Bank Sta=164.9,214.5
XS Rating Curve= 0 ,0
Exp/Cntr(USF)=0,0
Exp/Cntr=0.3,0.1

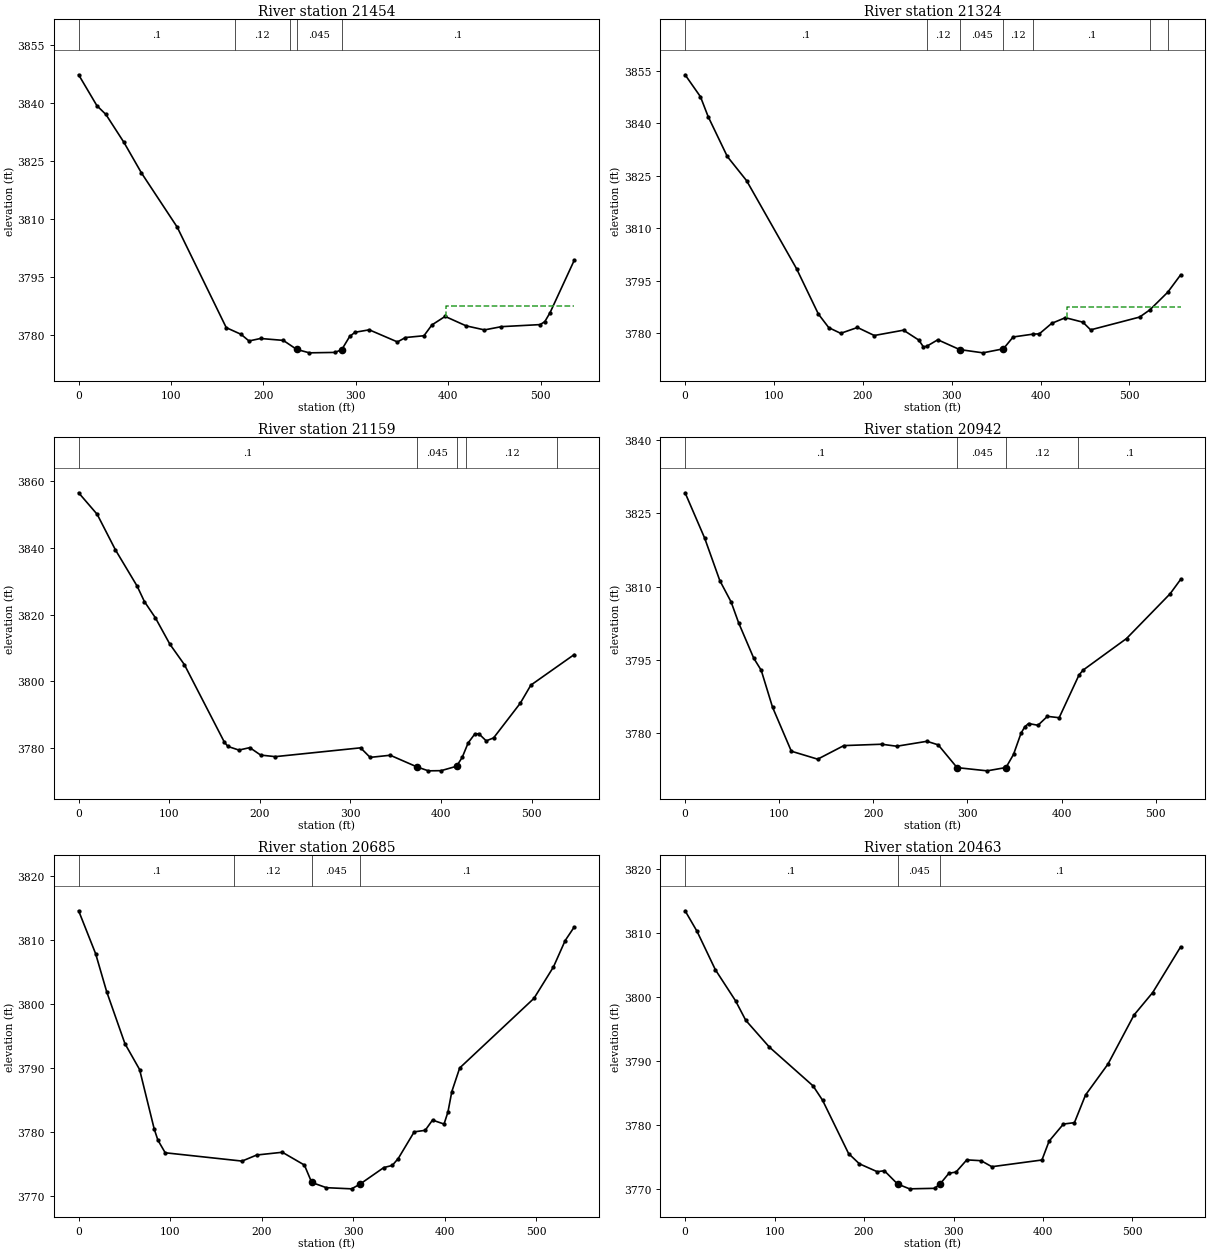
Type RM Length L Ch R = 1 ,21454   ,130.4,129.5,128.5
XS GIS Cut Line= 4
2266943.70097893543068.7764391112267075.60365316542980.239027638
2267212.02354226542787.8056741322267320.43669917542696.557933737
#Sta/Elev= 30
       0 3847.32    19.8 3839.32    29.5 3837.07    49.1 3829.82      68 3821.94
   106.7 3807.93   159.8 3781.94   175.8 3780.22   184.4  3778.5   196.9 3779.14
   221.5 3778.65   236.1 3776.31   249.8 3775.43   277.4 3775.54   284.8 3776.25
   293.4 3779.67   299.2 3780.75   314.6 3781.38   345.1 3778.25   353.8 3779.39
   373.8 3779.85   382.4 3782.64   396.7 3784.85   419.4 3782.41   439.3 3781.36
   457.7  3782.2   499.5 3782.73   504.6 3783.49   510.3 3785.82   536.4 3799.32
#Mann= 5 ,-1,0
       0      .1       0  168.86     .12       0  228.86      .1       0
   236.1    .045       0   284.8      .1       0
#XS Ineff= 2 , 0
                          397.49         3787.52
Permanent Ineff=
       F       F
Bank Sta=236.1,284.8
XS Rating Curve= 0 ,0
Exp/Cntr(USF)=0,0
Exp/Cntr=0.3,0.1

Type RM Length L Ch R = 1 ,21324   ,152.2,165.7,181.4
XS GIS Cut Line= 5
  2266976.224926543149.182863815  2267116.258587543091.362513466
2267192.14779683543043.4800358332267298.75406779542884.474072372
2267404.45689577542817.619292281
#Sta/Elev= 30
       0 3853.86    17.3 3847.59    25.9 3841.94    47.5 3830.53    69.2 3823.63
   125.4 3798.51     150 3785.55   161.7 3781.66   175.1 3780.04     194 3781.71
   212.9 3779.42   245.8 3780.94   263.1  3778.1   268.1  3776.2   271.7 3776.31
   284.4  3778.2     3093775.405   335.2 3774.47   358.2 3775.62   369.2    3779
   392.1 3779.83   398.6 3779.88   412.6 3782.89     428 3784.51   447.7 3783.22
   456.4 3781.03   511.5 3784.68   523.1 3786.75   543.2 3791.78   557.7 3796.74
#Mann= 7 ,-1,0
       0      .1       0   271.7     .12       0     309    .045       0
   358.2     .12       0   392.1      .1       0   523.1     .12       0
   543.2      .1       0
#XS Ineff= 2 , 0
                          429.65         3787.49
Permanent Ineff=
       F       F
Bank Sta=309,358.2
XS Rating Curve= 0 ,0
Exp/Cntr(USF)=0,0
Exp/Cntr=0.3,0.1

Type RM Length L Ch R = 1 ,21159   ,200.2,216.9,233
XS GIS Cut Line= 4
2266971.70771113543161.8310654542267268.03700667543141.955320022
2267389.09836521543068.7764391112267494.80119319543044.383478807
#Sta/Elev= 30
       0 3856.51    20.5 3850.05    40.6 3839.42    64.6 3828.54    72.6 3823.93
    84.7 3819.07   100.7 3811.17   116.7 3805.05   160.8 3781.85   164.8 3780.54
   176.9 3779.46   188.9 3780.19   200.9 3777.96     217 3777.49   311.2 3780.13
   321.7 3777.27   343.9 3777.91   373.4 3774.42     386 3773.24     400 3773.29
   417.1 3774.61   423.4 3777.31   429.9 3781.61   436.9 3784.15   441.6 3784.38
   449.8 3782.21     458 3783.11   487.4 3793.49   499.1 3798.91   546.9 3808.05
#Mann= 5 ,-1,0
       0      .1       0   373.4    .045       0   417.1      .1       0
     427     .12       0  528.46      .1       0
Bank Sta=373.4,417.1
XS Rating Curve= 0 ,0
Exp/Cntr(USF)=0,0
Exp/Cntr=0.3,0.1

Type RM Length L Ch R = 1 ,20942   ,254.9,256.6,258.7
XS GIS Cut Line= 3
2267059.34167962543314.5129280952267446.91871556543302.768169431
2267578.82138979543259.402906669
#Sta/Elev= 30
       0 3829.23    20.8 3819.94    36.9 3811.24    48.9 3806.87    56.9 3802.59
    72.9 3795.37    80.9 3792.87    92.9 3785.32   112.9  3776.3   140.9 3774.67
   168.7 3777.45   208.9 3777.73   224.9 3777.32     257 3778.33     269  3777.6
     289 3772.94     321 3772.28     341 3772.96     349 3775.64     357 3779.99
     361 3781.31     365 3781.97     375 3781.61     385 3783.44   397.5 3783.16
   418.5 3791.87   422.8 3792.89   469.1 3799.38   515.4 3808.54   526.6 3811.49
#Mann= 4 ,-1,0
       0      .1       0     289    .045       0     341     .12       0
  417.75      .1       0
Bank Sta=289,341
XS Rating Curve= 0 ,0
Exp/Cntr(USF)=0,0
Exp/Cntr=0.3,0.1

Type RM Length L Ch R = 1 ,20685   ,221.9,222,222
XS GIS Cut Line= 3
 2267109.5739198543555.4102645272267499.07992759543563.491302033
 2267641.3061877543510.156454493
#Sta/Elev= 30
       0 3814.61    18.6 3807.89    30.6 3801.98    50.6 3793.83    66.6 3789.79
    82.6 3780.48    86.6 3778.75    94.6 3776.77   178.6 3775.47   194.6 3776.42
   222.6 3776.85   246.7 3774.85   254.7 3772.13   270.7 3771.31   298.2 3771.13
   307.1 3771.83   333.5 3774.46   342.7 3774.79   349.2 3775.86   366.7 3780.04
   378.7 3780.28   386.7 3781.88   399.3 3781.26   403.6 3783.16   407.8 3786.34
   416.4 3790.03   497.6 3800.92   518.9 3805.84   531.7 3809.96   541.5 3812.06
#Mann= 4 ,-1,0
       0      .1       0     170     .12       0   254.7    .045       0
   307.1      .1       0
Bank Sta=254.7,307.1
XS Rating Curve= 0 ,0
Exp/Cntr(USF)=0,0
Exp/Cntr=0.3,0.1

Type RM Length L Ch R = 1 ,20463   ,245.1,225.6,200.2
XS GIS Cut Line= 4
2267161.43073571543877.3579010272267291.52652399543780.689502786
2267556.23531544543787.0136036062267678.20011696543751.779327612
#Sta/Elev= 30
       0 3813.52    13.4 3810.29    33.8 3804.31    56.4 3799.44    67.8 3796.39
    94.2  3792.2     143 3786.14   153.6  3783.9   182.7 3775.56   194.7 3773.96
   214.7 3772.72   222.7 3772.87   237.4  3770.8   250.8 3770.04   278.8 3770.12
   284.83770.772   294.8 3772.47   302.8 3772.67   314.8 3774.57   330.8 3774.44
   342.8  3773.5   398.8 3774.55   406.8  3777.5   422.8 3780.17   435.1 3780.39
   447.5 3784.71   472.6 3789.55   501.7 3797.22   522.6 3800.74   553.8 3807.88
#Mann= 3 ,-1,0
       0      .1       0   237.4    .045       0   284.8      .1       0
Bank Sta=237.4,284.8
XS Rating Curve= 0 ,0
Exp/Cntr(USF)=0,0
Exp/Cntr=0.3,0.1