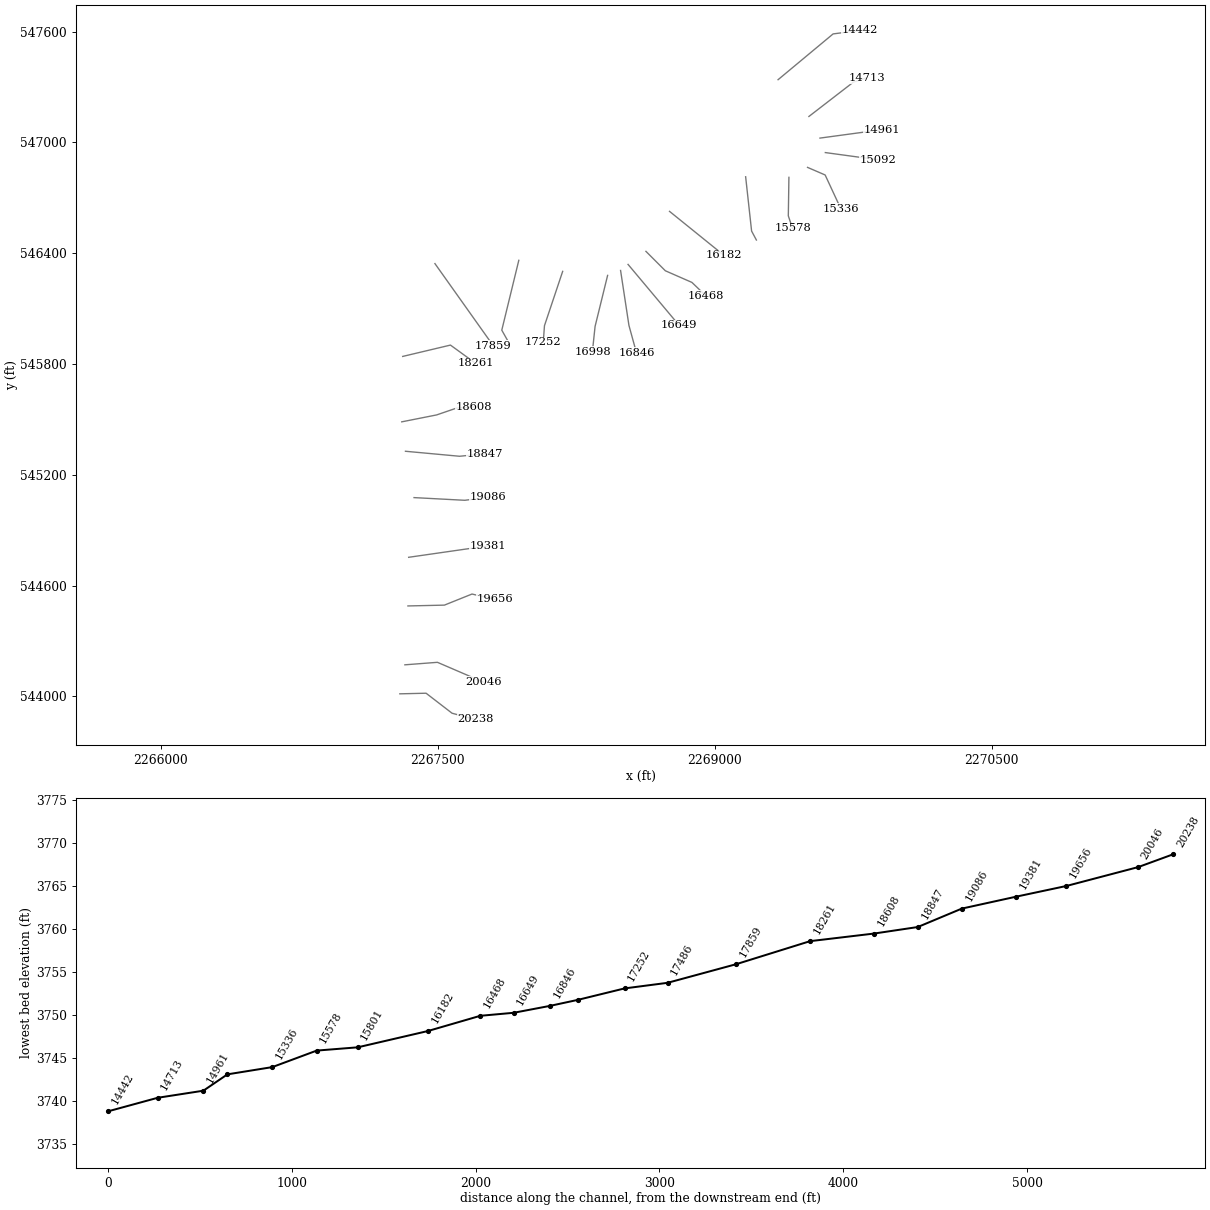
HEC-RAS study SHVRSFK.prj: SHVRSFK

--- SHVRSFK.g01 (geometry) --- (continued)

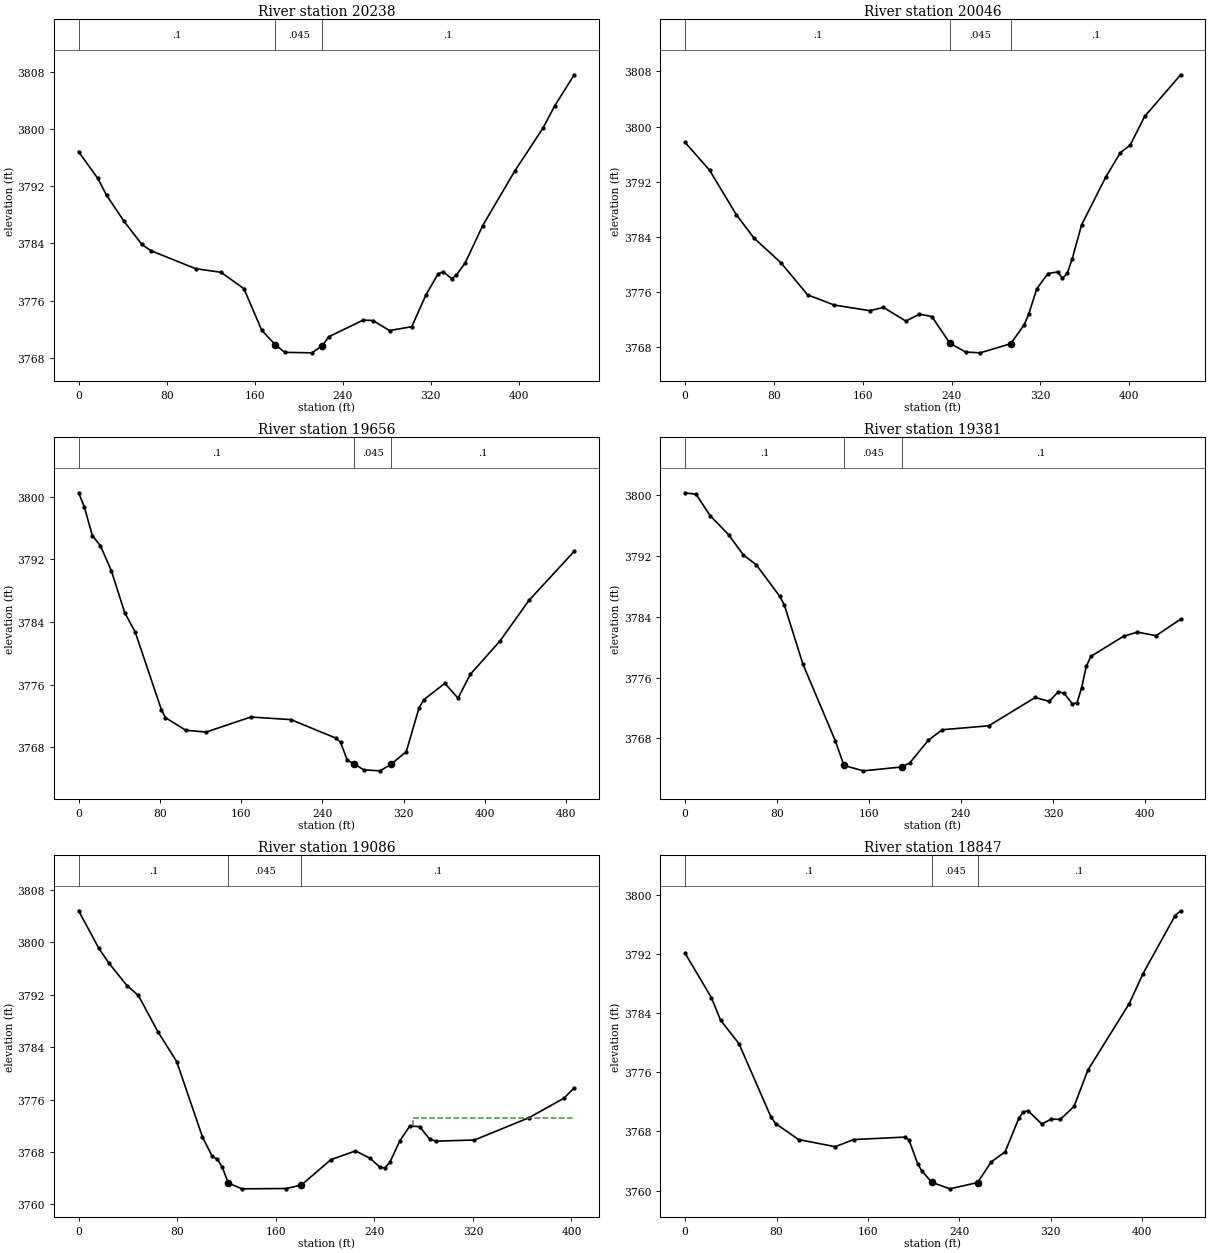
Type RM Length L Ch R = 1 ,20238   ,185.4,191.9,202.4
XS GIS Cut Line= 4
2267294.81579783544013.9410580532267437.04205794544017.173473056
2267577.65211055543908.8875704742267703.71629564543874.947212949
#Sta/Elev= 30
       0 3796.79    17.4 3793.08    25.4 3790.71    41.4 3787.05    57.4 3783.86
    65.4 3782.99   106.2 3780.46   129.4 3779.95   150.2 3777.66   166.4 3771.84
   178.7 3769.82   187.3 3768.76   211.9 3768.69   221.5 3769.69   227.2 3770.93
   258.6 3773.27   267.4 3773.21   282.5 3771.81   302.7 3772.34   315.6 3776.78
   326.5 3779.71   331.3 3780.04   338.9 3779.06   343.1 3779.52   351.3 3781.27
   367.2 3786.49   396.6 3794.17   421.8 3800.07   432.5 3803.18   450.3 3807.56
#Mann= 3 ,-1,0
       0      .1       0   178.7    .045       0   221.5      .1       0
Bank Sta=178.7,221.5
XS Rating Curve= 0 ,0
Exp/Cntr(USF)=0,0
Exp/Cntr=0.3,0.1

Type RM Length L Ch R = 1 ,20046   ,363.5,389.9,413.3
XS GIS Cut Line= 3
2267322.24358512544170.9768676442267498.41496509544184.528512257
2267745.95834002544077.922241301
#Sta/Elev= 30
       0 3797.69      22 3793.68    46.1 3787.22    62.1 3783.81    86.2 3780.27
   110.3  3775.6   134.3 3774.12   166.4  3773.3   178.6 3773.78   198.8 3771.79
     211  3772.8   222.2 3772.45   238.4 3768.59   252.6 3767.31   265.7 3767.19
   293.2 3768.51   305.4 3771.28   309.3 3772.75   316.6 3776.45   326.6 3778.68
   335.4 3778.92   339.7    3778   344.1 3778.71   348.5 3780.78   357.1 3785.77
   378.9 3792.71     392 3796.22   400.7 3797.29   413.8 3801.46   446.2  3807.5
#Mann= 3 ,-1,0
       0      .1       0   238.4    .045       0   293.2      .1       0
Bank Sta=238.4,293.2
XS Rating Curve= 0 ,0
Exp/Cntr(USF)=0,0
Exp/Cntr=0.3,0.1

Type RM Length L Ch R = 1 ,19656   ,283.9,275,266.3
XS GIS Cut Line= 4
2267338.67385476544489.797202534 2267536.1185815544494.216964544
2267685.54608555544554.2245641612267811.61027064544525.132829139
#Sta/Elev= 30
       0  3800.5     5.5 3798.72    13.5 3795.04    21.5 3793.73    32.2 3790.54
    45.5 3785.15    55.7 3782.72    81.5  3772.8    85.5 3771.79   105.5 3770.18
   125.5 3769.95   169.5 3771.87     209 3771.54   253.6 3769.16   257.9 3768.63
   264.4  3766.4   271.5 3765.87   280.6 3765.13   296.7    3765   307.5 3765.82
   307.5 3765.83   322.6 3767.45   335.1 3773.02   339.8 3774.08   360.6 3776.18
   373.5 3774.28   385.8 3777.35   414.6 3781.53   443.3 3786.75   487.9 3793.02
#Mann= 3 ,-1,0
       0      .1       0   271.5    .045       0   307.5      .1       0
Bank Sta=271.5,307.5
XS Rating Curve= 0 ,0
Exp/Cntr(USF)=0,0
Exp/Cntr=0.3,0.1

Type RM Length L Ch R = 1 ,19381   ,301.2,294.4,287.9
XS GIS Cut Line= 2
2267342.68915687544753.2198199742267769.36793719 544814.63570502
#Sta/Elev= 30
       0 3800.29     9.6 3800.08    21.7  3797.3    37.9 3794.77    50.7 3792.12
    62.1  3790.8    82.3 3786.69    86.4 3785.51   102.5 3777.77   130.8 3767.65
   138.23764.456   155.1 3763.75   188.5 3764.26   195.5  3764.8   211.6 3767.77
   223.7 3769.15   264.2 3769.67   304.6 3773.39   316.7 3772.88   324.8 3774.16
   329.8 3773.93   336.9 3772.56     341 3772.67     345  3774.7     349 3777.49
   353.1  3778.8   381.4 3781.43   393.5 3781.98   409.7 3781.51   431.1 3783.68
#Mann= 3 ,-1,0
       0      .1       0   138.2    .045       0   188.5      .1       0
Bank Sta=138.2,188.5
XS Rating Curve= 0 ,0
Exp/Cntr(USF)=0,0
Exp/Cntr=0.3,0.1

Type RM Length L Ch R = 1 ,19086   ,242.6,239.5,238.2
XS GIS Cut Line= 3
2267371.78089189545076.461320217 2267646.5361671545061.915452706
2267772.60035219545078.077527718
#Sta/Elev= 30
       0 3804.81    16.4 3799.08    24.4 3796.86    39.2  3793.4    48.5 3791.88
    64.5 3786.29    79.6  3781.8   100.5 3770.28   108.5 3767.31   112.6 3766.88
   116.6 3765.68   121.4 3763.26   132.6 3762.37   168.6 3762.42   180.83762.952
   204.7 3766.82   224.7 3768.16   236.7 3767.01   244.7 3765.64   248.7 3765.58
   252.7 3766.45   260.8 3769.74   268.8 3771.95   276.8 3771.86   284.9 3769.95
   290.2 3769.65   321.2 3769.82   365.5 3773.22   393.9  3776.2   402.2 3777.77
#Mann= 3 ,-1,0
       0      .1       0   121.4    .045       0   180.8      .1       0
#XS Ineff= 2 , 0
                           271.4         3773.22
Permanent Ineff=
       F       F
Bank Sta=121.4,180.8
XS Rating Curve= 0 ,0
Exp/Cntr(USF)=0,0
Exp/Cntr=0.3,0.1

Type RM Length L Ch R = 1 ,18847   ,226.4,238.5,253.6
XS GIS Cut Line= 3
2267325.31522085545327.392151869 2267618.4322747545300.288862643
2267756.96019742545314.342420019
#Sta/Elev= 30
       0  3792.1      23  3786.1      31 3783.06    47.1 3779.88    75.2 3769.93
    79.2 3769.06    99.3  3766.9   131.4 3765.93   147.5  3766.9   192.2 3767.23
   195.9 3766.83   203.7 3763.55   206.9 3762.71   215.8 3761.11   231.8 3760.23
   255.9 3761.08     268  3763.9     280 3765.22   292.1 3769.81   296.1 3770.64
   300.1 3770.79   312.2 3768.99   320.2 3769.67   328.3 3769.62   340.3 3771.38
   352.4 3776.28   388.6 3785.29   400.7 3789.35   428.8 3797.21   433.6 3797.85
#Mann= 3 ,-1,0
       0      .1       0   215.8    .045       0   255.9      .1       0
Bank Sta=215.8,255.9
XS Rating Curve= 0 ,0
Exp/Cntr(USF)=0,0
Exp/Cntr=0.3,0.1

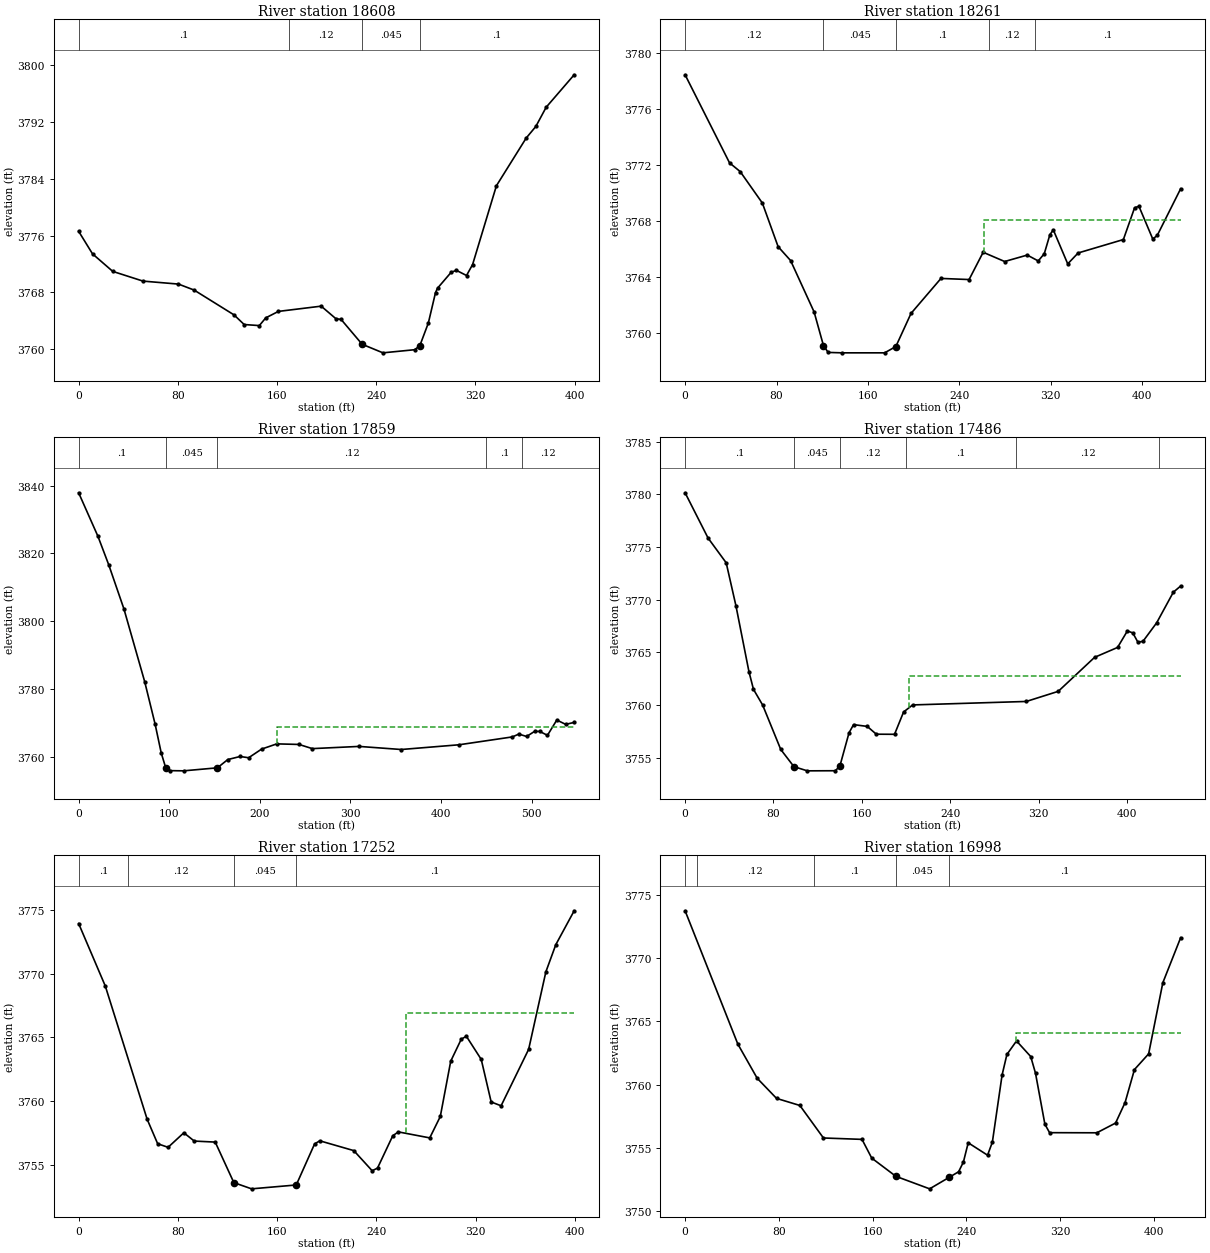
Type RM Length L Ch R = 1 ,18608   ,349.8,347,342.9
XS GIS Cut Line= 4
2267305.22580737545486.7258590712267493.95790937545524.141955141
2267602.37106627545561.2834996362267694.73181516545567.536234132
#Sta/Elev= 30
       0  3776.6    11.2 3773.42    27.5 3770.95    51.9 3769.58    80.5 3769.16
    93.1 3768.32   125.3 3764.82   133.5 3763.46   145.7 3763.31   150.9  3764.4
   161.1 3765.31   195.6 3766.05   207.4 3764.29   211.7 3764.17   228.6 3760.68
   245.4 3759.47   270.9 3759.91   275.1 3760.46     282 3763.67   287.8 3767.97
   289.4 3768.58   300.5 3770.84   304.7 3771.09   312.8 3770.37   317.7 3771.92
   336.9 3783.02   360.9 3789.74   368.7 3791.38     377 3794.08   399.6 3798.66
#Mann= 4 ,-1,0
       0      .1       0     170     .12       0   228.6    .045       0
   275.1      .1       0
Bank Sta=228.6,275.1
XS Rating Curve= 0 ,0
Exp/Cntr(USF)=0,0
Exp/Cntr=0.3,0.1

Type RM Length L Ch R = 1 ,18261   ,440.6,402.8,346.3
XS GIS Cut Line= 3
2267310.36500684545840.9274682912267568.95820704545902.343353338
2267704.71963714545803.754695763
#Sta/Elev= 30
       0 3778.47    38.9 3772.17    48.2 3771.55    67.6  3769.3    81.4 3766.18
    92.3 3765.19   112.9 3761.51   121.1  3759.1   125.2 3758.62   137.5 3758.59
   174.6 3758.59   184.4 3759.04   197.7 3761.41   223.9 3763.91   248.5 3763.83
   260.8 3765.78   279.6 3765.12   299.4 3765.58     309 3765.16   314.3 3765.68
   319.2 3767.04   322.2 3767.38   334.8 3764.95   343.9 3765.73   383.5 3766.69
   393.3 3768.96   397.1 3769.07   409.2 3766.73   413.1 3766.98   433.6 3770.32
#Mann= 5 ,-1,0
       0     .12       0   121.1    .045       0   184.4      .1       0
  265.79     .12       0  305.79      .1       0
#XS Ineff= 2 , 0
                          261.31          3768.1
Permanent Ineff=
       F       F
Bank Sta=121.1,184.4
XS Rating Curve= 0 ,0
Exp/Cntr(USF)=0,0
Exp/Cntr=0.3,0.1

Type RM Length L Ch R = 1 ,17859   ,401.8,372.7,339.2
XS GIS Cut Line= 2
2267484.91541697546343.5680011692267801.69208721545897.494730834
#Sta/Elev= 30
       0 3837.88    21.3 3825.06    33.3  3816.6      50 3803.65    72.9 3782.23
    84.4 3769.72    91.2 3761.17    96.1 3756.85   101.1 3755.97   115.9 3755.91
   153.2  3756.8   164.7 3759.24   178.3 3760.14   187.7 3759.77     202 3762.32
   218.8 3763.86   243.3 3763.69     258 3762.46   309.6 3763.11   356.2  3762.2
   419.9 3763.59   478.8 3765.91     486 3766.74   494.6 3766.04   503.3 3767.53
     509 3767.54   517.6 3766.38   527.9 3770.88   537.7 3769.62   547.1 3770.18
#Mann= 5 ,-1,0
       0      .1       0    96.1    .045       0   153.2     .12       0
     450      .1       0     490     .12       0
#XS Ineff= 2 , 0
                          218.79          3768.7
Permanent Ineff=
       F       F
Bank Sta=96.1,153.2
XS Rating Curve= 0 ,0
Exp/Cntr(USF)=0,0
Exp/Cntr=0.3,0.1

Type RM Length L Ch R = 1 ,17486   ,237,233.8,232.4
XS GIS Cut Line= 3
2267939.06972482546361.3462836832267846.94589725545983.153728398
2267876.03763227 545931.43508836
#Sta/Elev= 30
       0 3780.16    20.8 3775.86    37.2 3773.51      46 3769.44    57.8 3763.17
    61.9 3761.49    70.2    3760    86.6 3755.78    98.5 3754.15   110.6 3753.75
     136 3753.76   140.1  3754.2   148.4 3757.36   152.5 3758.14   164.9 3757.97
   173.1 3757.23   189.6 3757.22   197.8 3759.34     206 3760.01   308.9 3760.34
   337.8  3761.3   370.7 3764.53   391.5 3765.47   400.4 3767.04   405.3 3766.85
   409.9 3765.97   414.5 3766.05   426.9 3767.81     442 3770.72   448.6  3771.3
#Mann= 6 ,-1,0
       0      .1       0    98.5    .045       0   140.1     .12       0
     200      .1       0     300     .12       0  429.25      .1       0
#XS Ineff= 2 , 0
                          202.51         3762.74
Permanent Ineff=
       F       F
Bank Sta=98.5,140.1
XS Rating Curve= 0 ,0
Exp/Cntr(USF)=0,0
Exp/Cntr=0.3,0.1

Type RM Length L Ch R = 1 ,17252   ,252,254.1,257.4
XS GIS Cut Line= 3
2268176.65222749546301.5466061382268078.06356992546007.396840917
2268071.59873992 545918.50542835
#Sta/Elev= 30
       0 3773.93    21.5 3769.02    55.2 3758.57    63.7 3756.64    72.1 3756.36
    84.8  3757.5    93.2 3756.85   110.1 3756.77   125.13753.588   139.4  3753.1
   175.43753.403   190.2 3756.63   194.4 3756.87   221.8  3756.1   236.6 3754.52
   240.9 3754.73   253.2 3757.27   257.7 3757.57     283  3757.1   291.5 3758.78
   299.9 3763.12   308.4 3764.85   312.5 3765.08   324.5 3763.26   332.5 3759.92
   340.5 3759.62   362.7 3764.05   376.6 3770.14   384.6 3772.27   399.4 3774.93
#Mann= 4 ,-1,0
       0      .1       0      40     .12       0   125.1    .045       0
   175.4      .1       0
#XS Ineff= 2 , 0
                          264.16         3766.88
Permanent Ineff=
       F       F
Bank Sta=125.1,175.4
XS Rating Curve= 0 ,0
Exp/Cntr(USF)=0,0
Exp/Cntr=0.3,0.1

Type RM Length L Ch R = 1 ,16998   ,140.1,151.9,167
XS GIS Cut Line= 3
2268419.98631162546279.7530215172268352.10559657546003.381538809
2268337.55972906545866.003901206
#Sta/Elev= 30
       0 3773.75      45 3763.21    61.5 3760.51      78 3758.92    97.9 3758.36
     118 3755.79   150.9 3755.68   159.2  3754.2   179.8 3752.76   208.6 3751.77
   225.1 3752.67   233.3 3753.12   237.4 3753.89   241.5 3755.41     258 3754.43
   262.1 3755.46   270.4 3760.77   274.5 3762.39   282.7 3763.46   294.8 3762.23
   298.9 3760.91   306.9 3756.88   310.9 3756.21   351.2  3756.2   367.2 3756.97
   375.3 3758.59   383.3  3761.2   395.4 3762.44   407.5 3768.06   422.7 3771.62
#Mann= 5 ,-1,0
       0      .1       0      10     .12       0     110      .1       0
   179.8    .045       0   225.1      .1       0
#XS Ineff= 2 , 0
                          281.84         3764.05
Permanent Ineff=
       F       F
Bank Sta=179.8,225.1
XS Rating Curve= 0 ,0
Exp/Cntr(USF)=0,0
Exp/Cntr=0.3,0.1

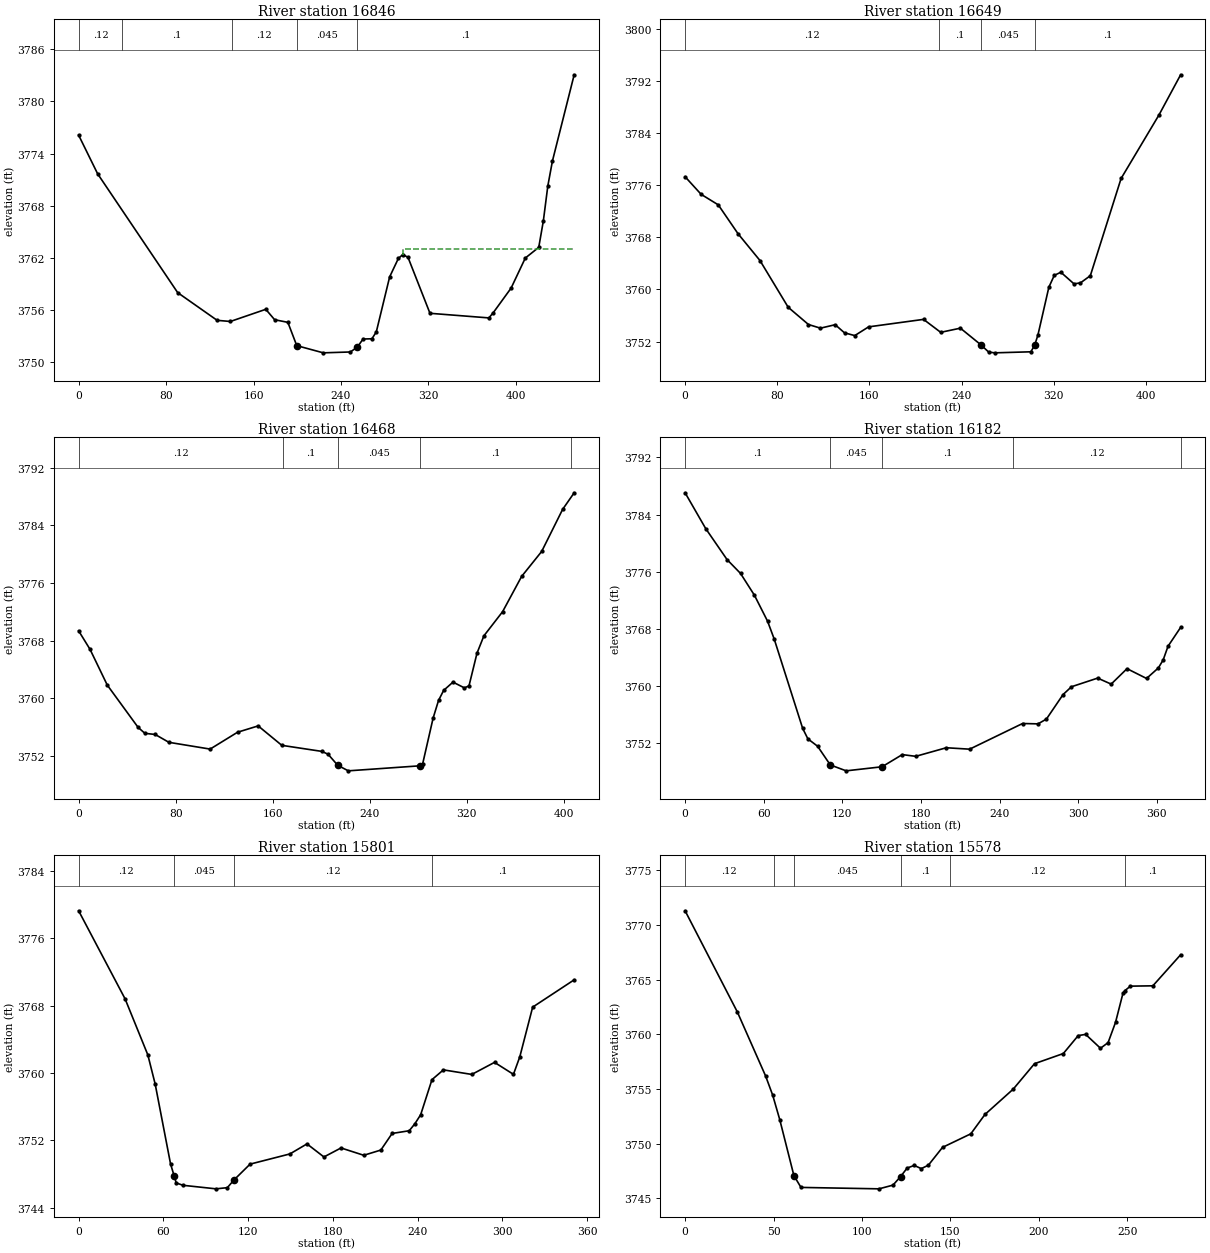
Type RM Length L Ch R = 1 ,16846   ,178.4,197.2,215.3
XS GIS Cut Line= 3
2268490.19648273546306.3952286412268535.45029276546009.013048418
2268575.85548029545861.938165807
#Sta/Elev= 30
       0 3776.12    17.4 3771.67    90.6    3758   126.7 3754.81   138.8 3754.68
   171.2 3756.08   179.3 3754.88   191.4 3754.58   199.5 3751.91   199.5  3751.9
   223.8 3751.07   248.6 3751.17     2553751.741   260.2 3752.66   268.3 3752.69
   272.3 3753.48   284.5 3759.81   292.5 3761.94   296.6 3762.38   301.3 3762.06
   321.4 3755.62   375.3 3755.09   379.4 3755.71   395.6 3758.52   408.6 3761.98
   420.9 3763.21   425.1 3766.25   429.2 3770.28   433.4 3773.14   453.3 3783.07
#Mann= 5 ,-1,0
       0     .12       0      40      .1       0     140     .12       0
   199.5    .045       0     255      .1       0
#XS Ineff= 2 , 0
                          296.45         3763.01
Permanent Ineff=
       F       F
Bank Sta=199.5,255
XS Rating Curve= 0 ,0
Exp/Cntr(USF)=0,0
Exp/Cntr=0.3,0.1

Type RM Length L Ch R = 1 ,16649   ,165.4,181.3,201.4
XS GIS Cut Line= 2
2268530.67130881546339.2308940582268807.04279152 546009.52456381
#Sta/Elev= 30
       0 3777.32    13.9 3774.62    28.8    3773    45.9 3768.58      65 3764.45
    89.5 3757.27   107.1 3754.62   117.5 3754.06   130.3 3754.59   138.4 3753.34
   147.3 3752.92   159.3 3754.26     207 3755.41   221.9 3753.42     239 3754.06
   256.73751.515   263.6 3750.38   268.9 3750.27   300.2 3750.43   303.5 3751.46
   306.3    3753   315.8 3760.35   320.5 3762.17   326.2 3762.65   337.6 3760.87
   343.2 3761.01   351.8 3762.12   378.5 3777.05   411.4 3786.81   430.2 3792.98
#Mann= 4 ,-1,0
       0     .12       0     220      .1       0   256.7    .045       0
   303.5      .1       0
Bank Sta=256.7,303.5
XS Rating Curve= 0 ,0
Exp/Cntr(USF)=0,0
Exp/Cntr=0.3,0.1

Type RM Length L Ch R = 1 ,16468   ,288.5,285.4,282
XS GIS Cut Line= 4
2268627.57412033546409.8325087192268732.62760791 546304.77902114
2268876.47007552546241.7469285932268950.81562058546170.633798539
#Sta/Elev= 30
       0 3769.36     9.4 3766.79    23.6 3761.83      49 3755.96    54.6 3755.13
    63.1 3754.97    74.4 3753.88   108.4 3752.94     131 3755.28     148 3756.16
   167.5 3753.46   200.5 3752.62   205.6 3752.23   213.6 3750.69   222.3 3749.92
   281.5 3750.62   283.5 3750.82   292.2 3757.23   296.7  3759.7   300.9 3761.09
   308.6 3762.24     318 3761.44   321.8 3761.72   328.4 3766.26   334.1 3768.67
   349.5 3772.02   365.2 3776.92   381.7 3780.38     399 3786.23   408.5 3788.53
#Mann= 5 ,-1,0
       0     .12       0  168.57      .1       0   213.6    .045       0
   281.5      .1       0  405.61     .12       0
Bank Sta=213.6,281.5
XS Rating Curve= 0 ,0
Exp/Cntr(USF)=0,0
Exp/Cntr=0.3,0.1

Type RM Length L Ch R = 1 ,16182   ,403.8,381.2,356.1
XS GIS Cut Line= 2
2268755.25451293546626.4043138822269049.40427815546388.821811203
#Sta/Elev= 30
       0 3787.04    15.7 3782.04      32  3777.7    42.3 3775.76    52.9 3772.71
    62.9 3769.09      68 3766.58    89.7 3754.09    93.7 3752.62   101.1 3751.59
   110.83748.974   122.9 3748.15   150.3 3748.72   165.7 3750.42     176 3750.18
   199.3 3751.38   217.1 3751.18   257.5 3754.77   269.3 3754.72   275.7 3755.39
   288.4 3758.82   294.8 3759.91   314.8 3761.12   325.1 3760.28   337.2 3762.44
   352.1 3761.07   361.1 3762.54   364.8 3763.67   368.5 3765.58   378.1 3768.21
#Mann= 5 ,-1,0
       0      .1       0   110.8    .045       0   150.3      .1       0
     250     .12       0  378.11      .1       0
Bank Sta=110.8,150.3
XS Rating Curve= 0 ,0
Exp/Cntr(USF)=0,0
Exp/Cntr=0.3,0.1

Type RM Length L Ch R = 1 ,15801   ,227.3,223.1,219.8
XS GIS Cut Line= 3
2269167.38742574546813.8843840232269199.71157576546519.734618802
2269225.57089578546471.248393765
#Sta/Elev= 30
       0 3779.24    32.9 3768.79      49 3762.15    54.2 3758.69    65.1 3749.21
    67.7 3747.76    69.1 3746.96    73.9 3746.68    97.3 3746.26   105.3  3746.4
   110.1 3747.33   121.4 3749.19   149.6  3750.4   161.7 3751.59   173.7 3750.04
   185.8 3751.11   201.9 3750.24     214 3750.86     222 3752.83   234.1 3753.15
   238.1 3753.98   242.2 3755.05   250.2 3759.21   258.3 3760.37   278.4 3759.83
   294.5 3761.26   307.9 3759.84   312.4 3761.92   321.5 3767.81   350.9 3771.05
#Mann= 4 ,-1,0
       0     .12       0    67.7    .045       0   110.1     .12       0
     250      .1       0
Bank Sta=67.7,110.1
XS Rating Curve= 0 ,0
Exp/Cntr(USF)=0,0
Exp/Cntr=0.3,0.1

Type RM Length L Ch R = 1 ,15578   ,225.8,241.9,256
XS GIS Cut Line= 3
2269401.73751342 546810.651969022269398.50509841546602.161201364
2269421.13200343546534.280486313
#Sta/Elev= 30
       0  3771.3    29.5 3762.06    45.5  3756.2    49.5 3754.45    53.5 3752.21
    61.5 3747.09    65.5 3746.01   109.6 3745.88   117.5 3746.22   121.8    3747
   125.5 3747.78   129.5 3748.02   133.5 3747.73   137.5 3748.04   145.5 3749.67
   161.5 3750.91   169.5 3752.68   185.5    3755   197.5 3757.32   213.8 3758.25
   222.2 3759.89   226.4    3760   234.8 3758.73   239.1 3759.25   243.3  3761.1
   247.5 3763.76   248.6    3764   251.7 3764.41   264.4 3764.44   280.1 3767.28
#Mann= 6 ,-1,0
       0     .12       0      50      .1       0    61.5    .045       0
   121.8      .1       0     150     .12       0  248.52      .1       0
Bank Sta=61.5,121.8
XS Rating Curve= 0 ,0
Exp/Cntr(USF)=0,0
Exp/Cntr=0.3,0.1

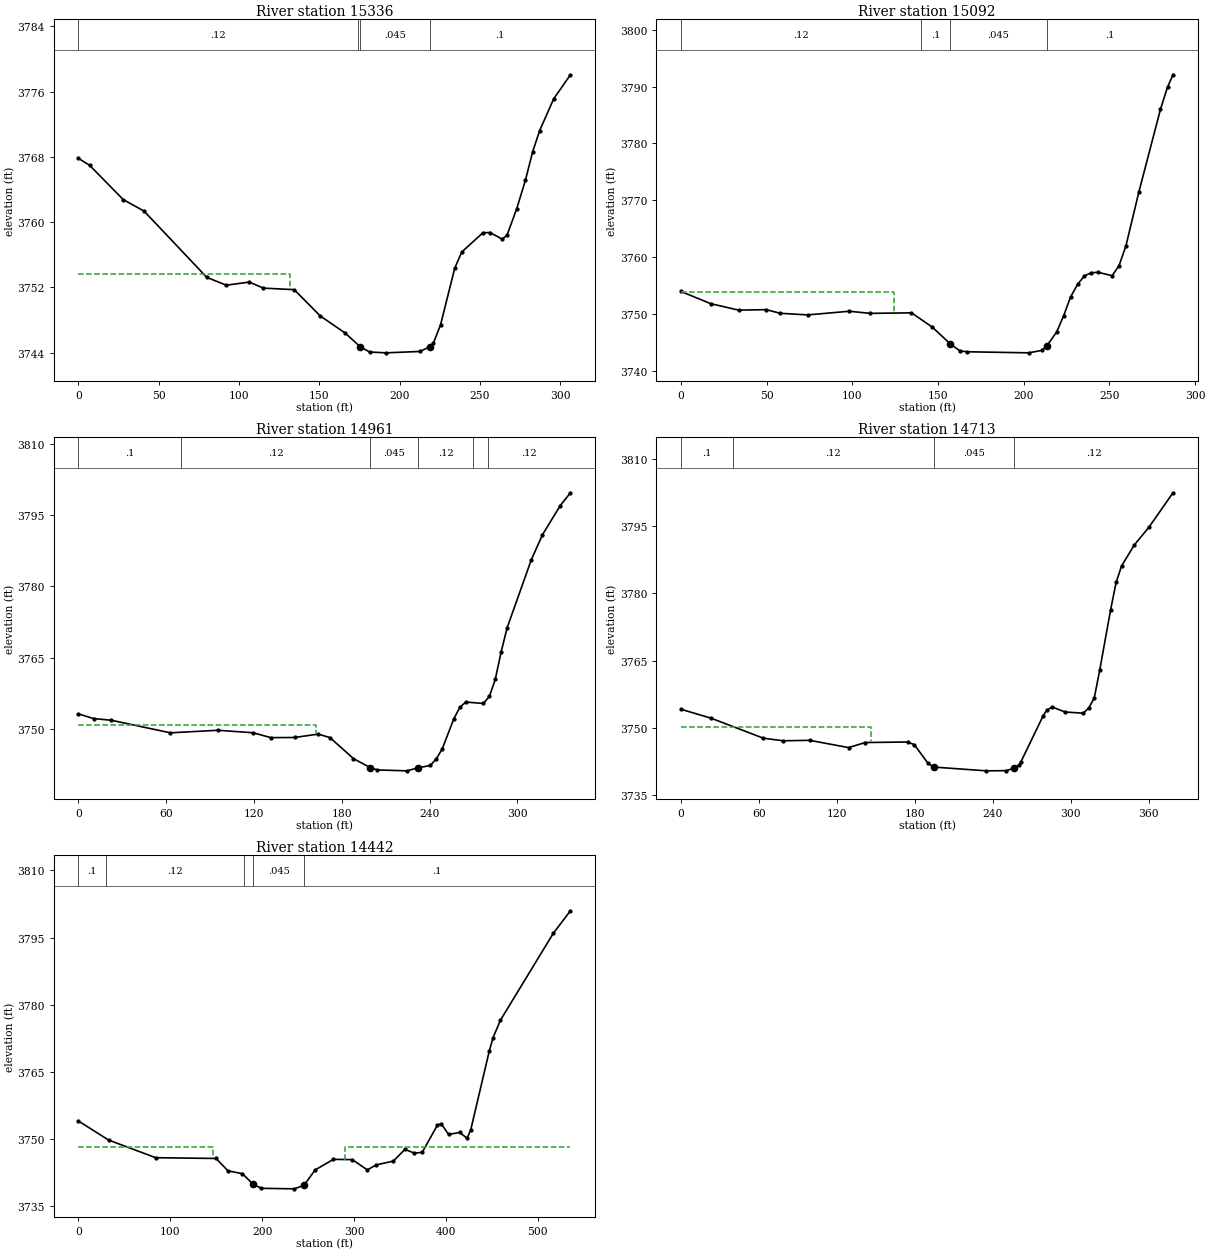
Type RM Length L Ch R = 1 ,15336   ,211.9,243.9,281.6
XS GIS Cut Line= 3
2269502.60039578546864.6208207822269597.96382084546823.463974179
2269683.28899063546639.763902757
#Sta/Elev= 30
       0 3767.82     6.9 3766.97    27.9 3762.76    40.9 3761.34    79.9 3753.22
    92.1 3752.26   106.4 3752.64   115.2  3751.9   134.4 3751.71   150.5  3748.5
   166.1 3746.39   175.6 3744.68   181.4 3744.06   191.6 3743.96   212.7 3744.13
   218.7  3744.7   221.1 3745.18   225.5 3747.39   234.3 3754.32   238.7 3756.33
   251.9 3758.69   256.3 3758.72   263.9 3757.91   266.9 3758.39   272.9 3761.61
   278.4 3765.15   282.8 3768.58   287.2 3771.21     296 3775.13   306.4 3778.07
#Mann= 4 ,-1,0
       0     .12       0  173.87      .1       0   175.6    .045       0
   218.7      .1       0
#XS Ineff= 2 , 0
          131.52  3753.6
Permanent Ineff=
       F       F
Bank Sta=175.6,218.7
XS Rating Curve= 0 ,0
Exp/Cntr(USF)=0,0
Exp/Cntr=0.3,0.1

Type RM Length L Ch R = 1 ,15092   ,124.9,130.9,142.1
XS GIS Cut Line= 2
2269598.91482856546944.7971916212269883.36734878546906.008211592
#Sta/Elev= 30
       0 3753.92    17.4 3751.77    33.6 3750.64    49.7 3750.72      58 3750.08
    73.9  3749.8    98.2 3750.44   110.3 3750.07   134.5 3750.16   146.6 3747.66
   157.1  3744.7   162.8 3743.46   166.8 3743.31   202.9 3743.12   210.4 3743.54
   213.33744.274   219.3 3746.84   223.3 3749.66   227.3 3752.94   231.4 3755.16
   235.4 3756.66   239.5 3757.23   243.5 3757.29   251.6  3756.7   255.6 3758.47
   259.6 3761.91   267.2 3771.46   279.8 3786.01   283.9  3789.9   287.1 3792.07
#Mann= 4 ,-1,0
       0     .12       0     140      .1       0   157.1    .045       0
   213.3      .1       0
#XS Ineff= 2 , 0
          124.22 3753.78
Permanent Ineff=
       F       F
Bank Sta=157.1,213.3
XS Rating Curve= 0 ,0
Exp/Cntr(USF)=0,0
Exp/Cntr=0.3,0.1

Type RM Length L Ch R = 1 ,14961   ,231.1,248.1,265.8
XS GIS Cut Line= 2
2269569.85670609547023.2252540322269903.12678102547068.397402743
#Sta/Elev= 30
       0 3753.18    10.4 3752.21    22.5 3751.85    62.9 3749.21    95.2 3749.75
   119.4 3749.23   131.5  3748.2   147.7 3748.23   163.8 3748.94   171.9 3748.22
     188 3743.79   199.3 3741.92   204.2 3741.41   224.4 3741.22   232.4 3741.87
   240.5 3742.35   244.5 3743.69   248.6 3745.79   256.6 3752.17   260.7 3754.56
   264.7 3755.68   276.8 3755.39   280.9 3756.88   284.9 3760.43   288.9 3766.18
     293 3771.27   309.5 3785.56   317.2 3790.86   329.3 3796.97   336.3 3799.68
#Mann= 6 ,-1,0
       0      .1       0      70     .12       0   199.3    .045       0
   232.4     .12       0     270      .1       0     280     .12       0
#XS Ineff= 2 , 0
           162.7 3750.88
Permanent Ineff=
       F       F
Bank Sta=199.3,232.4
XS Rating Curve= 0 ,0
Exp/Cntr(USF)=0,0
Exp/Cntr=0.3,0.1

Type RM Length L Ch R = 1 ,14713   ,267.8,271.1,271.1
XS GIS Cut Line= 3
  2269510.023416547140.3582992682269750.83833368547326.222161908
2269821.95146373547348.849066925
#Sta/Elev= 30
       0 3754.14    22.9 3752.18    63.4 3747.69    78.5 3747.11    99.1 3747.21
     129 3745.59   141.9 3746.72   174.5 3746.84   179.6 3746.24   190.3 3742.05
   194.7 3741.24   235.1  3740.4   250.3 3740.44   256.7 3741.01   260.4 3741.73
   261.6 3742.35   278.7 3752.61   281.6 3753.95   285.7 3754.64   295.8 3753.53
   309.8 3753.27     314 3754.46   318.2 3756.68   322.4 3762.91   330.8 3776.41
     335 3782.45   339.2 3786.13     349 3790.82   360.2 3794.75   378.8 3802.47
#Mann= 4 ,-1,0
       0      .1       0      40     .12       0   194.7    .045       0
   256.7     .12       0
#XS Ineff= 2 , 0
          146.14 3750.26
Permanent Ineff=
       F       F
Bank Sta=194.7,256.7
XS Rating Curve= 0 ,0
Exp/Cntr(USF)=0,0
Exp/Cntr=0.3,0.1

Type RM Length L Ch R = 1 ,14442   ,117.3,113.9,112
BEGIN DESCRIPTION:
Structure XS 4
END DESCRIPTION:
XS GIS Cut Line= 3
2269342.99213701547339.430295005 2269641.1283185547587.375200149
2269787.68684542 547606.44788516
#Sta/Elev= 30
       0 3753.99    32.8 3749.73    84.1 3745.78   149.8 3745.61   162.8 3742.84
   178.4 3742.22   190.4 3739.81   199.2 3738.94     235 3738.82   245.53739.611
   257.7 3743.05   277.6 3745.41   298.1 3745.35   314.5 3743.06   324.1 3744.17
   342.9 3745.03   355.3 3747.64   365.7 3746.81   374.2 3746.97   390.8 3753.06
   394.9 3753.39   402.9 3750.98     415 3751.42   423.1 3750.13   427.1 3752.05
   447.3 3769.68   451.3 3772.59   459.4 3776.53     517 3795.97   535.6 3800.99
#Mann= 5 ,-1,0
       0      .1       0      30     .12       0     180      .1       0
   190.4    .045       0   245.5      .1       0
#XS Ineff= 2 , 0
          146.97 3748.25  290.19         3748.25
Permanent Ineff=
       F       F
Bank Sta=190.4,245.5
XS Rating Curve= 0 ,0
Exp/Cntr(USF)=0,0
Exp/Cntr=0.5,0.3