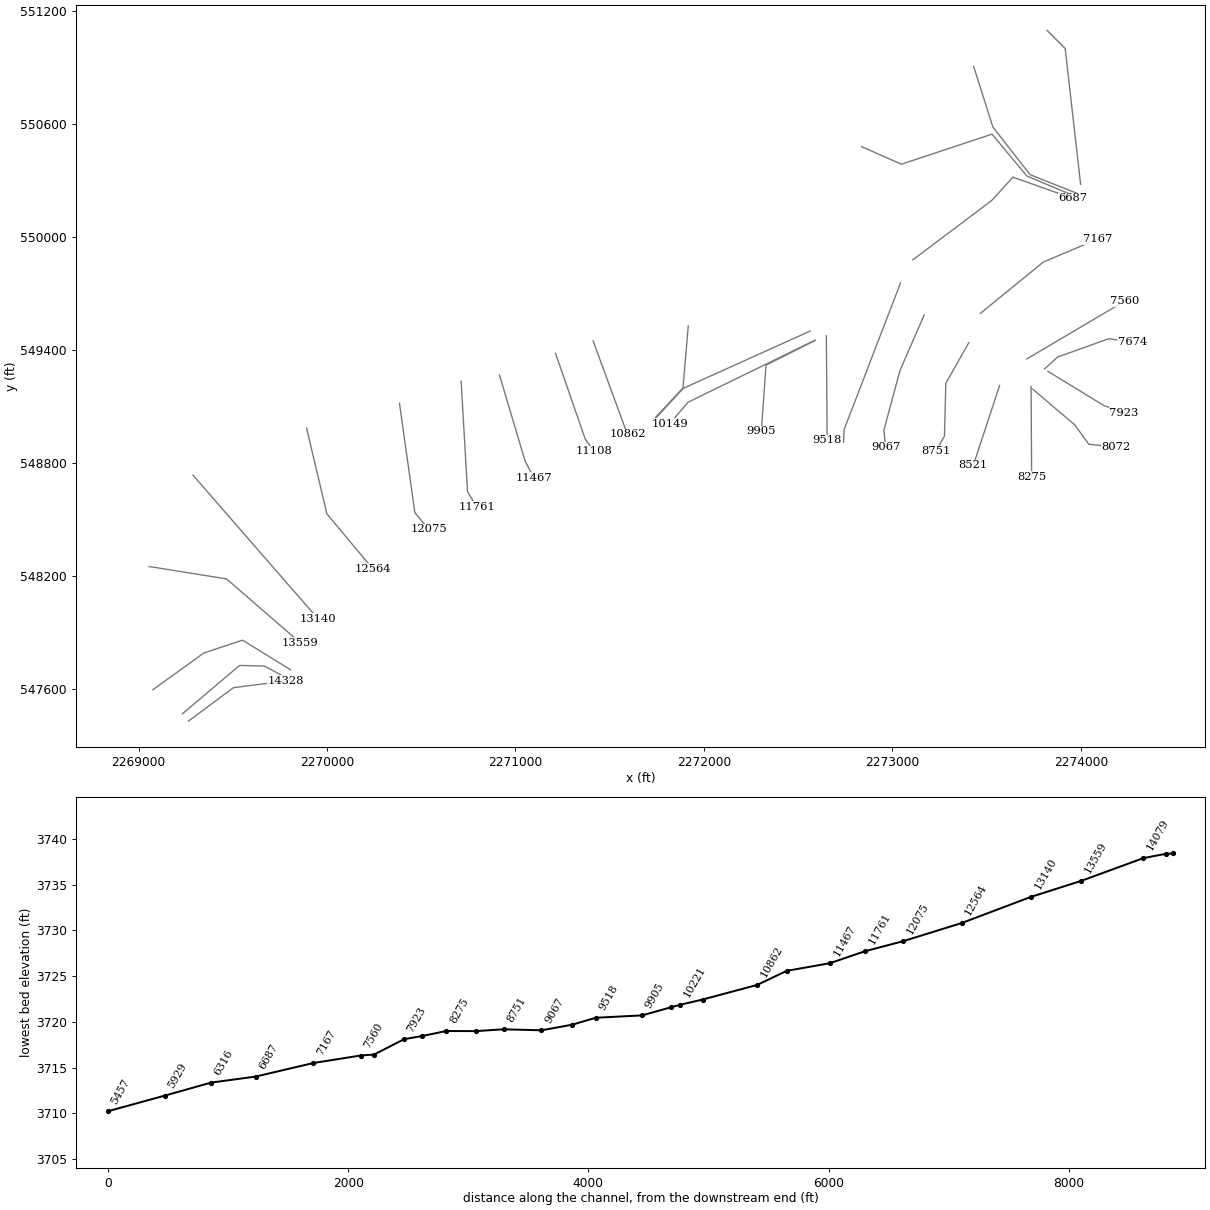
HEC-RAS study SHVRSFK.prj: SHVRSFK

--- SHVRSFK.g01 (geometry) --- (continued)

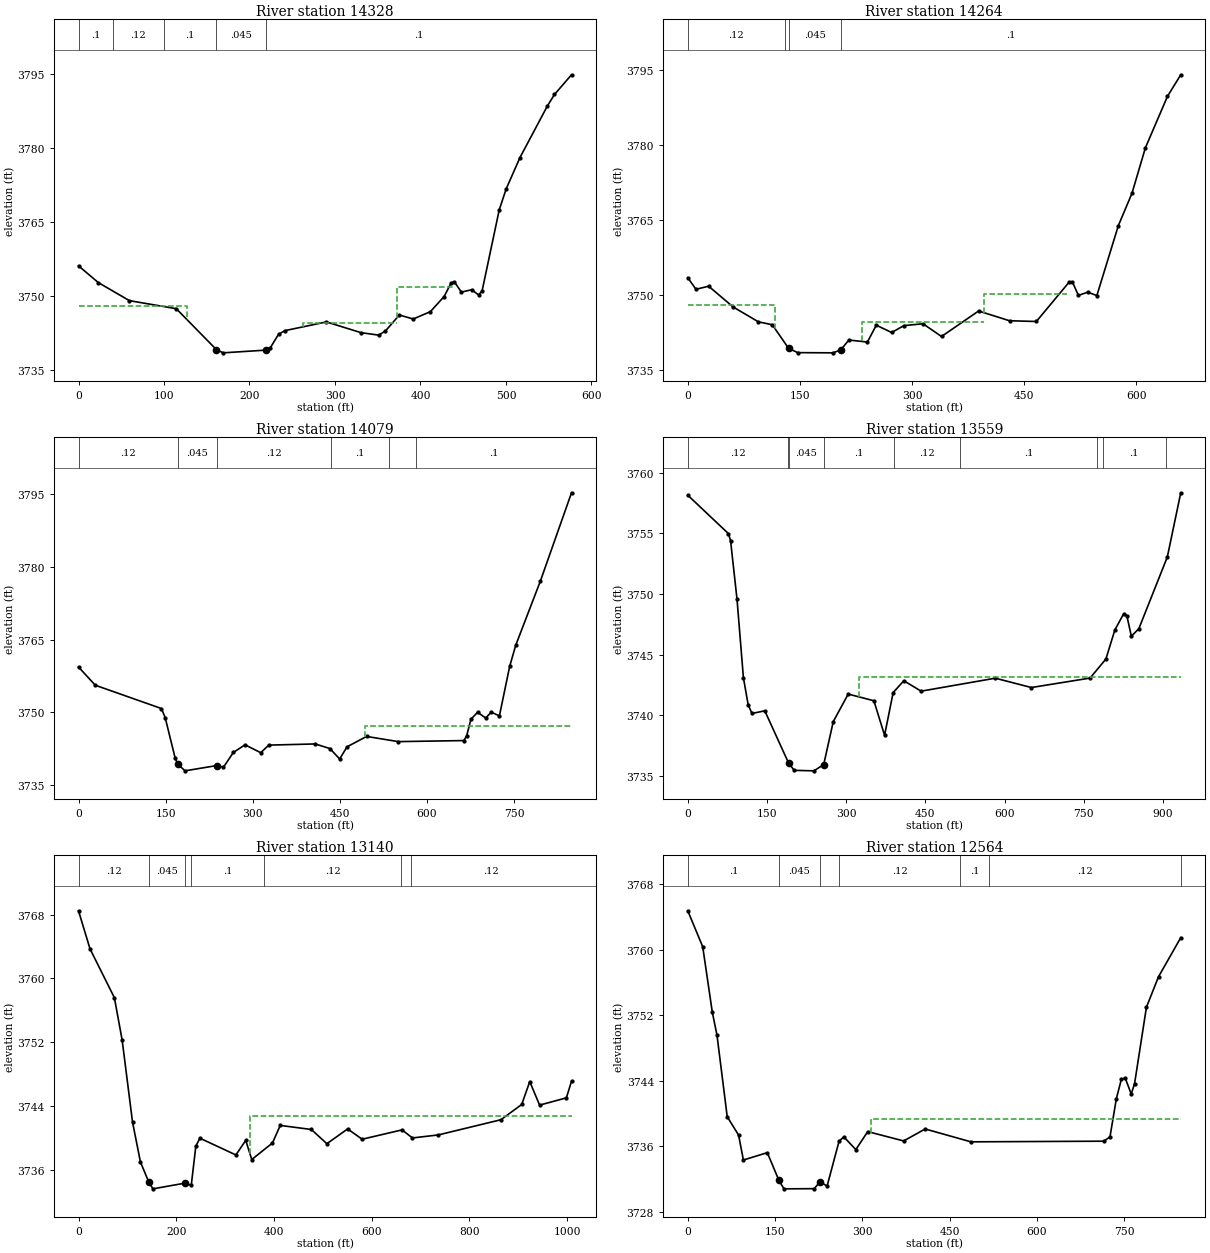
Type RM Length L Ch R = 1 ,14328   ,64.8,64.4,66.5
BEGIN DESCRIPTION:
Structure XS 3
END DESCRIPTION:
XS GIS Cut Line= 3
2269264.35987581547431.2756494872269503.55858599 547609.05847462
 2269779.9300687547644.615039647
#Sta/Elev= 30
       0 3756.06    23.3 3752.65    59.6    3749   114.4 3747.37   161.3 3739.07
   169.2 3738.42   219.1 3738.97   224.5 3739.48     234 3742.18   241.4 3742.92
     290 3744.69   330.3 3742.52   351.1 3742.01   359.1 3742.86   375.3 3746.09
   391.6 3745.28   411.6 3746.77   427.7 3749.84   435.8 3752.56   439.8  3752.8
   447.9 3750.73     460 3751.22     468 3750.16   472.1 3750.97   492.2 3767.44
   500.3 3771.67   516.4 3778.01   548.5 3788.48   556.8 3790.81   576.7  3794.8
#Mann= 5 ,-1,0
       0      .1       0      40     .12       0     100      .1       0
   161.3    .045       0   219.1      .1       0
#XS Ineff= 4 ,-1
       0     127    3748     263  372.03  3744.5  372.03   440.5 3751.68
   440.5   576.7  3744.5
Permanent Ineff=
       F       F       F       F
Bank Sta=161.3,219.1
XS Rating Curve= 0 ,0
Exp/Cntr(USF)=0,0
Exp/Cntr=0.5,0.3

Type RM Length L Ch R = 1 ,14264   ,187.2,185,180.6
BEGIN DESCRIPTION:
Structure XS 2
END DESCRIPTION:
XS GIS Cut Line= 4
2269232.03572579547470.0646295162269535.88273602547727.041622209
2269668.41175112547723.809207207 2269781.5462762547662.393322161
#Sta/Elev= 30
       0  3753.4      11 3751.08    27.9  3751.7    60.6 3747.55    94.5 3744.57
     113 3743.99   134.9 3739.26   147.1 3738.41     194 3738.37   204.43738.926
   215.4 3740.93   240.2 3740.53   252.1  3743.9   272.6 3742.44     289 3743.81
   314.5 3744.19   339.3 3741.64   388.9 3746.74   430.2 3744.79   466.1 3744.64
   510.3 3752.58   514.3 3752.56   522.3 3749.86   534.8  3750.5     547 3749.83
   575.8 3763.84     594  3770.3   611.9 3779.38   641.4 3789.67   659.2 3793.99
#Mann= 4 ,-1,0
       0     .12       0     130      .1       0   134.9    .045       0
   204.4      .1       0
#XS Ineff= 4 ,-1
       0     117    3748     233  395.55  3744.5  395.55  506.61  3750.2
  506.61   659.2  3744.5
Permanent Ineff=
       F       F       F       F
Bank Sta=134.9,204.4
XS Rating Curve= 0 ,0
Exp/Cntr(USF)=0,0
Exp/Cntr=0.5,0.3

Type RM Length L Ch R = 1 ,14079   ,546.7,519.9,477.7
BEGIN DESCRIPTION:
Structure XS 1
END DESCRIPTION:
XS GIS Cut Line= 4
2269075.26359817547597.7450221122269346.78645837547793.306129759
2269552.04481103 547861.186844812269805.78938872547704.414717192
#Sta/Elev= 30
       0 3759.34    28.9 3755.58   142.8 3750.77   149.3  3748.9   166.5 3740.52
     1713739.289   183.5 3737.91   238.1    3739   249.6 3738.65   266.7 3741.71
   286.8 3743.28   313.9 3741.65   327.6 3743.22   407.7 3743.46     433 3742.51
   449.8 3740.35   462.5 3742.87   496.2 3745.01   550.8 3743.94   663.8 3744.16
   668.5 3745.13   675.9 3748.55   687.3    3750   701.4 3748.81   710.8 3750.03
   724.9 3749.25   742.7 3759.52   753.1 3763.85   795.5 3777.08   849.1  3795.3
#Mann= 6 ,-1,0
       0     .12       0     171    .045       0   238.1     .12       0
  434.62      .1       0  534.62     .12       0  580.81      .1       0
#XS Ineff= 2 , 0
                          494.08         3747.24
Permanent Ineff=
       F       F
Bank Sta=171,238.1
XS Rating Curve= 0 ,0
Exp/Cntr(USF)=0,0
Exp/Cntr=0.3,0.1

Type RM Length L Ch R = 1 ,13559   ,441.1,418.5,376.4
XS GIS Cut Line= 3
2269056.06957055548252.0660637762269466.62880979548186.376585496
2269858.02861787 547846.98094772
#Sta/Elev= 30
       0 3758.14    77.1 3754.97    81.1 3754.38    93.3 3749.56   105.4 3743.09
   114.4 3740.86   121.6 3740.14   145.9 3740.36   191.2 3736.03   201.7 3735.45
   239.1 3735.41   257.5 3735.93   275.6 3739.47   303.9 3741.74   352.5 3741.19
   372.8 3738.34     389 3741.86   409.2 3742.84     442 3741.98   582.5 3743.05
   650.8 3742.28     762 3743.06     792 3744.63     809 3747.03   825.5 3748.35
   831.7  3748.2   840.2 3746.51   854.4 3747.13   908.3 3753.04   933.8 3758.34
#Mann= 9 ,-1,0
       0     .12       0     190      .1       0   191.2    .045       0
   257.5      .1       0     390     .12       0  515.78      .1       0
  775.78     .12       0  785.78      .1       0  905.78     .12       0
#XS Ineff= 2 , 0
                          324.29         3743.12
Permanent Ineff=
       F       F
Bank Sta=191.2,257.5
XS Rating Curve= 0 ,0
Exp/Cntr(USF)=0,0
Exp/Cntr=0.3,0.1

Type RM Length L Ch R = 1 ,13140   ,593.4,576.4,547.9
XS GIS Cut Line= 2
2269288.71980612548736.525966086 2269951.0887121547975.622842683
#Sta/Elev= 30
       0 3768.47    23.5 3763.71    73.4 3757.59    89.3 3752.29   110.5 3742.03
   126.7 3737.03   143.73734.522   152.3 3733.66   218.5 3734.38   230.7 3734.09
   240.1 3739.01   248.4    3740   322.1  3737.9   342.2 3739.73   354.5 3737.33
   396.9  3739.4   412.8  3741.6   476.4 3741.09   508.2 3739.31   550.7 3741.16
   580.4 3739.87     662 3741.04   683.3 3740.03   736.3 3740.41   864.3 3742.31
   906.9 3744.22   923.4 3747.09   943.5 3744.14   998.3 3745.05  1008.8 3747.13
#Mann= 7 ,-1,0
       0     .12       0   143.7    .045       0   218.5     .12       0
     230      .1       0     380     .12       0     660      .1       0
     680     .12       0
#XS Ineff= 2 , 0
                          351.16         3742.73
Permanent Ineff=
       F       F
Bank Sta=143.7,218.5
XS Rating Curve= 0 ,0
Exp/Cntr(USF)=0,0
Exp/Cntr=0.3,0.1

Type RM Length L Ch R = 1 ,12564   ,493.4,489.3,485.2
XS GIS Cut Line= 3
2269891.53298886548986.156931793 2269999.2801556 548531.22444997
2270242.70893974548239.908036171
#Sta/Elev= 30
       0 3764.76    25.7 3760.37    42.1 3752.41    50.3 3749.53    67.8 3739.61
    87.3 3737.37    95.6 3734.32   136.7 3735.22   156.7 3731.82   165.4  3730.8
   217.4 3730.82   227.3 3731.68   239.4 3731.13     260 3736.62   268.2 3737.15
   288.8 3735.59   309.3 3737.79     371 3736.65     408 3738.11   486.6 3736.54
   715.2 3736.62   725.6 3737.16   736.5 3741.81   745.1 3744.17   751.7 3744.34
   762.1 3742.38   767.8 3743.64   788.2 3752.98     809 3756.71   847.2 3761.48
#Mann= 7 ,-1,0
       0      .1       0   156.7    .045       0   227.3      .1       0
     260     .12       0  467.52      .1       0  517.52     .12       0
  847.15      .1       0
#XS Ineff= 2 , 0
                          315.24         3739.36
Permanent Ineff=
       F       F
Bank Sta=156.7,227.3
XS Rating Curve= 0 ,0
Exp/Cntr(USF)=0,0
Exp/Cntr=0.3,0.1

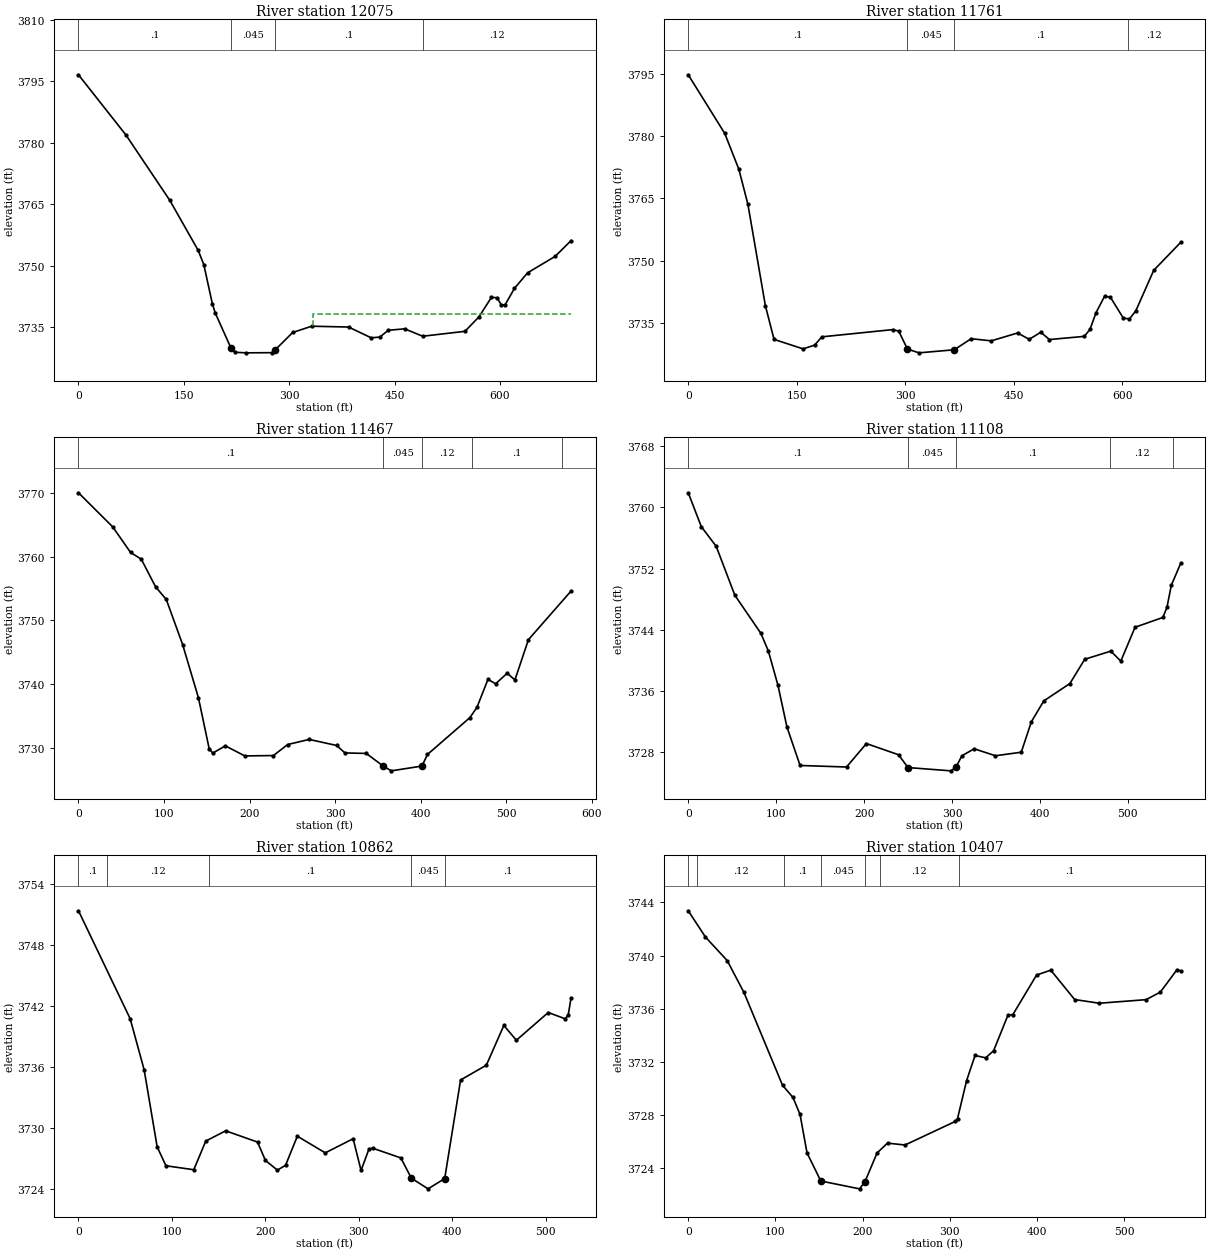
Type RM Length L Ch R = 1 ,12075   ,316.9,313.2,310
XS GIS Cut Line= 3
2270384.37651083549117.8479133742270466.18454484548537.210403678
2270540.01130725548449.416415958
#Sta/Elev= 30
       0 3796.58    67.7 3781.87   129.9    3766   170.4 3753.78   178.4 3750.31
   190.5  3740.8   194.6 3738.55   217.3 3729.88   222.8 3728.94     239 3728.81
   275.4 3728.85   280.1 3729.55   304.9 3733.77   331.9  3735.3   384.4  3735.1
   416.7 3732.47   428.9 3732.65     441 3734.31   464.2 3734.66     490 3732.86
     550 3734.05     570 3737.56   587.8 3742.34   595.7 3742.23     602 3740.48
   607.3 3740.53   620.5 3744.51   639.2  3748.3   678.7 3752.35   701.1 3756.16
#Mann= 4 ,-1,0
       0      .1       0   217.3    .045       0   280.1      .1       0
     490     .12       0
#XS Ineff= 2 , 0
                          333.47         3738.37
Permanent Ineff=
       F       F
Bank Sta=217.3,280.1
XS Rating Curve= 0 ,0
Exp/Cntr(USF)=0,0
Exp/Cntr=0.3,0.1

Type RM Length L Ch R = 1 ,11761   ,287.7,294.3,301.2
XS GIS Cut Line= 3
2270711.60864688549235.5716696352270745.52905123548648.948206231
2270793.41668089548569.135490122
#Sta/Elev= 30
       0 3794.83    50.5 3780.67      70 3772.01    82.5 3763.54   106.6 3739.12
   118.6 3730.97   158.7 3728.69   174.7 3729.59   184.6 3731.59   282.9 3733.34
   290.9 3732.97   302.9 3728.64   318.9 3727.73   367.7 3728.47     391 3731.14
   418.7 3730.62   455.2 3732.52   471.2 3730.99   487.2 3732.69   499.2 3730.94
   547.3  3731.7   555.3 3733.41   563.4 3737.35   575.4 3741.39   583.4 3741.15
   601.3 3736.11   609.8 3735.92   618.5 3737.85   643.3 3747.64   680.7 3754.41
#Mann= 4 ,-1,0
       0      .1       0   302.9    .045       0   367.7      .1       0
   607.6     .12       0
Bank Sta=302.9,367.7
XS Rating Curve= 0 ,0
Exp/Cntr(USF)=0,0
Exp/Cntr=0.3,0.1

Type RM Length L Ch R = 1 ,11467   ,357.1,358.6,356.3
XS GIS Cut Line= 3
2270915.13107296549267.4967560792271050.81269035548812.564274255
2271096.70500211548722.774968632
#Sta/Elev= 30
       0 3770.04      40 3764.69    60.9 3760.67    73.4 3759.62    90.1 3755.28
   102.6  3753.3   121.7 3746.23   140.2 3737.86   152.7  3729.9   156.9 3729.19
   171.6 3730.33   194.4 3728.75   227.8 3728.81   244.5 3730.54   269.6 3731.34
   301.7 3730.39   311.4 3729.22   336.3 3729.14   356.4 3727.13   365.6 3726.41
   401.4 3727.16   407.8 3728.98   457.4 3734.76   465.7 3736.38   478.5 3740.76
   487.5 3740.07     501 3741.73     510 3740.67   525.8 3746.99   575.6 3754.62
#Mann= 5 ,-1,0
       0      .1       0   356.4    .045       0   401.4     .12       0
     460      .1       0  564.73     .12       0
Bank Sta=356.4,401.4
XS Rating Curve= 0 ,0
Exp/Cntr(USF)=0,0
Exp/Cntr=0.3,0.1

Type RM Length L Ch R = 1 ,11108   ,248.9,246,240
XS GIS Cut Line= 3
2271212.43344047549383.2251944382271370.06355478548928.292712614
2271415.95586655548864.442539727
#Sta/Elev= 30
       0 3761.89    14.9 3757.46    31.8  3754.9      53 3748.51    82.6 3743.54
    91.1 3741.23     102 3736.77   112.2 3731.32   127.2 3726.28     180 3726.08
   202.6 3729.14   239.2 3727.68   249.8 3726.01   298.5 3725.58   304.43726.046
   311.2 3727.55   325.2 3728.46   349.3 3727.55   378.7 3728.01   390.2 3731.99
   404.3 3734.71     434 3736.98   450.9 3740.15   480.5 3741.21   491.9 3739.91
   508.1 3744.33   539.7 3745.61   544.4 3746.93   549.3  3749.8   560.1 3752.71
#Mann= 5 ,-1,0
       0      .1       0   249.8    .045       0   304.4      .1       0
     480     .12       0  551.47      .1       0
Bank Sta=249.8,304.4
XS Rating Curve= 0 ,0
Exp/Cntr(USF)=0,0
Exp/Cntr=0.3,0.1

Type RM Length L Ch R = 1 ,10862   ,476.2,455,440.8
XS GIS Cut Line= 2
2271411.96523074549449.0706852282271593.53915989 548954.23184535
#Sta/Elev= 30
       0  3751.4    55.3 3740.78    70.3 3735.74    84.2 3728.17    93.6 3726.31
   123.4 3725.92   136.2 3728.74   157.5 3729.75   191.6 3728.64   200.1 3726.83
   212.9 3725.88   221.6 3726.36   234.2 3729.22   264.1 3727.58   293.9 3728.97
   302.4 3725.85   310.9 3727.97   315.2 3728.03     345 3727.08   356.2 3725.09
   374.1 3724.04   391.9 3725.05   408.9 3734.75   436.5 3736.21   455.2 3740.12
   468.6 3738.66   502.7 3741.39   520.6 3740.78     524  3741.1   527.1 3742.82
#Mann= 5 ,-1,0
       0      .1       0      30     .12       0     140      .1       0
   356.2    .045       0   391.9      .1       0
Bank Sta=356.2,391.9
XS Rating Curve= 0 ,0
Exp/Cntr(USF)=0,0
Exp/Cntr=0.3,0.1

Type RM Length L Ch R = 1 ,10407   ,233.2,186.6,149.2
BEGIN DESCRIPTION:
Structure XS 4
END DESCRIPTION:
XS GIS Cut Line= 3
2271916.78066013549528.8834013372271888.84620949549199.655947386
2271729.22077727549028.058607751
#Sta/Elev= 30
       0 3743.37    19.8 3741.39    44.7 3739.62    63.9 3737.22   108.1 3730.24
   120.1 3729.32   128.2 3728.04   136.2 3725.15     152 3723.03   196.4 3722.44
   202.53722.949   216.5 3725.14   228.5 3725.88   248.6 3725.74   306.1 3727.51
   308.8 3727.73   319.2 3730.59   328.9 3732.48   341.1  3732.3   350.2 3732.84
   366.6 3735.51   372.3 3735.56   399.4 3738.53   415.7  3738.9   443.1 3736.69
   471.3 3736.41     525 3736.68   541.4 3737.25   560.4 3738.93   564.8 3738.84
#Mann= 7 ,-1,0
       0      .1       0      10     .12       0     110      .1       0
     152    .045       0   202.5      .1       0     220     .12       0
     310      .1       0
Bank Sta=152,202.5
XS Rating Curve= 0 ,0
Exp/Cntr(USF)=0,0
Exp/Cntr=0.5,0.3

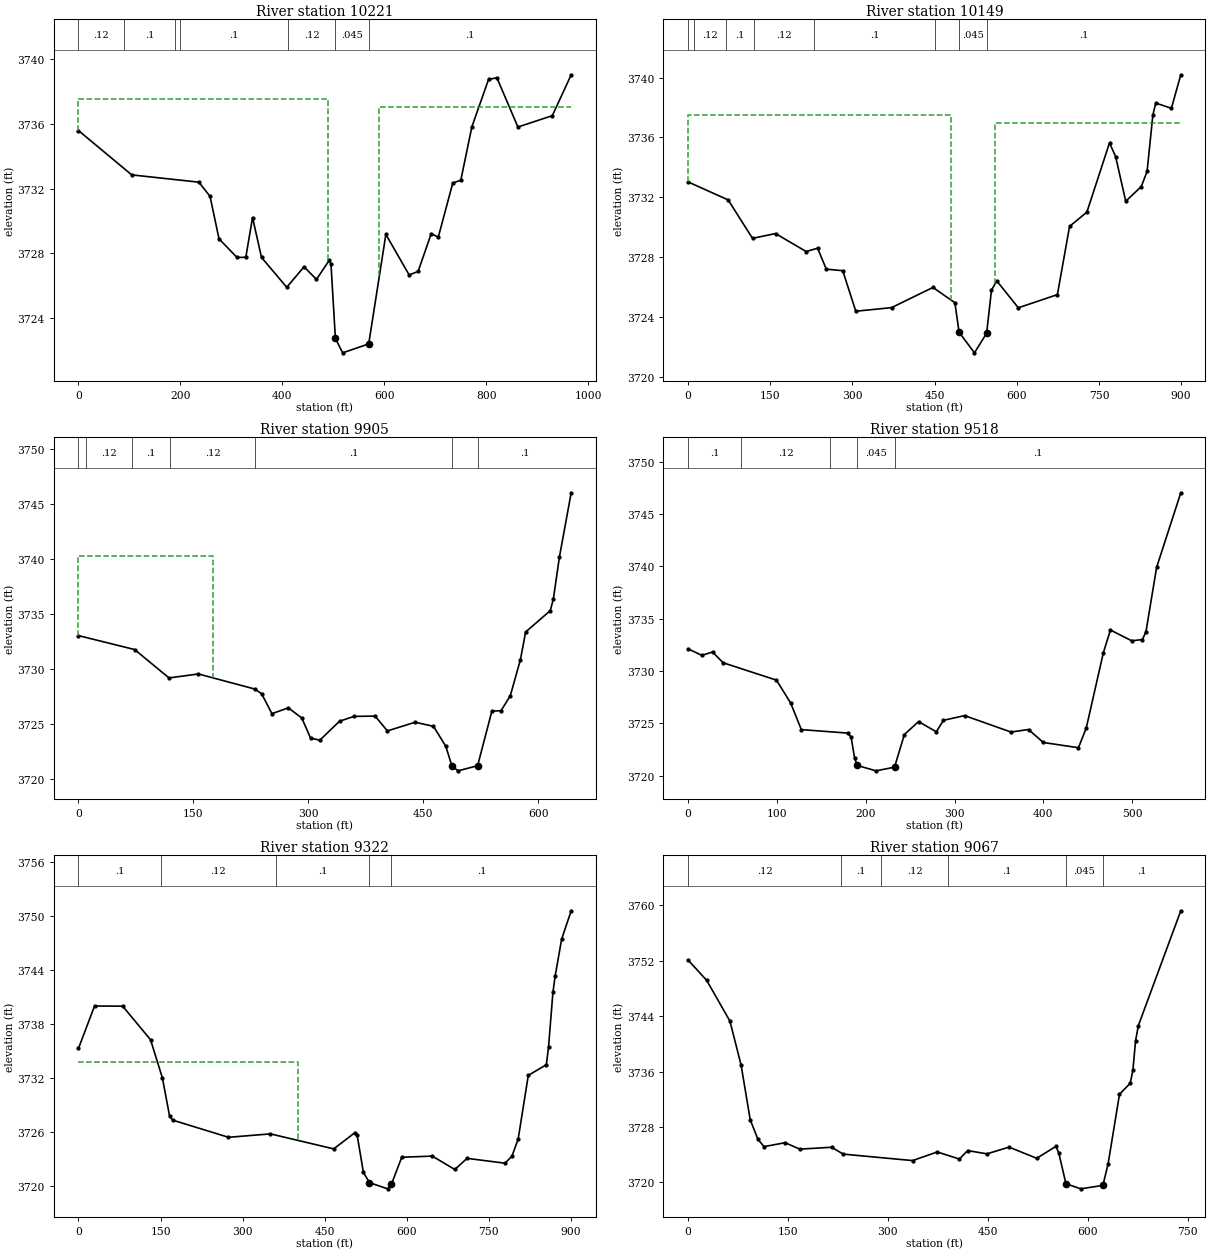
Type RM Length L Ch R = 1 ,10221   ,71,72,77.8
BEGIN DESCRIPTION:
Structure XS 3
END DESCRIPTION:
XS GIS Cut Line= 3
2272563.34453536549501.2441290172271889.87086961549197.235498039
2271735.68467399549029.958021663
#Sta/Elev= 30
       0 3735.57   104.4 3732.84   236.1 3732.39     258 3731.52   275.6  3728.9
   310.9 3727.75   328.2 3727.76   341.4 3730.21     359 3727.75   408.5 3725.91
   442.3 3727.17   466.8  3726.4   492.3 3727.59   495.3 3727.32   503.93722.758
   518.2 3721.87  569.263722.422   602.9 3729.17   648.6 3726.67   666.2 3726.89
   691.9 3729.22   705.7    3729   734.2 3732.34   749.9 3732.51   771.6  3735.8
   804.3 3738.72   820.6 3738.83   861.9 3735.79   929.4 3736.49   966.4 3739.01
#Mann= 7 ,-1,0
       0     .12       0      90      .1       0     190     .12       0
     200      .1       0     410     .12       0   503.9    .045       0
  569.26      .1       0
#XS Ineff= 2 , 0
             490  3737.5     590            3737
Permanent Ineff=
       F       F
Bank Sta=503.9,569.26
XS Rating Curve= 0 ,0
Exp/Cntr(USF)=0,0
Exp/Cntr=0.5,0.3

Type RM Length L Ch R = 1 ,10149   ,199.7,244.1,265.6
BEGIN DESCRIPTION:
Structure XS 2
END DESCRIPTION:
XS GIS Cut Line= 3
2272589.83911425549452.9194581122271916.14591406549123.986188062
2271818.68860173549010.528421477
#Sta/Elev= 30
       0 3733.03    73.1 3731.83   117.6 3729.26   159.6 3729.58   215.5 3728.38
   236.4  3728.6   252.3  3727.2   282.3  3727.1   306.1 3724.39   371.3 3724.63
     447 3725.98     487 3724.96   494.6 3722.99   522.7 3721.61   544.9 3722.92
   553.8  3725.8   563.4 3726.42   602.8 3724.62   674.1  3725.5   696.3 3730.06
   727.9 3731.01   769.2 3735.64   780.4 3734.72   798.8 3731.74   827.2 3732.72
   837.8 3733.73   848.3 3737.49   853.6  3738.3   882.2 3737.95   899.3 3740.19
#Mann= 8 ,-1,0
       0      .1       0      10     .12       0      70      .1       0
     120     .12       0     230      .1       0     450     .12       0
   494.6    .045       0   544.9      .1       0
#XS Ineff= 2 , 0
             480  3737.5     560            3737
Permanent Ineff=
       F       F
Bank Sta=494.6,544.9
XS Rating Curve= 0 ,0
Exp/Cntr(USF)=0,0
Exp/Cntr=0.5,0.3

Type RM Length L Ch R = 1 ,9905    ,384.8,386.4,384.9
BEGIN DESCRIPTION:
Structure XS 1
END DESCRIPTION:
XS GIS Cut Line= 3
2272589.68965092549451.4630713932272329.31862248549320.550263795
2272304.59064771548969.994856781
#Sta/Elev= 30
       0 3733.01    73.3 3731.74   118.1 3729.16   156.5 3729.52     230 3728.15
     239 3727.72   252.4 3725.91   273.9 3726.44   291.4 3725.51   302.8 3723.69
   314.9  3723.5   340.6 3725.22   359.3 3725.66     387 3725.69   403.1 3724.34
   439.2 3725.13   463.2 3724.76   479.3 3722.94   487.3 3721.15   495.3 3720.71
   520.83721.177   539.4 3726.14   551.4 3726.18   563.5 3727.55   576.6 3730.81
   583.5 3733.34   615.6 3735.28   619.6 3736.32   627.6 3740.18   642.9    3746
#Mann= 7 ,-1,0
       0      .1       0      10     .12       0      70      .1       0
     120     .12       0     230      .1       0   487.3    .045       0
   520.8      .1       0
#XS Ineff= 2 , 0
          175.17 3740.24
Permanent Ineff=
       F       F
Bank Sta=487.3,520.8
XS Rating Curve= 0 ,0
Exp/Cntr(USF)=0,0
Exp/Cntr=0.3,0.1

Type RM Length L Ch R = 1 ,9518    ,208.5,196.2,185.9
XS GIS Cut Line= 2
2272649.64595086549476.6909034912272653.69146797548921.993493995
#Sta/Elev= 30
       0 3732.11    15.5 3731.49    27.5 3731.81    39.5 3730.78    99.5 3729.12
   115.5 3726.93   127.5 3724.39   179.5 3724.06   183.5 3723.69   187.5 3721.66
   190.4 3720.97   211.5 3720.45   232.4  3720.8   243.5 3723.92   259.5 3725.16
   279.5 3724.18   287.5 3725.28   311.3 3725.73   363.5 3724.16   383.3  3724.4
   399.9 3723.16   439.5 3722.66   448.3 3724.55   467.5 3731.73   475.5 3733.91
   499.5 3732.88   511.5    3733   515.5 3733.75   527.5  3739.9   554.7 3747.03
#Mann= 5 ,-1,0
       0      .1       0      60     .12       0     160      .1       0
   190.4    .045       0   232.4      .1       0
Bank Sta=190.4,232.4
XS Rating Curve= 0 ,0
Exp/Cntr(USF)=0,0
Exp/Cntr=0.3,0.1

Type RM Length L Ch R = 1 ,9322    ,253.5,255.3,272.6
XS GIS Cut Line= 3
2273043.06584517549756.5164022672272743.87584654548978.722377288
2272740.96667303548911.811386738
#Sta/Elev= 30
       0  3735.3    29.3 3740.01    80.7    3740   131.7 3736.26   153.4    3732
   166.4  3727.8     172 3727.33   274.1 3725.42   350.7  3725.8   466.4 3724.13
     505 3725.93   509.3 3725.62   520.6 3721.52   531.7 3720.38   564.9 3719.69
   571.9 3720.21   590.7  3723.2   646.4 3723.33   687.7 3721.84     710 3723.08
   779.3 3722.54   792.1 3723.32   803.4 3725.22   821.9  3732.3   854.9 3733.49
   858.9 3735.44   866.9 3741.52   870.9  3743.3   882.9 3747.46   900.3  3750.6
#Mann= 5 ,-1,0
       0      .1       0     150     .12       0     360      .1       0
   531.7    .045       0   571.9      .1       0
#XS Ineff= 2 , 0
          401.93 3733.83
Permanent Ineff=
       F       F
Bank Sta=531.7,571.9
XS Rating Curve= 0 ,0
Exp/Cntr(USF)=0,0
Exp/Cntr=0.3,0.1

Type RM Length L Ch R = 1 ,9067    ,322,315.3,321.7
XS GIS Cut Line= 4
2273168.61517786549586.7396392452273040.61154376549292.913115524
2272954.79092545548975.8132037862272963.51844595548885.628825218
#Sta/Elev= 30
       0  3752.1    27.9 3749.17    62.8 3743.29    79.5 3736.98    93.3 3729.04
   104.9 3726.22     114 3725.17   145.7 3725.74   167.5 3724.81   215.5 3725.08
   232.9 3724.09   336.9 3723.16   374.1  3724.4   407.2 3723.38   419.7  3724.6
   448.7 3724.13   481.8  3725.1   523.3 3723.49   552.2 3725.21   556.4 3724.28
   567.2 3719.82   589.6 3719.08   622.7 3719.58   630.5 3722.68   647.6 3732.73
   663.7 3734.32   667.7 3736.19   671.7 3740.41   675.8 3742.61   739.6 3759.21
#Mann= 6 ,-1,0
       0     .12       0     230      .1       0     290     .12       0
   390.5      .1       0   567.2    .045       0   622.7      .1       0
Bank Sta=567.2,622.7
XS Rating Curve= 0 ,0
Exp/Cntr(USF)=0,0
Exp/Cntr=0.3,0.1

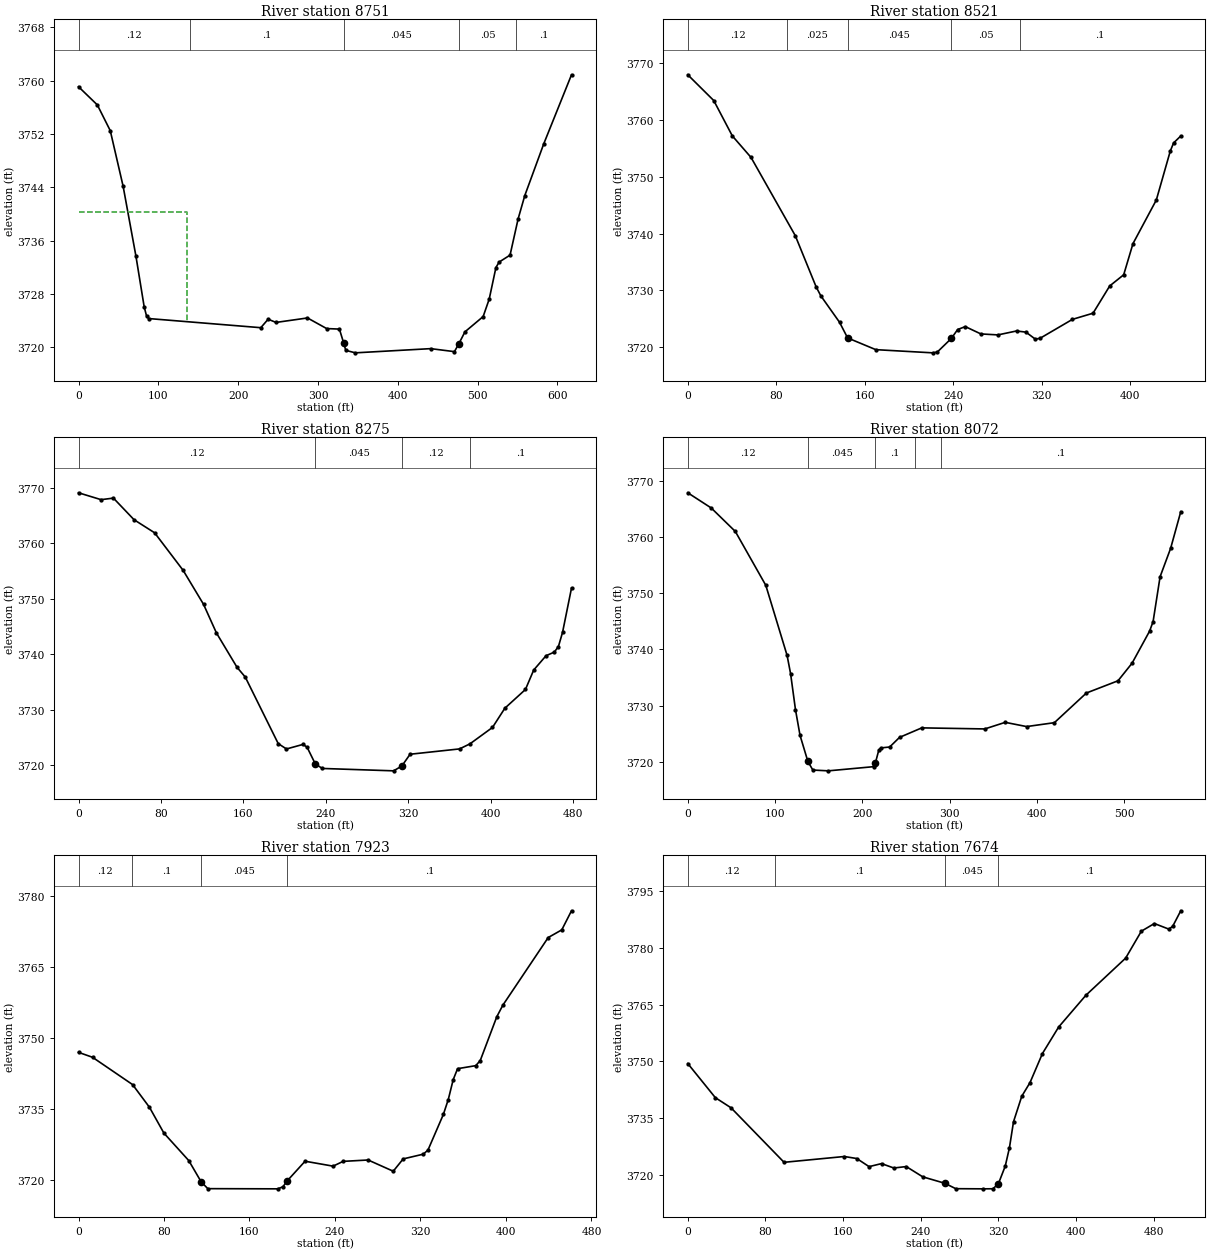
Type RM Length L Ch R = 1 ,8751    ,255.4,230.7,215
XS GIS Cut Line= 4
2273405.71281828549439.8263773852273283.52753119549224.547538223
2273276.25459744548943.8122952622273231.16240815548866.719197454
#Sta/Elev= 30
       0 3759.09    23.6 3756.36    39.8  3752.5    55.9 3744.17      72 3733.66
    82.3 3726.08    85.2 3724.74      88 3724.33   228.4 3722.96   237.6 3724.23
   247.5 3723.75   286.9 3724.42   310.9 3722.83   326.9 3722.75   332.1 3720.72
   334.9 3719.56   346.9 3719.19   441.3 3719.82     471 3719.37   476.4 3720.52
   484.2 3722.34     507 3724.63   514.6 3727.25     523 3731.98     527  3732.8
   540.7 3733.84   550.8 3739.27   559.2 3742.78     583 3750.55   617.7 3760.88
#Mann= 5 ,-1,0
       0     .12       0     140      .1       0   332.1    .045       0
   476.4     .05       0  548.37      .1       0
#XS Ineff= 2 , 0
          135.58 3740.24
Permanent Ineff=
       F       F
Bank Sta=332.1,476.4
XS Rating Curve= 0 ,0
Exp/Cntr(USF)=0,0
Exp/Cntr=0.3,0.1

Type RM Length L Ch R = 1 ,8521    ,232.9,246.1,265.4
XS GIS Cut Line= 2
2273568.62653441549211.456257463 2273428.9862063548788.171512895
#Sta/Elev= 30
       0 3767.97    23.5 3763.43    40.3  3757.2    57.2 3753.41    97.2 3739.63
   116.1 3730.59   120.3 3729.03   137.2 3724.38   144.53721.618     170 3719.55
   221.4 3718.99   225.6 3719.13   238.3 3721.53     244  3723.1   250.9 3723.61
     265 3722.32   280.4 3722.15   297.2 3722.84   305.7 3722.64   314.1 3721.42
   318.3 3721.53   347.8 3724.89   366.4 3725.97   381.5 3730.78   394.1 3732.74
   402.5 3738.23   423.6 3745.91   436.2 3754.52   439.2 3755.96   445.7 3757.19
#Mann= 5 ,-1,0
       0     .12       0      90    .025       0   144.5    .045       0
   238.3     .05       0     300      .1       0
Bank Sta=144.5,238.3
XS Rating Curve= 0 ,0
Exp/Cntr(USF)=0,0
Exp/Cntr=0.3,0.1

Type RM Length L Ch R = 1 ,8275    ,163.4,203.1,250.7
XS GIS Cut Line= 2
2273735.90401078 549207.092497212273738.81318429  548728.5334561
#Sta/Elev= 30
       0 3769.09    21.9 3767.85    33.9 3768.13    53.9 3764.24    73.9 3761.88
   101.6 3755.11   121.4 3748.99   133.9 3743.84   153.9 3737.65   161.9 3735.89
   193.9  3723.9   201.9 3722.94   217.9 3723.76   221.9 3723.26   229.9 3720.24
   236.7 3719.43   305.9    3719   313.9 3719.87   321.9 3721.99   369.9 3722.95
     380 3723.86   401.9 3726.82   413.9 3730.28   433.9 3733.66   441.9 3737.16
   453.9 3739.74   461.9 3740.39   465.9 3741.39   469.9 3743.94   478.6 3751.92
#Mann= 4 ,-1,0
       0     .12       0   229.9    .045       0   313.9     .12       0
     380      .1       0
Bank Sta=229.9,313.9
XS Rating Curve= 0 ,0
Exp/Cntr(USF)=0,0
Exp/Cntr=0.3,0.1

Type RM Length L Ch R = 1 ,8072    ,143,148.4,157.5
XS GIS Cut Line= 4
2273745.51284369549192.5038279442273967.39455839549003.691447638
2274042.14333128548900.9118849142274187.68581514548885.680052738
#Sta/Elev= 30
       0 3767.82    26.9 3765.12    54.5 3760.95    89.4 3751.39   113.8 3738.94
   117.8  3735.7   123.4 3729.31   128.6 3724.76   137.6 3720.12   143.3 3718.59
   161.1 3718.45   213.6  3719.2     215 3719.88   218.8  3722.1   221.2 3722.52
   231.3 3722.68   242.6 3724.39   268.1 3726.08   340.3 3725.89   363.7 3727.06
   388.2 3726.31     420    3727   456.7 3732.27   492.9 3734.44     509 3737.56
   529.1 3743.26   533.1 3744.95   541.1 3752.91   553.2 3757.96   564.8 3764.46
#Mann= 5 ,-1,0
       0     .12       0   137.6    .045       0     215      .1       0
     260     .12       0     290      .1       0
Bank Sta=137.6,215
XS Rating Curve= 0 ,0
Exp/Cntr(USF)=0,0
Exp/Cntr=0.3,0.1

Type RM Length L Ch R = 1 ,7923    ,209.3,249.4,292.6
XS GIS Cut Line= 3
2273824.97127657549287.8220064212274122.00536638549106.140961201
2274228.70693262549068.651221711
#Sta/Elev= 30
       0 3746.93    13.1 3745.89    50.6 3740.12    66.4 3735.33    79.9 3729.88
   103.2 3724.07   114.8 3719.58     121 3718.15   186.6 3718.11   191.3 3718.56
   195.43719.824     212 3723.94   238.2  3722.9   247.6 3723.91     271  3724.2
   294.5 3721.83   303.8 3724.43   322.6 3725.43     327  3726.3   341.4 3733.82
     346 3736.97   350.6 3741.16   354.7 3743.48   371.7 3744.12   375.9 3745.19
   391.4 3754.45   397.1  3756.9   439.5 3771.17   452.2 3772.79   461.3 3776.82
#Mann= 4 ,-1,0
       0     .12       0      50      .1       0   114.8    .045       0
   195.4      .1       0
Bank Sta=114.8,195.4
XS Rating Curve= 0 ,0
Exp/Cntr(USF)=0,0
Exp/Cntr=0.3,0.1

Type RM Length L Ch R = 1 ,7674    ,107,113.4,121.1
XS GIS Cut Line= 4
2273807.18202348549300.2844261782273876.64707487549363.379762577
2274147.95980141549460.8515732962274272.42793187549442.558493025
#Sta/Elev= 30
       0 3749.45    28.4 3740.46    44.6 3737.78    99.2 3723.42   161.3 3724.95
   174.1 3724.42   186.8 3722.28   199.6 3723.08   212.3 3721.92   225.1  3722.3
   242.1 3719.59   264.8  3717.9   276.1 3716.47   304.4 3716.43   314.4 3716.45
     320 3717.76   327.1 3722.44   331.4 3727.26   335.6 3734.12   344.1 3740.83
   352.6 3744.43   365.4 3752.09   382.1 3759.07   410.2 3767.45   451.1 3777.22
   467.3 3784.32   480.7 3786.34   495.6 3784.87   499.6 3785.61   507.9  3789.7
#Mann= 4 ,-1,0
       0     .12       0      90      .1       0   264.8    .045       0
     320      .1       0
Bank Sta=264.8,320
XS Rating Curve= 0 ,0
Exp/Cntr(USF)=0,0
Exp/Cntr=0.3,0.1

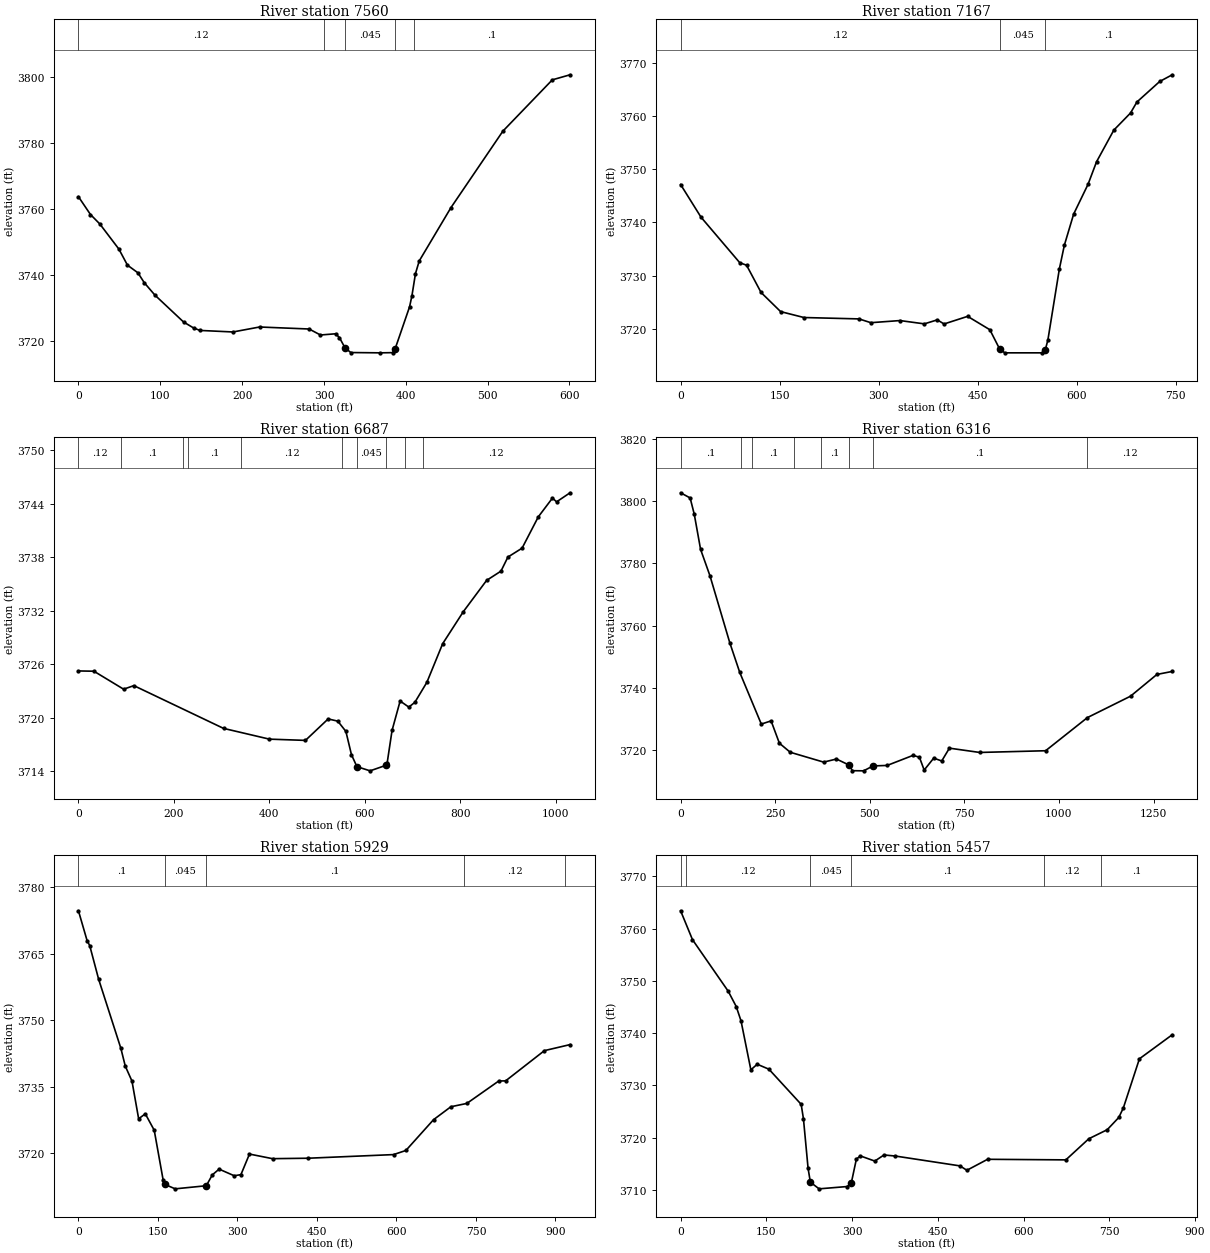
Type RM Length L Ch R = 1 ,7560    ,397.8,393.1,387.3
XS GIS Cut Line= 2
2273713.60034727 549353.682517572274230.78674765  549659.1457353
#Sta/Elev= 30
       0 3763.76    14.7 3758.35    26.2 3755.45    49.4 3747.85    59.9 3742.96
    72.7 3740.63    80.4 3737.64    93.4 3733.87   128.4  3725.7   140.6 3723.89
   148.5 3723.13   188.8 3722.66   221.3 3724.17   281.9 3723.56   295.7 3721.74
   314.2 3722.11   318.9 3720.95   325.7 3717.85   332.8 3716.41   368.7 3716.32
   383.9 3716.38     387 3717.57   404.6 3730.31   407.5 3733.69   411.8 3740.39
   416.4 3744.24   455.2 3760.46   518.6 3783.67     579 3799.26   600.7  3800.8
#Mann= 5 ,-1,0
       0     .12       0     300      .1       0   325.7    .045       0
     387     .12       0     410      .1       0
Bank Sta=325.7,387
XS Rating Curve= 0 ,0
Exp/Cntr(USF)=0,0
Exp/Cntr=0.3,0.1

Type RM Length L Ch R = 1 ,7167    ,458.7,479.9,496.4
XS GIS Cut Line= 3
2273466.71966316549595.1891454572273801.48966684549867.882592164
2274089.70225279 549989.81868622
#Sta/Elev= 30
       0  3747.1    30.9 3740.97    89.6 3732.42    99.9 3731.95   121.9 3726.83
   151.5 3723.24   186.8 3722.13   270.2 3721.87   288.2 3721.16   332.3 3721.56
   369.2 3720.94   388.8 3721.69   399.1 3720.92   434.8 3722.35   468.4 3719.84
   483.6 3716.14   491.2  3715.5   547.6  3715.5   552.53716.122   556.3 3717.88
   573.7 3731.23   581.3 3735.71   595.4 3741.56   617.1 3747.12   630.1 3751.38
   656.2 3757.31   681.5 3760.52   691.2 3762.59   725.7 3766.44   744.7  3767.7
#Mann= 3 ,-1,0
       0     .12       0   483.6    .045       0   552.5      .1       0
Bank Sta=483.6,552.5
XS Rating Curve= 0 ,0
Exp/Cntr(USF)=0,0
Exp/Cntr=0.3,0.1

Type RM Length L Ch R = 1 ,6687    ,391.9,371.4,350.1
XS GIS Cut Line= 4
2273108.59740004549879.4183564832273526.57920024550193.784516278
2273639.64721473550317.9376302262273958.89807917550204.869615737
#Sta/Elev= 30
       0 3725.24    32.4 3725.21    94.6 3723.19   116.1 3723.59   303.8 3718.79
   399.9 3717.58   475.4 3717.44     523 3719.85   543.2  3719.6   560.1 3718.45
   571.8 3715.83   583.2 3714.49   610.8 3714.02   643.13714.623   646.6 3714.92
   656.8 3718.56   673.7 3721.86   691.9 3721.18   704.5 3721.71   729.7 3723.96
   762.8  3728.3   806.1  3731.9   854.8 3735.41   884.9 3736.45   899.4 3738.03
   929.1 3739.03   963.1 3742.55   992.8 3744.66  1001.3 3744.23  1029.6 3745.25
#Mann= 10 ,-1,0
       0     .12       0      90      .1       0     220     .12       0
     230      .1       0     340     .12       0  553.01      .1       0
   583.2    .045       0   643.1     .12       0  683.01      .1       0
  720.93     .12       0
Bank Sta=583.2,643.1
XS Rating Curve= 0 ,0
Exp/Cntr(USF)=0,0
Exp/Cntr=0.3,0.1

Type RM Length L Ch R = 1 ,6316    ,458.6,387.1,320.7
XS GIS Cut Line= 5
2272837.08601385550479.7800823362273047.70290359550386.665246875
2273528.79622013550546.2906790942273712.80887116550324.588689901
2273965.54913884550218.171735089
#Sta/Elev= 30
       0  3802.6    25.2 3800.94    36.1 3795.73    52.8 3784.44    77.7 3775.93
   130.2 3754.39   156.4 3744.93   213.3 3728.37   239.2 3729.39   261.1 3722.23
   289.8 3719.32     378 3716.16     412 3717.15   445.7 3715.19   454.1 3713.41
   483.6 3713.36   508.9 3714.94   545.9 3715.09   614.3 3718.32   631.2 3717.74
   643.8 3713.61   669.1 3717.45   690.2 3716.52   710.5 3720.64   790.6 3719.26
   964.8 3719.81  1075.3 3730.45  1189.3 3737.32    1259  3744.3  1299.5 3745.26
#Mann= 8 ,-1,0
       0      .1       0     160     .12       0     190      .1       0
  300.28     .12       0  370.28      .1       0   445.7    .045       0
   508.9      .1       0 1075.28     .12       0
Bank Sta=445.7,508.9
XS Rating Curve= 0 ,0
Exp/Cntr(USF)=0,0
Exp/Cntr=0.3,0.1

Type RM Length L Ch R = 1 ,5929    ,479.1,471.7,461.8
XS GIS Cut Line= 4
2273431.24734489550905.4479015862273533.23025992550583.980017257
 2273730.5450303550331.2397495772273981.06827809 550231.47385444
#Sta/Elev= 30
       0  3774.7    16.3 3767.98    21.3 3766.84    38.1 3759.25      80 3743.67
    88.4 3739.63     101 3736.26   113.6 3727.75   126.2 3728.86     143 3725.16
   159.7 3714.01   162.73712.952   182.5 3711.93   241.2 3712.63   252.6 3715.08
   265.4 3716.38     294 3714.88   306.6 3715.14   322.7 3719.78   366.2 3718.74
     433 3718.84   594.5 3719.66   617.8 3720.59     670 3727.54   702.7 3730.46
   732.8 3731.21   793.1 3736.28     806  3736.3   879.2 3743.13   927.6 3744.49
#Mann= 5 ,-1,0
       0      .1       0   162.7    .045       0   241.2      .1       0
   727.9     .12       0   917.9      .1       0
Bank Sta=162.7,241.2
XS Rating Curve= 0 ,0
Exp/Cntr(USF)=0,0
Exp/Cntr=0.3,0.1

Type RM Length L Ch R = 1 ,5457    ,367.2,345.5,322.6
XS GIS Cut Line= 3
2273821.44284587551096.1116122922273916.77470122551000.779756939
2273998.80443722550280.248292063
#Sta/Elev= 30
       0 3763.41    20.8 3757.88    83.2 3748.04    97.3  3745.1   105.7 3742.35
   122.9 3732.99     134 3734.06   154.5 3733.11   210.9 3726.39   214.9 3723.62
     223 3714.15     227  3711.5   242.3 3710.23   291.4 3710.67   298.6 3711.36
   307.5 3715.93   314.6 3716.52   339.7 3715.54   355.8 3716.71   375.8  3716.5
   488.7 3714.62   500.8 3713.78     537 3715.88   673.9 3715.77   714.1 3719.81
   746.3 3721.54   766.5 3723.88   774.5 3725.71   802.6  3735.1     860  3739.7
#Mann= 6 ,-1,0
       0      .1       0      10     .12       0     227    .045       0
   298.6      .1       0  634.82     .12       0  734.82      .1       0
Bank Sta=227,298.6
XS Rating Curve= 0 ,0
Exp/Cntr(USF)=0,0
Exp/Cntr=0.3,0.1