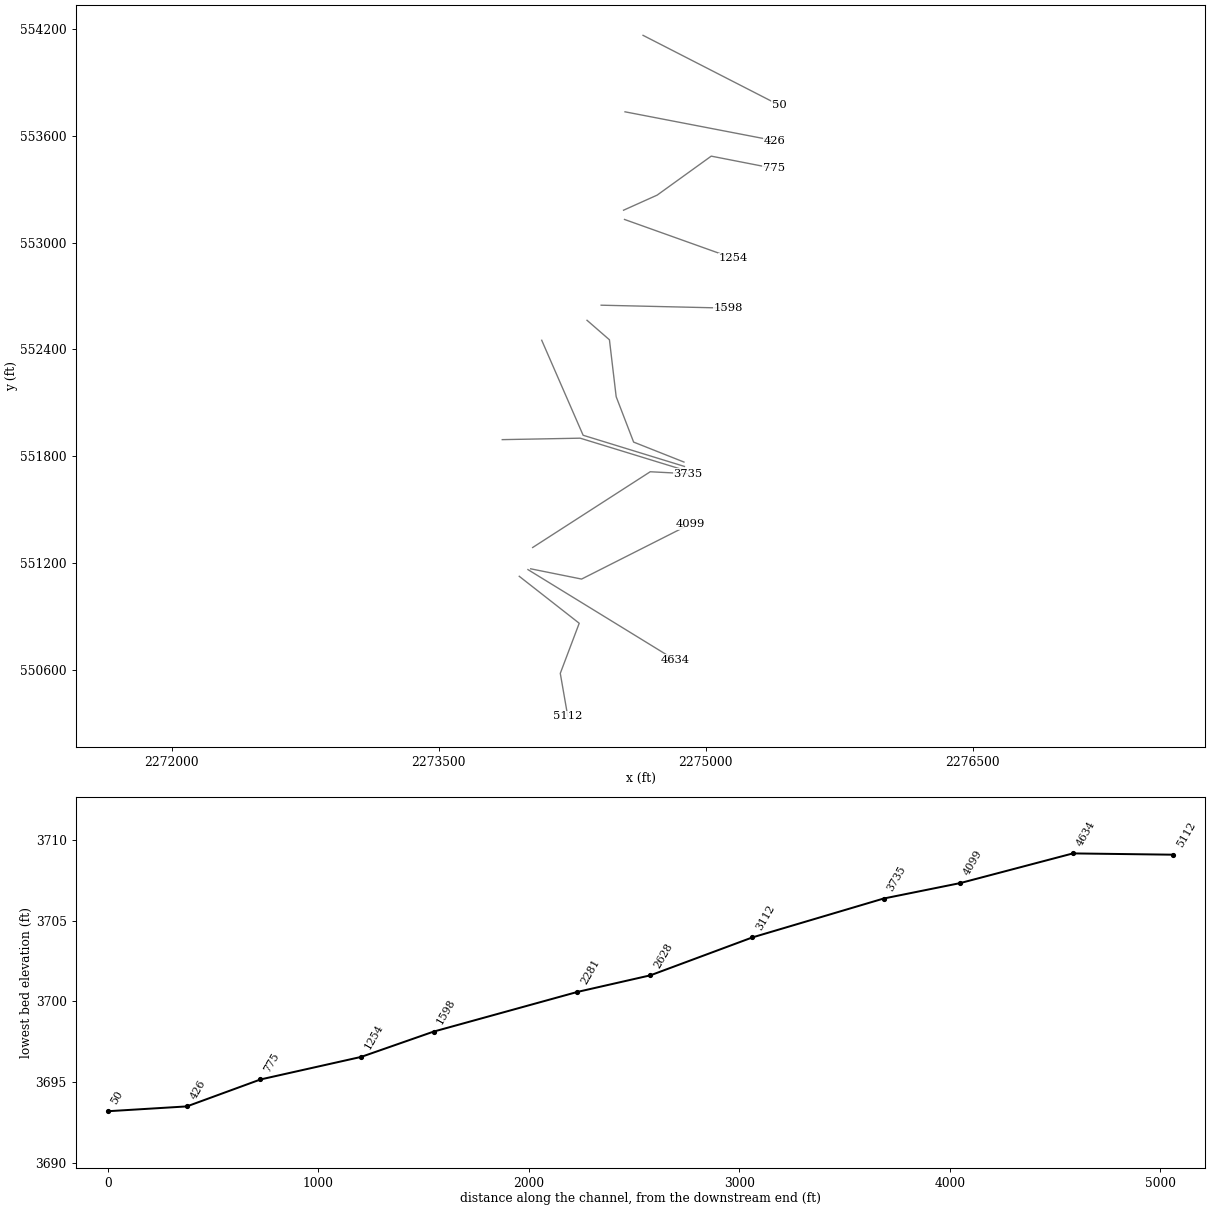
HEC-RAS study SHVRSFK.prj: SHVRSFK

--- SHVRSFK.g01 (geometry) --- (continued)

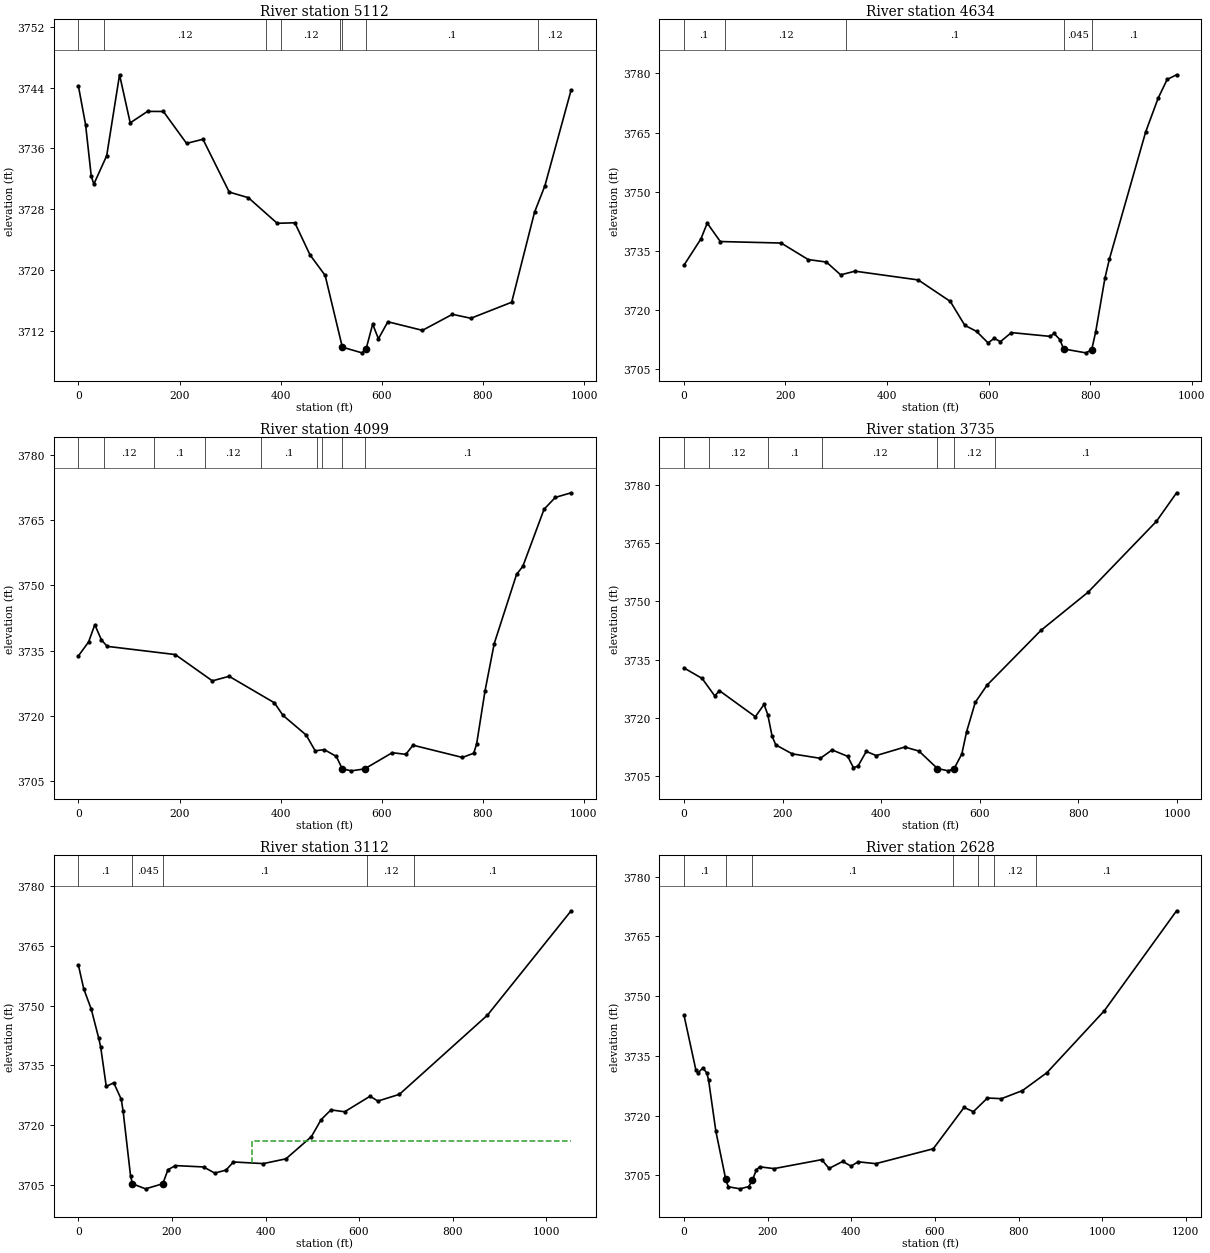
Type RM Length L Ch R = 1 ,5112    ,439.4,477.4,539
XS GIS Cut Line= 4
2273952.24701949551124.9328708872274289.23404307550861.107503748
2274182.81708825550579.545977473 2274224.9404662550337.890809253
#Sta/Elev= 30
       0 3744.16      14 3739.15    25.3 3732.33    30.4 3731.31    55.8 3735.05
    81.2  3745.7   102.3 3739.37   136.5 3740.88   167.9 3740.87   213.7 3736.67
   246.2 3737.21   298.1 3730.26     336 3729.52     393 3726.15   427.9 3726.22
   457.8    3722   487.8 3719.29   521.8 3709.85   560.5  3709.1     569 3709.67
   581.8 3712.87   593.2 3710.95   611.8 3713.19   680.2 3712.06   739.5 3714.17
     776 3713.65   856.7 3715.76   901.9 3727.61   922.4 3731.09   974.3 3743.71
#Mann= 8 ,-1,0
       0      .1       0      50     .12       0     370      .1       0
     400     .12       0  517.98      .1       0   521.8    .045       0
     569      .1       0  908.98     .12       0
Bank Sta=521.8,569
XS Rating Curve= 0 ,0
Exp/Cntr(USF)=0,0
Exp/Cntr=0.3,0.1

Type RM Length L Ch R = 1 ,4634    ,508,535.3,581.4
XS GIS Cut Line= 2
2274001.02145711 551162.62220905 2274827.9698768550654.924653799
#Sta/Elev= 30
       0 3731.38    33.3 3738.01    45.9 3742.04    71.6 3737.38   191.4    3737
   244.7 3732.82   280.6 3732.18   308.7 3728.94     337 3729.87   461.5 3727.65
   524.7  3722.2   553.2 3716.15   576.3 3714.62   599.1 3711.69   611.2 3712.87
   623.3    3712     645 3714.31   721.4 3713.35   729.1 3714.09   740.6 3712.51
   747.8 3710.17   791.5 3709.18   803.1 3709.93     811 3714.47   829.3 3728.15
     838 3732.92   909.6  3765.2     934 3773.68   951.8 3778.45   970.4 3779.63
#Mann= 5 ,-1,0
       0      .1       0      80     .12       0     320      .1       0
   747.8    .045       0   803.1      .1       0
Bank Sta=747.8,803.1
XS Rating Curve= 0 ,0
Exp/Cntr(USF)=0,0
Exp/Cntr=0.3,0.1

Type RM Length L Ch R = 1 ,4099    ,363.9,364.3,365.5
XS GIS Cut Line= 3
2274016.54059636551167.0562488342274302.53616242551109.413731644
 2274912.2166327551417.579496622
#Sta/Elev= 30
       0  3733.8      20    3737    32.3 3740.96    45.4 3737.45    56.8 3735.98
   191.5 3734.09   264.9 3728.04   298.1 3729.09   387.7 3722.99   404.7  3720.1
   450.5 3715.58   468.4 3711.94   486.3 3712.22   510.1 3710.67     522  3707.8
   540.1 3707.34   566.1 3707.78   620.8 3711.51   647.7 3711.14     662 3713.24
   759.7 3710.42   782.1 3711.39   787.8 3713.48   804.5 3725.75   822.7 3736.62
   866.9 3752.54   879.3 3754.39   921.3 3767.52   943.5 3770.24   974.9 3771.31
#Mann= 9 ,-1,0
       0      .1       0      50     .12       0     150      .1       0
     250     .12       0  361.75      .1       0  471.75     .12       0
  481.75      .1       0     522    .045       0   566.1      .1       0
Bank Sta=522,566.1
XS Rating Curve= 0 ,0
Exp/Cntr(USF)=0,0
Exp/Cntr=0.3,0.1

Type RM Length L Ch R = 1 ,3735    ,652.2,622.9,588.9
XS GIS Cut Line= 3
2274027.62569582551286.7753229982274688.29762361551712.443142248
2274901.13153324551701.358042789
#Sta/Elev= 30
       0 3732.86    36.9 3730.15    62.5 3725.65      72    3727   144.8  3720.3
   162.4 3723.46     170 3720.85   178.7 3715.31   186.2 3713.06   219.5 3710.75
   276.6  3709.6   300.4 3711.76     332 3710.11   343.6 3707.23   352.8 3707.56
   369.7 3711.37   389.9 3710.31   447.9  3712.5   476.5 3711.47     514 3706.98
   536.2 3706.38   547.9 3706.94   563.5 3710.73   573.1  3716.4   590.7 3723.99
   614.5 3728.41   723.9 3742.52   819.4 3752.33     958 3770.56     999 3777.92
#Mann= 7 ,-1,0
       0      .1       0      50     .12       0     170      .1       0
     280     .12       0     514    .045       0   547.9     .12       0
     630      .1       0
Bank Sta=514,547.9
XS Rating Curve= 0 ,0
Exp/Cntr(USF)=0,0
Exp/Cntr=0.3,0.1

Type RM Length L Ch R = 1 ,3112    ,531.8,484.2,432.6
XS GIS Cut Line= 3
2273856.81938472 551892.843571442274294.74923992551901.054756225
2274883.21748284551720.408690957
#Sta/Elev= 30
       0 3760.09    11.2 3754.23    27.4 3749.08    43.4 3741.75    47.4 3739.64
    59.4  3729.7    75.4 3730.61    91.4 3726.49    95.4 3723.54   111.4 3707.16
   115.4 3705.24   143.4 3703.97   180.3 3705.25   191.4 3708.78   207.4 3709.81
   267.4 3709.47   291.4 3707.93   315.4 3708.67   331.4 3710.72   395.4 3710.31
   443.7 3711.51   498.1 3717.08   518.8 3721.34   539.9 3723.81   569.2 3723.33
   623.6 3727.24   640.3 3726.02   686.4 3727.72   874.7 3747.62  1053.6 3773.83
#Mann= 5 ,-1,0
       0      .1       0   115.4    .045       0   180.3      .1       0
  618.01     .12       0  718.01      .1       0
#XS Ineff= 2 , 0
                          371.61         3716.07
Permanent Ineff=
       F       F
Bank Sta=115.4,180.3
XS Rating Curve= 0 ,0
Exp/Cntr(USF)=0,0
Exp/Cntr=0.3,0.1

Type RM Length L Ch R = 1 ,2628    ,358.7,346.7,334.7
XS GIS Cut Line= 3
2274078.52137391552451.2041368142274311.17160949551917.477125795
2274880.48042124551742.305183716
#Sta/Elev= 30
       0 3745.27    28.4 3731.53    33.2 3730.68    45.3 3731.99    54.6 3730.71
    58.9 3728.94    76.4 3716.03     100 3703.98   106.1 3702.14   134.3 3701.62
   154.9 3702.19   163.9 3703.83     173 3706.37   181.1 3707.15   215.5  3706.7
   329.5 3708.95   346.9 3706.74   379.6  3708.5   399.3 3707.33   416.7 3708.41
   458.6 3707.94   596.1 3711.68   669.7 3722.05   692.1    3721   725.6 3724.43
   759.1 3724.26   809.3 3726.29   867.9 3730.79  1004.9 3746.31  1177.9 3771.44
#Mann= 7 ,-1,0
       0      .1       0     100    .045       0   163.9      .1       0
  642.23     .12       0  702.23      .1       0  742.23     .12       0
  842.23      .1       0
Bank Sta=100,163.9
XS Rating Curve= 0 ,0
Exp/Cntr(USF)=0,0
Exp/Cntr=0.3,0.1

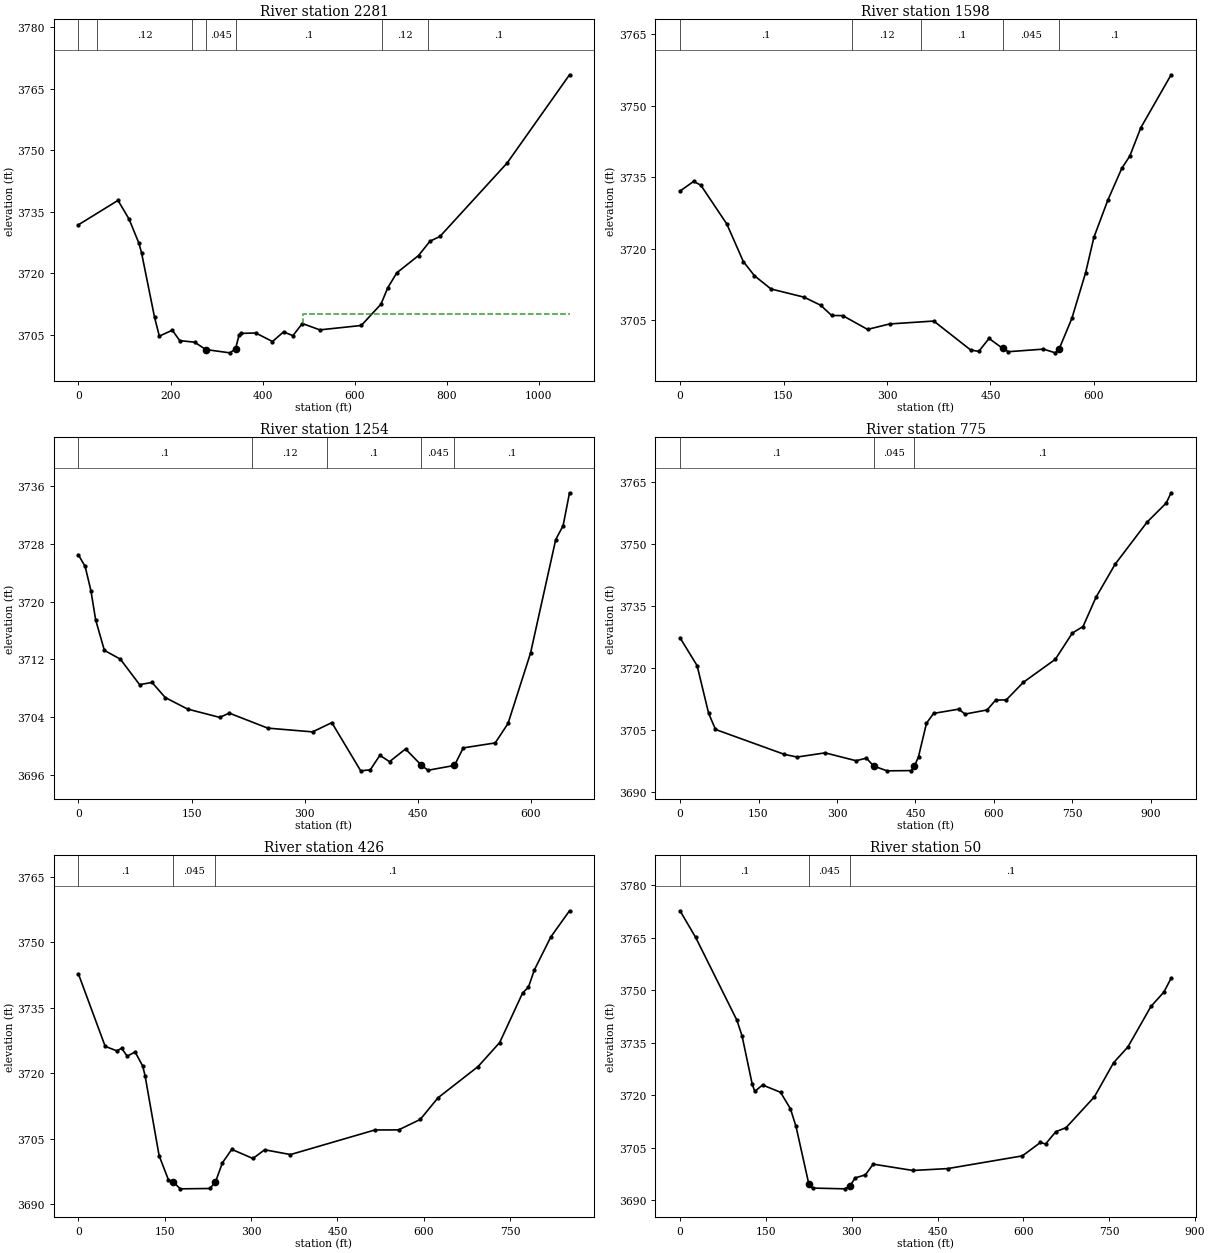
Type RM Length L Ch R = 1 ,2281    ,623.2,682.9,758.8
XS GIS Cut Line= 5
2274333.06810225552563.4236622082274458.97293561552453.941198409
2274496.88294175552134.1106936462274594.88930818551879.092187199
2274877.74335965551766.938738071
#Sta/Elev= 30
       0 3731.81      86 3737.76   110.1 3733.17   131.4  3727.3   137.1 3724.97
   165.4 3709.22   175.7 3704.67   203.9 3706.11     220 3703.57   252.2 3703.19
  276.583701.395   328.7 3700.59341.1683 3701.54   348.9 3704.98   352.9 3705.33
   385.1 3705.43   421.4 3703.35   445.5  3705.7   465.7 3704.78   486.2 3707.74
   524.2 3706.19   614.2 3707.26     657 3712.46   671.7 3716.45   691.3  3720.1
   738.5 3724.31   763.5 3727.82     785 3728.96     931 3746.89  1066.4 3768.39
#Mann= 7 ,-1,0
       0      .1       0      40     .12       0  246.85      .1       0
  276.58    .045       0341.1683      .1       0  658.92     .12       0
  758.92      .1       0
#XS Ineff= 2 , 0
                          486.85         3710.15
Permanent Ineff=
       F       F
Bank Sta=276.58,341.1683
XS Rating Curve= 0 ,0
Exp/Cntr(USF)=0,0
Exp/Cntr=0.3,0.1

Type RM Length L Ch R = 1 ,1598    ,356.4,344.3,328.9
XS GIS Cut Line= 2
 2274412.4428885552648.2725716522275124.07890319552631.850202082
#Sta/Elev= 30
       0 3732.07    19.7 3734.09    30.1 3733.32    67.8 3725.17    91.8 3717.28
   107.8 3714.32   131.8 3711.53   179.8 3709.81   203.8 3708.12   219.8 3705.97
   235.8 3705.94   271.8 3703.05   303.8 3704.19   367.8  3704.8   421.2 3698.73
     433 3698.43   447.9 3701.15   467.5 3699.08   475.9 3698.37   526.8 3698.91
   543.9 3698.13   549.5 3698.96   567.9 3705.34   587.9 3714.96   599.9 3722.37
   619.9 3730.11   640.2 3736.81   651.9 3739.42   667.9 3745.37   711.8 3756.47
#Mann= 5 ,-1,0
       0      .1       0     250     .12       0     350      .1       0
   467.5    .045       0   549.5      .1       0
Bank Sta=467.5,549.5
XS Rating Curve= 0 ,0
Exp/Cntr(USF)=0,0
Exp/Cntr=0.3,0.1

Type RM Length L Ch R = 1 ,1254    ,435.9,478.4,509.9
XS GIS Cut Line= 2
2274543.82184506553129.9954123672275156.92364233 552911.03048477
#Sta/Elev= 30
       0 3726.49     8.9 3724.89    16.6 3721.53    22.8 3717.51    34.4 3713.26
    55.6 3712.04    81.1 3708.51    97.6 3708.81   115.1 3706.72   144.8 3705.12
   187.3 3703.97     200 3704.56     251 3702.48   310.4 3701.96   335.9 3703.24
   374.2 3696.56   386.9  3696.7   399.6 3698.71   412.4 3697.83   433.6 3699.59
   454.4 3697.36   463.3 3696.64   498.5 3697.31   510.1 3699.74   552.5 3700.43
   569.5 3703.13   599.3 3712.88   632.7 3728.61   642.5 3730.54     651  3735.1
#Mann= 5 ,-1,0
       0      .1       0     230     .12       0     330      .1       0
   454.4    .045       0   498.5      .1       0
Bank Sta=454.4,498.5
XS Rating Curve= 0 ,0
Exp/Cntr(USF)=0,0
Exp/Cntr=0.3,0.1

Type RM Length L Ch R = 1 ,775     ,389.1,349.5,313.3
XS GIS Cut Line= 4
2274538.34772187553181.9995826722274727.20497192553266.848492116
2275031.01880896553485.8134197142275381.36269312 553417.38687984
#Sta/Elev= 30
       0 3727.29    32.7 3720.55    54.6 3709.09    67.8 3705.15   199.3 3699.14
   223.7 3698.49   277.3  3699.5   336.4  3697.6   356.2 3698.23   369.9 3696.33
   395.7 3695.16   441.5 3695.22     4483696.264   455.8  3698.6     471 3706.65
   484.7 3709.03   532.6 3710.05   544.7 3708.86   586.8 3709.86   603.1 3712.23
   623.5 3712.29   656.1 3716.53   717.2 3722.08   749.8 3728.43   770.2    3730
   794.9 3737.05   831.3    3745   892.5 3755.19   929.1  3759.8   938.5 3762.28
#Mann= 3 ,-1,0
       0      .1       0   369.9    .045       0     448      .1       0
Bank Sta=369.9,448
XS Rating Curve= 0 ,0
Exp/Cntr(USF)=0,0
Exp/Cntr=0.3,0.1

Type RM Length L Ch R = 1 ,426     ,375.8,375.8,375.8
XS GIS Cut Line= 2
2274546.55890665553734.8860248562275384.09975471553573.399390753
#Sta/Elev= 30
       0 3742.79    46.5 3726.17    66.8 3725.13      75 3725.73    84.8 3723.91
    98.5 3724.89   111.6 3721.67   115.7 3719.48   140.2 3701.08   156.4 3695.54
   164.6 3695.11   176.8 3693.49   228.2 3693.57   237.9 3695.01   250.1 3699.46
   266.4 3702.54   303.1 3700.45   323.5 3702.45   368.3 3701.35   514.9 3706.99
   556.1 3707.01   593.7  3709.4   624.4 3714.35   694.2 3721.54   731.7 3727.04
   771.6 3738.43   781.5  3739.7   791.9 3743.69   820.5 3751.26     853 3757.26
#Mann= 3 ,-1,0
       0      .1       0   164.6    .045       0   237.9      .1       0
Bank Sta=164.6,237.9
XS Rating Curve= 0 ,0
Exp/Cntr(USF)=0,0
Exp/Cntr=0.3,0.1

Type RM Length L Ch R = 1 ,50      ,,,
XS GIS Cut Line= 2
2274647.83018567554164.6046952672275411.47037066553773.204887186
#Sta/Elev= 30
       0 3772.67    27.4 3765.04    99.3 3741.42   108.3 3736.98   126.2 3723.08
   130.7 3721.05   144.2 3722.88   175.7 3720.78     193 3716.05   202.7 3711.02
   225.1 3694.52   231.6 3693.41     288 3693.19   296.9 3693.98     306 3696.32
     324 3697.19   337.5 3700.25   406.9 3698.44   467.8 3698.98   598.2 3702.61
   629.7 3706.44   638.7 3706.01   656.6 3709.51   674.6 3710.69   724.1  3719.5
   757.6 3729.24   782.5 3733.73   822.9 3745.34   845.4 3749.42   858.1 3753.41
#Mann= 3 ,-1,0
       0      .1       0   225.1    .045       0   296.9      .1       0
Bank Sta=225.1,296.9
XS Rating Curve= 0 ,0
Exp/Cntr(USF)=0,0
Exp/Cntr=0.3,0.1
LCMann Table=0

Chan Stop Cuts=-1
Use User Specified Reach Order=0
Composite Channel Slope=5